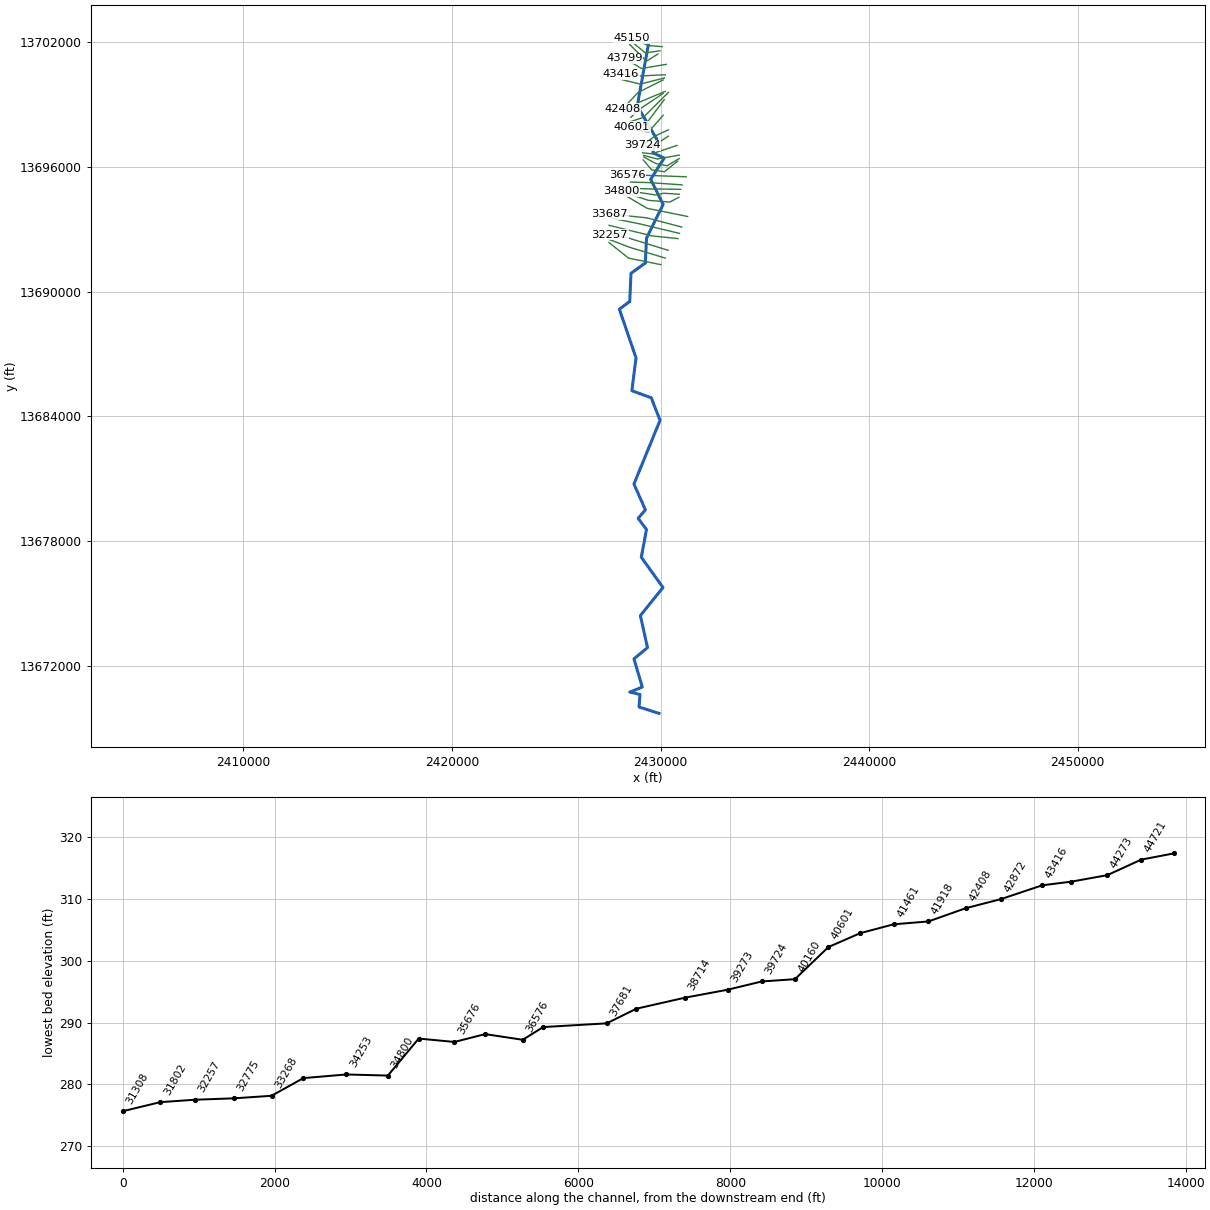
--- WEST BRUSHY CREEK.prj (project) ---

Proj Title=WEST BRUSHY CREEK Base Level Engineering
Current Plan=p01
Default Exp/Contr=0.3,0.1
English Units
Geom File=g01
Flow File=f01
Plan File=p01
Y Axis Title=Elevation
X Axis Title(PF)=Main Channel Distance
X Axis Title(XS)=Station
BEGIN DESCRIPTION:
WEST BRUSHY CREEK
END DESCRIPTION:
DSS Export Rating Curves= 0
DSS Export Rating Curve Sorted= 0
DSS Export Volume Flow Curves= 0
DXF OffsetX= 0
DXF OffsetY= 0
DXF ScaleX= 1
DXF ScaleY= 10

--- WEST BRUSHY CREEK.p01 (plan) ---

Plan Title=Multiple Run
Short Identifier=Multiple
Geom File=g01
Flow File=f01
Subcritical Flow
K Sum by GR= 0
Std Step Tol= 0.01
Critical Tol= 0.01
Num of Std Step Trials= 20
Max Error Tol= 0.3
Flow Tol Ratio= 0.001
Split Flow NTrial= 30
Split Flow Tol= 0.02
Split Flow Ratio= 0.02
Log Output Level= 0
Friction Slope Method= 1
Unsteady Friction Slope Method= 2
Unsteady Bridges Friction Slope Method= 1
Parabolic Critical Depth
Global Vel Dist=  1 , 1 , 1
Global Log Level= 0
CheckData=True
Encroach Param= -1, 0, 0, 0
BEGIN DESCRIPTION:
Multiple Run
END DESCRIPTION:

--- WEST BRUSHY CREEK.f01 (steady flow) ---

Flow Title=Multiple
Number of Profiles=7
Profile Names=10-year,25-year,50-year,1pct_min,100-year,1pct_plu,500-year
River Rch & RM= WEST BRUSHY CREE,Reach-1,45150
     637    1018    1359     877    1751    3493    2880
River Rch & RM= WEST BRUSHY CREE,Reach-1,42872
     934    1524    2061    1347    2688    5363    4531
River Rch & RM= WEST BRUSHY CREE,Reach-1,38714
    1138    1871    2544    1670    3332    6649    5668
River Rch & RM= WEST BRUSHY CREE,Reach-1,35206
    1349    2234    3050    2010    4010    8002    6874
River Rch & RM= WEST BRUSHY CREE,Reach-1,33268
    1416    2345    3203    2110    4209    8399    7211
River Rch & RM= WEST BRUSHY CREE,Reach-1,27433
    1623    2701    3702    2446    4881    9739    8413
River Rch & RM= WEST BRUSHY CREE,Reach-1,24799
    1771    2960    4068    2695    5377   10728    9313
River Rch & RM= WEST BRUSHY CREE,Reach-1,24381
    1845    3078    4224    2793    5573   11120    9620
River Rch & RM= WEST BRUSHY CREE,Reach-1,18865
    1919    3205    4402    2913    5812   11596   10047
River Rch & RM= WEST BRUSHY CREE,Reach-1,17485
    2160    3616    4974    3295    6574   13118   11390
River Rch & RM= WEST BRUSHY CREE,Reach-1,11474
    2271    3802    5231    3464    6912   13792   11970
River Rch & RM= WEST BRUSHY CREE,Reach-1,7265
    2366    3962    5449    3607    7197   14359   12450
River Rch & RM= WEST BRUSHY CREE,Reach-1,1651
    2435    4075    5605    3709    7401   14767   12797
Boundary for River Rch & Prof#=WEST BRUSHY CREE,Reach-1,1
Up Type=0
Dn Type=3
Dn Slope=0.001
Boundary for River Rch & Prof#=WEST BRUSHY CREE,Reach-1,2
Up Type=0
Dn Type=3
Dn Slope=0.001
Boundary for River Rch & Prof#=WEST BRUSHY CREE,Reach-1,3
Up Type=0
Dn Type=3
Dn Slope=0.001
Boundary for River Rch & Prof#=WEST BRUSHY CREE,Reach-1,4
Up Type=0
Dn Type=3
Dn Slope=0.001
Boundary for River Rch & Prof#=WEST BRUSHY CREE,Reach-1,5
Up Type=0
Dn Type=3
Dn Slope=0.001
Boundary for River Rch & Prof#=WEST BRUSHY CREE,Reach-1,6
Up Type=0
Dn Type=3
Dn Slope=0.001
Boundary for River Rch & Prof#=WEST BRUSHY CREE,Reach-1,7
Up Type=0
Dn Type=3
Dn Slope=0.001

--- WEST BRUSHY CREEK.g01 (geometry) ---

Geom Title=Existing Conditions
Program Version=4.10

River Reach=WEST BRUSHY CREE,Reach-1
Reach XY= 30
        2429425.       13701925.      2428882.53     13698925.01
      2429823.03     13697319.11      2429630.52     13696672.56
      2430173.46     13696419.17      2429524.53     13695395.25
       2430124.5      13694190.2      2429326.96     13692569.11
      2429271.56     13691376.19        2428583.     13690878.35
      2428521.97     13689526.39       2428024.6     13689154.86
      2428823.78      13686814.5       2428626.5     13685236.43
      2429555.41      13684895.2      2429975.05     13683809.66
       2428724.6       13680750.      2429274.62     13679509.73
      2428924.95     13679105.02      2429324.91      13678559.6
      2429077.04     13677230.85      2430118.02     13675774.79
      2429032.81     13674428.41      2429374.35     13672885.64
      2428724.52     13672345.16      2429124.62     13670990.15
      2428524.37     13670749.92      2429013.92     13670635.39
      2428968.67     13670032.34        2429925.       13669725.

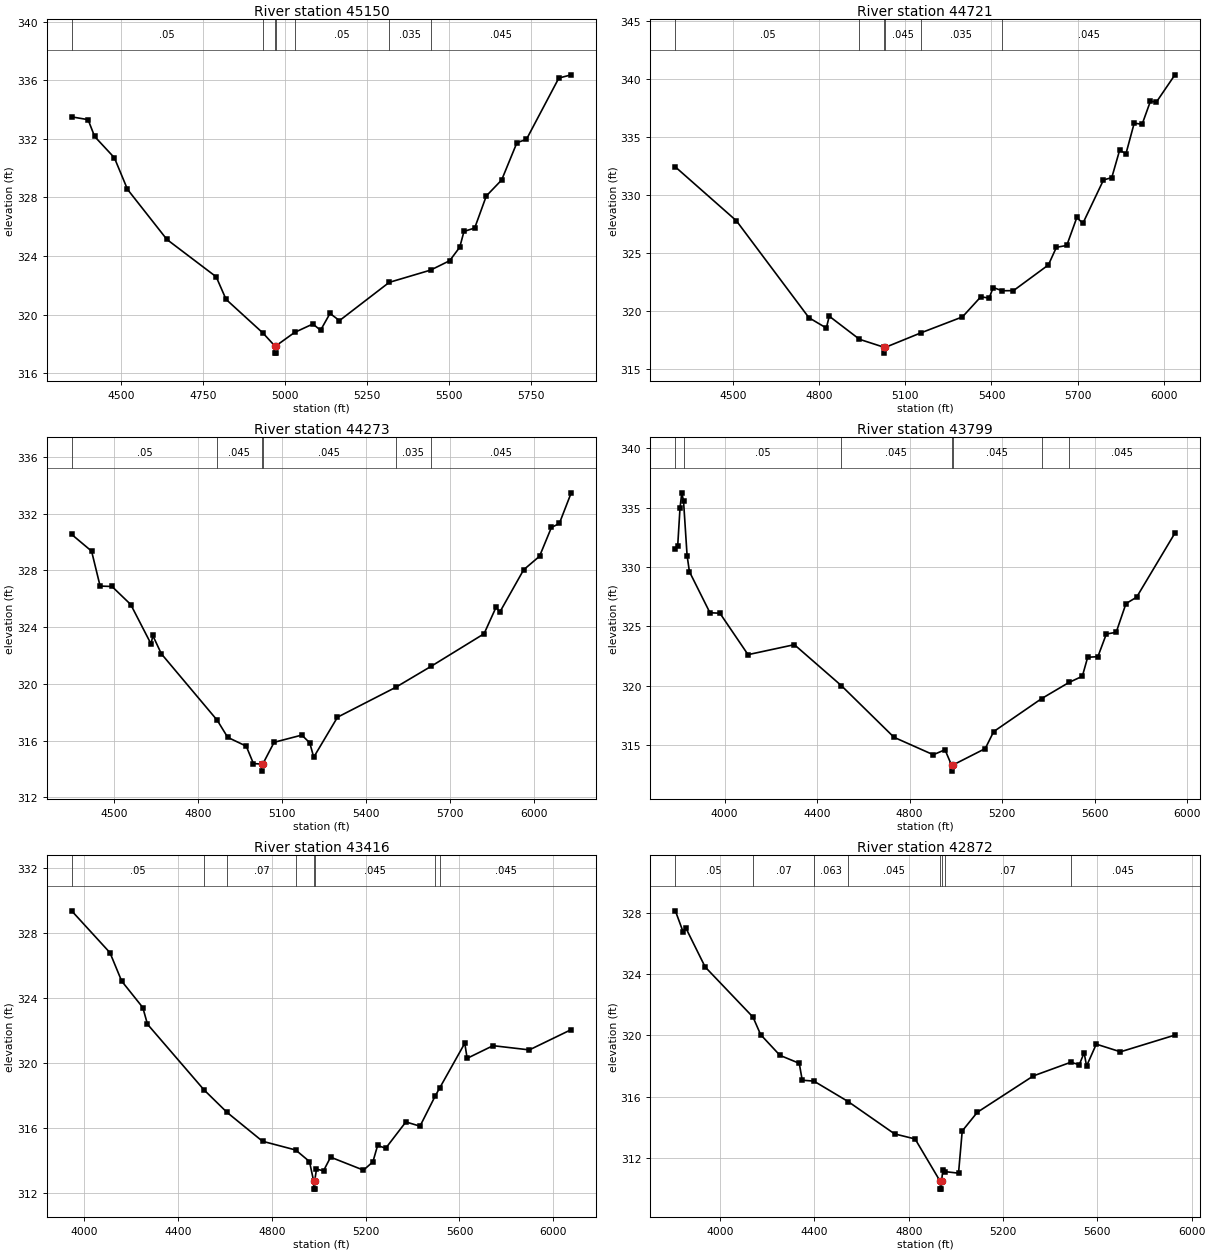
Type RM Length L Ch R = 1 ,45150   ,429,429,429
BEGIN DESCRIPTION:
WEST BRUSHY CREEK 76.0
END DESCRIPTION:
XS GIS Cut Line= 3
      2430074.99       13701775.        2429425.       13701825.
      2428625.02     13702174.99
#Sta/Elev= 30
  4348.2   333.5  4398.3  333.31  4418.4  332.16  4478.6  330.71  4518.7  328.55
    4639  325.13  4789.5  322.58  4819.6  321.04  4932.3  318.74    4968  317.87
  4968.2  317.37  4971.8  317.37  4972.1  317.87  5028.6  318.78  5084.7  319.36
  5108.1  318.93  5136.9  320.08  5165.8  319.59  5317.6   322.2  5444.2  323.04
  5502.2  323.68    5533   324.6  5545.9  325.68  5578.6  325.91  5614.1   328.1
  5660.9  329.19  5707.6  331.74  5736.5  331.96  5835.5  336.15  5873.3  336.37
#Mann= 7 ,-1 , 0
  4348.2     .05       0  4932.3     .07       0    4968     .05       0
  4972.1     .07       0  5028.6     .05       0  5317.6    .035       0
  5444.2    .045       0
Bank Sta=4968,4972.1
XS Rating Curve= 0 ,0
Exp/Cntr=0.3,0.1

Type RM Length L Ch R = 1 ,44721   ,448,448,448
BEGIN DESCRIPTION:
WEST BRUSHY CREEK 75.0
END DESCRIPTION:
XS GIS Cut Line= 3
      2429974.96     13701574.99        2429275.       13701475.
      2428475.03     13702124.97
#Sta/Elev= 30
  4300.5   332.4  4512.6  327.77  4765.1  319.42  4825.7  318.53  4835.8  319.55
    4941  317.56  5027.1  316.87  5027.3  316.37  5031.2  316.87  5154.1  318.11
  5299.2  319.49  5363.1  321.22  5391.9  321.11  5406.2  322.02    5437  321.74
  5476.6  321.75    5598  323.96    5626  325.48    5662  325.64  5697.1  328.05
    5718  327.54  5789.8  331.28  5818.6  331.48  5845.8  333.83  5868.1  333.55
  5896.6  336.17  5924.1  336.07  5952.9  338.05  5973.9  337.99  6038.3  340.33
#Mann= 6 ,-1 , 0
  4300.5     .05       0    4941    .045       0  5027.1    .045       0
  5031.2    .045       0  5154.1    .035       0    5437    .045       0
Bank Sta=5027.1,5031.2
XS Rating Curve= 0 ,0
Exp/Cntr=0.3,0.1

Type RM Length L Ch R = 1 ,44273   ,474,474,474
BEGIN DESCRIPTION:
WEST BRUSHY CREEK 74.0
END DESCRIPTION:
XS GIS Cut Line= 3
      2429875.04     13701425.02        2429325.       13701075.
      2428525.03     13701874.97
#Sta/Elev= 30
  4348.6  330.53  4419.8  329.35  4450.2  326.89  4492.6  326.86  4559.5  325.59
  4632.3   322.8  4638.2  323.41  4668.7  322.12  4868.4  317.43  4905.7  316.23
  4971.8  315.61  4997.6  314.38  5026.7  314.35    5027  313.85  5030.9  314.35
  5071.3  315.88  5170.3  316.39  5198.6  315.84  5212.7  314.83  5297.6  317.65
  5504.9  319.75  5631.3  321.23  5820.8  323.53  5863.2  325.38  5877.4  325.07
  5962.2  328.04  6018.8  328.99  6061.2  331.02  6089.5   331.3  6131.9  333.46
#Mann= 6 ,-1 , 0
  4348.6     .05       0  4868.4    .045       0  5026.7    .045       0
  5030.9    .045       0  5504.9    .035       0  5631.3    .045       0
Bank Sta=5026.7,5030.9
XS Rating Curve= 0 ,0
Exp/Cntr=0.3,0.1

Type RM Length L Ch R = 1 ,43799   ,383,383,383
BEGIN DESCRIPTION:
WEST BRUSHY CREEK 73.0
END DESCRIPTION:
XS GIS Cut Line= 3
      2430274.97     13700924.99        2429075.       13700725.
      2428275.02     13701224.99
#Sta/Elev= 30
  3787.4  331.54  3797.5  331.77  3807.6  334.99  3815.2  336.24  3822.7  335.56
  3838.1  330.96  3848.2   329.6  3936.9  326.14    3980   326.1  4101.6  322.61
  4301.9  323.45  4504.6  320.01  4732.7  315.65  4902.5  314.18  4953.2   314.6
  4981.5   313.3  4981.8   312.8  4985.8   313.3  5127.2   314.7  5163.7  316.13
  5371.1  318.91  5489.3  320.27    5547  320.79    5570  322.39  5614.2  322.44
  5650.7  324.35  5693.2  324.49  5735.6  326.91  5781.6  327.45  5947.3  332.85
#Mann= 7 ,-1 , 0
  3787.4     .07       0  3822.7     .05       0  4504.6    .045       0
  4981.5    .045       0  4985.8    .045       0  5371.1    .035       0
  5489.3    .045       0
Bank Sta=4981.5,4985.8
XS Rating Curve= 0 ,0
Exp/Cntr=0.3,0.1

Type RM Length L Ch R = 1 ,43416   ,544,544,544
BEGIN DESCRIPTION:
H21612
END DESCRIPTION:
XS GIS Cut Line= 3
      2430228.19     13700422.88      2429019.85     13700367.32
       2428103.2      13700457.6
#Sta/Elev= 30
  3945.8  329.36  4109.2  326.78  4159.2  325.03  4249.3   323.4  4269.3  322.37
  4510.1  318.33  4608.5  316.94  4759.8  315.16  4901.5  314.62  4960.1  313.91
  4977.9  312.71  4978.2  312.21    4982  312.21  4982.3  312.71  4990.1  313.44
  5020.1  313.34  5050.2  314.18  5190.4  313.38  5230.6  313.89  5250.7   314.9
  5285.3  314.73  5371.3  316.35  5431.6  316.09  5496.8  317.96  5515.4  318.44
  5622.5   321.2  5632.6  320.27  5743.1  321.05  5897.9  320.79  6076.5  322.04
#Mann= 8 ,-1 , 0
  3945.8     .05       0  4510.1    .045       0  4608.5     .07       0
  4901.5    .045       0  4977.9    .045       0  4982.3    .045       0
  5496.8    .035       0  5515.4    .045       0
Bank Sta=4977.9,4982.3
XS Rating Curve= 0 ,0
Exp/Cntr=0.3,0.1

Type RM Length L Ch R = 1 ,42872   ,464,464,464
BEGIN DESCRIPTION:
WEST BRUSHY CREEK 72.0
END DESCRIPTION:
XS GIS Cut Line= 3
      2430186.55     13700270.11        2429025.       13699975.
      2428130.92     13700193.72
#Sta/Elev= 30
  3810.2  328.11  3842.8  326.75  3854.7  326.99  3936.6  324.45  4139.6  321.18
  4171.9  320.04  4253.8  318.69  4335.7  318.17  4348.3  317.07  4397.9  317.01
  4542.8  315.68    4740  313.57    4827  313.24  4933.8  310.47  4934.2  309.97
  4938.7  309.97  4939.1  310.47  4944.7  311.21  4954.4  311.11  5011.2  311.01
  5026.9  313.76    5091  314.98  5328.6  317.35  5487.4  318.24  5523.4  318.08
    5544  318.86  5554.3  317.99  5595.5  319.42  5698.1  318.92  5929.1  320.01
#Mann= 8 ,-1 , 0
  3810.2     .05       0  4139.6     .07       0  4397.9    .063       0
  4542.8    .045       0  4933.8     .05       0  4939.1    .045       0
  4954.4     .07       0  5487.4    .045       0
Bank Sta=4933.8,4939.1
XS Rating Curve= 0 ,0
Exp/Cntr=0.3,0.1

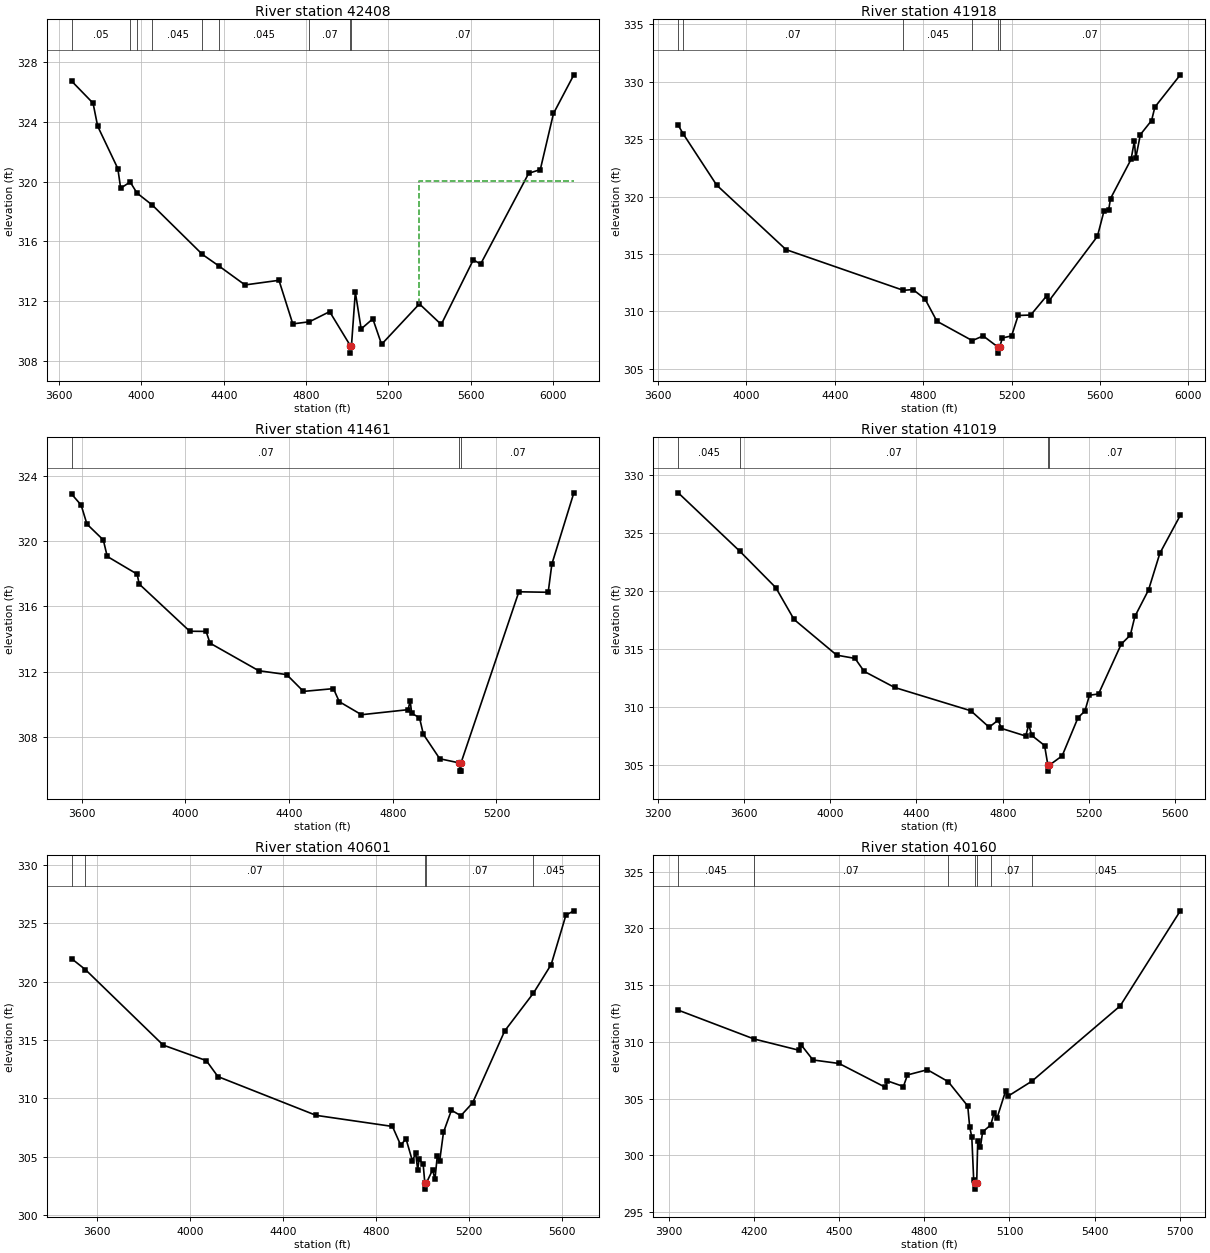
Type RM Length L Ch R = 1 ,42408   ,490,490,490
BEGIN DESCRIPTION:
WEST BRUSHY CREEK 71.0
END DESCRIPTION:
XS GIS Cut Line= 3
      2430124.96     13700174.98        2428925.       13699575.
      2428174.99     13698774.98
#Sta/Elev= 30
  3662.2  326.72  3765.6  325.25  3787.9  323.71  3885.8  320.87  3899.7  319.55
  3945.7  319.97  3978.8  319.23  4054.2  318.41  4296.9  315.11  4376.8  314.34
  4503.5  313.07  4668.4  313.38  4735.5  310.46  4816.1   310.6  4914.4  311.28
  5014.9     309  5015.4   308.5  5020.5     309  5039.2  312.59  5067.5  310.12
  5124.2   310.8  5166.7  309.09  5350.4   311.8  5456.4  310.42  5612.2  314.75
  5647.8  314.47  5881.1  320.55  5937.5   320.8  6001.5  324.56  6100.4  327.15
#Mann= 9 ,-1 , 0
  3662.2     .05       0  3945.7     .07       0  3978.8    .063       0
  4054.2    .045       0  4296.9     .07       0  4376.8    .045       0
  4816.1     .07       0  5014.9     .05       0  5020.5     .07       0
#XS Ineff= 2 , 0
       0                  5350.8       0  320.06
Permanent Ineff=
       F       F
Bank Sta=5014.9,5020.5
XS Rating Curve= 0 ,0
Exp/Cntr=0.3,0.1

Type RM Length L Ch R = 1 ,41918   ,457,457,457
BEGIN DESCRIPTION:
WEST BRUSHY CREEK 70.0
END DESCRIPTION:
XS GIS Cut Line= 3
      2430225.03     13699625.01        2429025.       13699125.
      2428224.96     13698574.98
#Sta/Elev= 30
  3692.1  326.22    3714  325.48    3866     321  4179.6  315.38  4710.7  311.83
  4753.8   311.9    4808  311.09  4862.1  309.14    5022  307.45  5071.3  307.86
  5140.1  306.86  5140.6  306.36  5145.8  306.86  5157.9  307.68  5199.8  307.86
  5229.6  309.64  5286.4  309.68  5358.1  311.34  5366.9  310.86  5588.1  316.54
  5617.9  318.75  5638.9  318.84  5647.4  319.83  5740.4  323.25  5755.3  324.85
  5761.3  323.34  5782.3   325.4  5833.1  326.63  5847.9   327.8    5963  330.61
#Mann= 6 ,-1 , 0
  3692.1    .045       0    3714     .07       0  4710.7    .045       0
    5022     .07       0  5140.1    .045       0  5145.8     .07       0
Bank Sta=5140.1,5145.8
XS Rating Curve= 0 ,0
Exp/Cntr=0.3,0.1

Type RM Length L Ch R = 1 ,41461   ,442,442,442
BEGIN DESCRIPTION:
WEST BRUSHY CREEK 69.0
END DESCRIPTION:
XS GIS Cut Line= 3
      2430125.04     13699525.02        2428925.       13698725.
      2428575.03     13698375.03
#Sta/Elev= 30
  3561.7  322.88  3597.8  322.22  3620.3  321.05  3683.4  320.08  3698.5  319.07
  3814.1  317.98  3821.6  317.38  4016.9  314.48    4080  314.47  4095.1  313.75
  4282.9  312.06    4391  311.82  4455.6  310.79  4571.3  310.96  4593.8  310.16
  4679.5  309.36  4859.7  309.67  4867.3  310.23  4873.3  309.44  4903.3  309.18
  4918.3  308.16  4981.4  306.66  5057.7   306.4  5058.1   305.9  5062.9   305.9
  5063.4   306.4  5286.8   316.9  5399.9  316.87  5414.1   318.6  5498.9  322.97
#Mann= 3 ,-1 , 0
  3561.7     .07       0  5057.7     .05       0  5063.4     .07       0
Bank Sta=5057.7,5063.4
XS Rating Curve= 0 ,0
Exp/Cntr=0.3,0.1

Type RM Length L Ch R = 1 ,41019   ,418,418,418
BEGIN DESCRIPTION:
WEST BRUSHY CREEK 68.0
END DESCRIPTION:
XS GIS Cut Line= 3
      2430374.97     13699574.97        2429175.       13698375.
      2428574.97     13698174.99
#Sta/Elev= 30
  3294.6  328.48  3579.2  323.46  3747.1   320.3    3832  317.55  4029.9  314.47
  4114.8  314.19  4157.2  313.07  4298.7  311.68  4652.2  309.67  4737.1  308.25
  4779.5  308.87  4793.6  308.15  4906.8  307.49  4920.9  308.47    4935  307.54
  4994.3  306.67  5009.8  304.96  5010.2  304.46  5015.6  304.96  5075.9  305.78
  5149.7  309.08  5181.4  309.64  5202.4  311.01  5244.6  311.12    5350  315.42
  5392.2   316.2  5413.3  317.81  5476.5  320.09  5529.2  323.26  5624.1  326.54
#Mann= 4 ,-1 , 0
  3294.6    .045       0  3579.2     .07       0  5009.8     .05       0
  5015.6     .07       0
Bank Sta=5009.8,5015.6
XS Rating Curve= 0 ,0
Exp/Cntr=0.3,0.1

Type RM Length L Ch R = 1 ,40601   ,441,441,441
BEGIN DESCRIPTION:
WEST BRUSHY CREEK 67.0
END DESCRIPTION:
XS GIS Cut Line= 3
      2430174.99     13699224.98        2429275.       13698025.
      2428625.03       13697925.
#Sta/Elev= 30
  3492.4  321.95  3550.7  321.03  3885.1  314.56  4070.5  313.23  4120.5  311.86
  4542.4  308.54  4870.5  307.59  4905.9  305.99  4928.8  306.53  4955.9  304.66
  4970.5  305.28  4978.8  303.88  4985.1  304.78  5002.5  304.35  5009.7  302.72
  5010.2  302.22  5015.5  302.72    5043  303.87  5053.1  303.06  5063.2  305.05
  5073.3  304.62  5089.8  307.09  5123.9  308.98  5164.4  308.51    5215  309.61
  5352.8  315.77  5476.3  319.01  5552.6  321.46  5615.9  325.69    5650  326.06
#Mann= 5 ,-1 , 0
  3492.4    .045       0  3550.7     .07       0  5009.7     .05       0
  5015.5     .07       0  5476.3    .045       0
Bank Sta=5009.7,5015.5
XS Rating Curve= 0 ,0
Exp/Cntr=0.3,0.1

Type RM Length L Ch R = 1 ,40160   ,436,436,436
BEGIN DESCRIPTION:
WEST BRUSHY CREEK 66.0
END DESCRIPTION:
XS GIS Cut Line= 3
      2430124.98     13698474.98        2429425.       13697675.
      2428724.99       13697775.
#Sta/Elev= 30
  3932.3  312.79  4199.4  310.25  4357.5  309.26  4364.6  309.76  4407.3   308.4
  4499.4  308.09  4662.6  305.99  4669.3  306.56  4726.2  306.06  4740.4  307.08
  4810.7  307.54  4884.1  306.49    4953  304.34  4959.7  302.52  4967.3   301.6
  4973.9  297.85  4978.6  297.52  4979.1  297.02  4984.5  297.52  4988.2  301.27
  4997.8  300.75  5005.4  302.06    5034  302.67  5045.8  303.72  5055.9  303.26
  5086.2  305.65  5096.3  305.23  5179.7  306.54  5490.3  313.16  5702.4  321.54
#Mann= 7 ,-1 , 0
  3932.3    .045       0  4199.4     .07       0  4884.1     .12       0
  4978.6     .05       0  4984.5     .12       0    5034     .07       0
  5179.7    .045       0
Bank Sta=4978.6,4984.5
XS Rating Curve= 0 ,0
Exp/Cntr=0.3,0.1

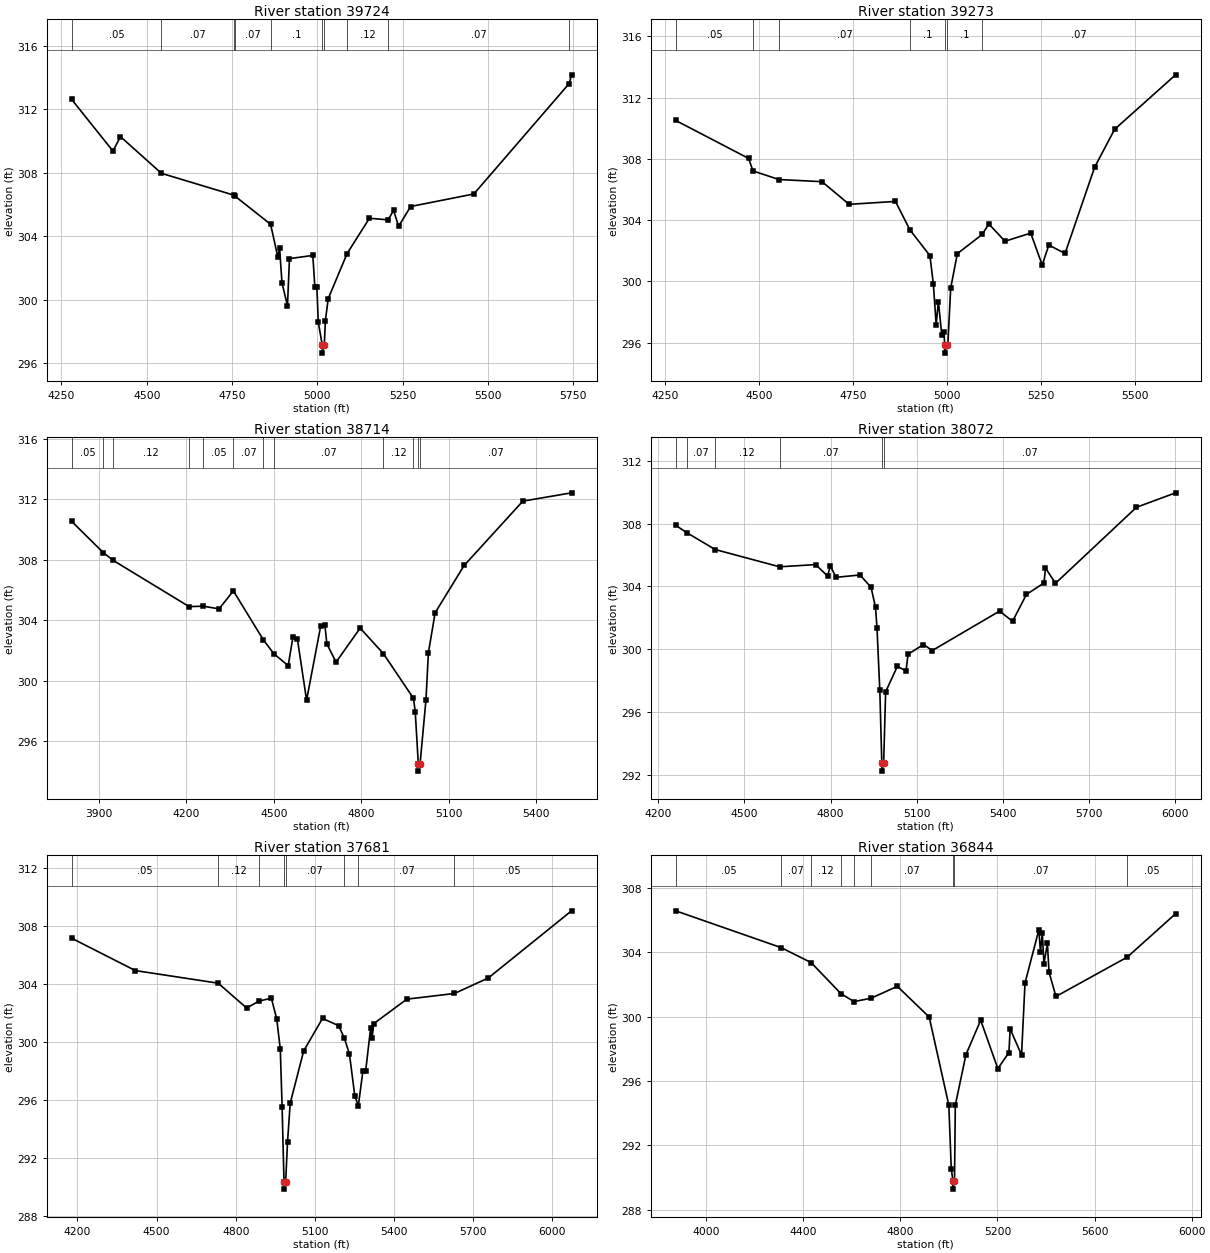
Type RM Length L Ch R = 1 ,39724   ,451,451,451
BEGIN DESCRIPTION:
WEST BRUSHY CREEK 65.0
END DESCRIPTION:
XS GIS Cut Line= 3
      2430374.96     13697774.98        2429725.       13697475.
      2429125.04     13697025.03
#Sta/Elev= 30
  4279.8  312.62  4400.9  309.37  4422.9  310.28    4543  307.97  4756.2  306.59
  4758.4  306.54  4863.2  304.76  4884.1  302.72  4889.6  303.24  4896.5  301.08
  4912.6  299.63  4918.5   302.6  4986.9   302.8  4992.9  300.83  4998.8  300.83
  5002.9  298.61  5014.6  297.15  5015.1  296.65  5020.5  297.15  5023.8   298.7
  5032.1  300.08  5087.5  302.92  5152.9  305.14  5207.9  305.04  5223.8  305.64
  5238.4  304.63  5273.8  305.88  5459.2  306.67  5738.6  313.62  5745.6  314.17
#Mann= 10 ,-1 , 0
  4279.8     .05       0    4543     .07       0  4756.2     .05       0
  4758.4     .07       0  4863.2      .1       0  5014.6     .05       0
  5020.5      .1       0  5087.5     .12       0  5207.9     .07       0
  5738.6    .045       0
Bank Sta=5014.6,5020.5
XS Rating Curve= 0 ,0
Exp/Cntr=0.3,0.1

Type RM Length L Ch R = 1 ,39273   ,559,559,559
BEGIN DESCRIPTION:
WEST BRUSHY CREEK 64.0
END DESCRIPTION:
XS GIS Cut Line= 3
        2430375.       13697475.        2429775.       13697075.
      2429174.99       13696975.
#Sta/Elev= 30
  4279.3  310.51  4473.1  308.03  4484.9  307.21  4553.9  306.65  4668.4  306.51
  4740.5  305.03  4863.7  305.22  4902.2  303.36  4955.3  301.68  4964.4  299.85
  4971.9  297.18  4977.9  298.68  4986.9  296.47  4992.9  296.72  4994.4  295.81
  4994.9  295.31  5000.5  295.81  5002.9  295.81  5010.6  299.56  5028.3  301.81
  5094.3  303.06  5111.9  303.75    5155  302.62  5223.4  303.15  5253.9  301.07
  5271.6  302.37  5314.7  301.82  5393.3  307.45  5446.5  309.93  5608.7  313.49
#Mann= 7 ,-1 , 0
  4279.3     .05       0  4484.9    .045       0  4553.9     .07       0
  4902.2      .1       0  4994.4     .05       0  5000.5      .1       0
  5094.3     .07       0
Bank Sta=4994.4,5000.5
XS Rating Curve= 0 ,0
Exp/Cntr=0.3,0.1

Type RM Length L Ch R = 1 ,38714   ,642,642,642
BEGIN DESCRIPTION:
H21611
END DESCRIPTION:
XS GIS Cut Line= 3
      2430783.72     13697027.04       2429589.3     13696624.27
        2429139.     13696672.76
#Sta/Elev= 30
  3807.1  310.53  3916.1  308.46  3949.9  307.95  4209.8   304.9  4258.5  304.93
  4312.3  304.75  4361.4  305.94  4464.3   302.7  4500.4  301.78  4549.3     301
  4565.6  302.89  4580.8  302.76  4612.3  298.72  4660.6  303.61  4675.2  303.67
  4681.7  302.45  4713.3  301.23  4795.9  303.48  4875.8  301.79  4978.7  298.84
  4984.8  297.95  4995.2  294.53  4995.7  294.03  5001.4  294.53  5021.5  298.74
  5029.9  301.86    5053   304.5  5152.4  307.62  5353.5  311.87  5520.5  312.42
#Mann= 12 ,-1 , 0
  3807.1     .05       0  3916.1     .07       0  3949.9     .12       0
  4209.8     .07       0  4258.5     .05       0  4361.4     .07       0
  4464.3     .12       0  4500.4     .07       0  4875.8     .12       0
  4978.7     .07       0  4995.2     .05       0  5001.4     .07       0
Bank Sta=4995.2,5001.4
XS Rating Curve= 0 ,0
Exp/Cntr=0.3,0.1

Type RM Length L Ch R = 1 ,38072   ,391,391,391
BEGIN DESCRIPTION:
H21610
END DESCRIPTION:
XS GIS Cut Line= 3
      2430894.87     13696561.77       2429839.3     13696374.27
      2429193.42     13696547.89
#Sta/Elev= 30
  4260.6  307.89  4298.5  307.43    4398  306.35  4622.3  305.25    4748  305.39
  4789.5  304.66  4798.8  305.31  4819.1  304.58  4902.5  304.73    4941  303.94
  4956.5  302.66  4961.6  301.36  4971.4  297.38  4978.4  292.74  4978.9  292.24
  4984.7  292.74  4991.7  297.29  5032.4  298.91  5062.8  298.62  5069.6  299.68
  5123.5   300.3  5154.2  299.92  5388.5  302.43  5433.7  301.78  5482.1  303.49
  5543.2  304.22  5548.4  305.17  5583.2   304.2  5865.3  309.04  6001.5  309.96
#Mann= 6 ,-1 , 0
  4260.6     .05       0  4298.5     .07       0    4398     .12       0
  4622.3     .07       0  4978.4     .05       0  4984.7     .07       0
Bank Sta=4978.4,4984.7
XS Rating Curve= 0 ,0
Exp/Cntr=0.3,0.1

Type RM Length L Ch R = 1 ,37681   ,837,837,837
BEGIN DESCRIPTION:
H21609
END DESCRIPTION:
XS GIS Cut Line= 4
      2430894.87     13696395.11      2430311.52     13696047.88
      2429769.85     13696158.99      2429188.27     13696477.48
#Sta/Elev= 30
    4178  307.17  4419.5  304.94  4733.5  304.07  4841.2  302.36  4887.7  302.83
    4935  303.04  4955.4   301.6  4968.8  299.53  4975.8  295.53  4982.9  290.37
  4983.4  289.87  4989.2  290.37  4996.2  293.09  5006.4  295.79  5057.5   299.4
  5128.9  301.64  5190.2  301.14  5211.8  300.27    5231  299.18  5251.4  296.29
  5264.8  295.62  5282.1  298.04  5292.3  297.99  5311.5     301  5316.6  300.27
  5322.9  301.28  5448.7  302.97    5629  303.36  5757.4  304.43  6072.9  309.06
#Mann= 8 ,-1 , 0
    4178     .05       0  4733.5     .12       0  4887.7     .07       0
  4982.9     .05       0  4989.2     .07       0  5211.8     .12       0
  5264.8     .07       0    5629     .05       0
Bank Sta=4982.9,4989.2
XS Rating Curve= 0 ,0
Exp/Cntr=0.3,0.1

Type RM Length L Ch R = 1 ,36844   ,268,268,268
BEGIN DESCRIPTION:
H21608
END DESCRIPTION:
XS GIS Cut Line= 4
      2430818.43     13696270.07      2430186.52     13695763.16
      2429582.35     13695846.49      2429166.82     13696331.28
#Sta/Elev= 30
  3875.4  306.59  4309.5   304.3  4432.9  303.37  4556.2  301.43  4609.6  300.94
  4679.6  301.15    4788  301.89  4919.2  299.98    5000   294.5  5010.1  290.55
    5017  289.77  5017.5  289.27  5023.4  289.77  5026.8   294.5  5070.6  297.64
  5131.2  299.78  5201.9  296.77  5247.6  297.77  5252.6  299.24  5299.5  297.62
  5313.8   302.1  5370.9  305.41  5377.4  304.03  5385.1  305.21  5391.7   303.3
    5406  304.56  5412.6  302.78  5441.1  301.26    5735  303.71  5933.9  306.41
#Mann= 9 ,-1 , 0
  3875.4     .05       0  4309.5     .07       0  4432.9     .12       0
  4556.2     .07       0  4609.6     .12       0  4679.6     .07       0
    5017     .05       0  5023.4     .07       0    5735     .05       0
Bank Sta=5017,5023.4
XS Rating Curve= 0 ,0
Exp/Cntr=0.3,0.1

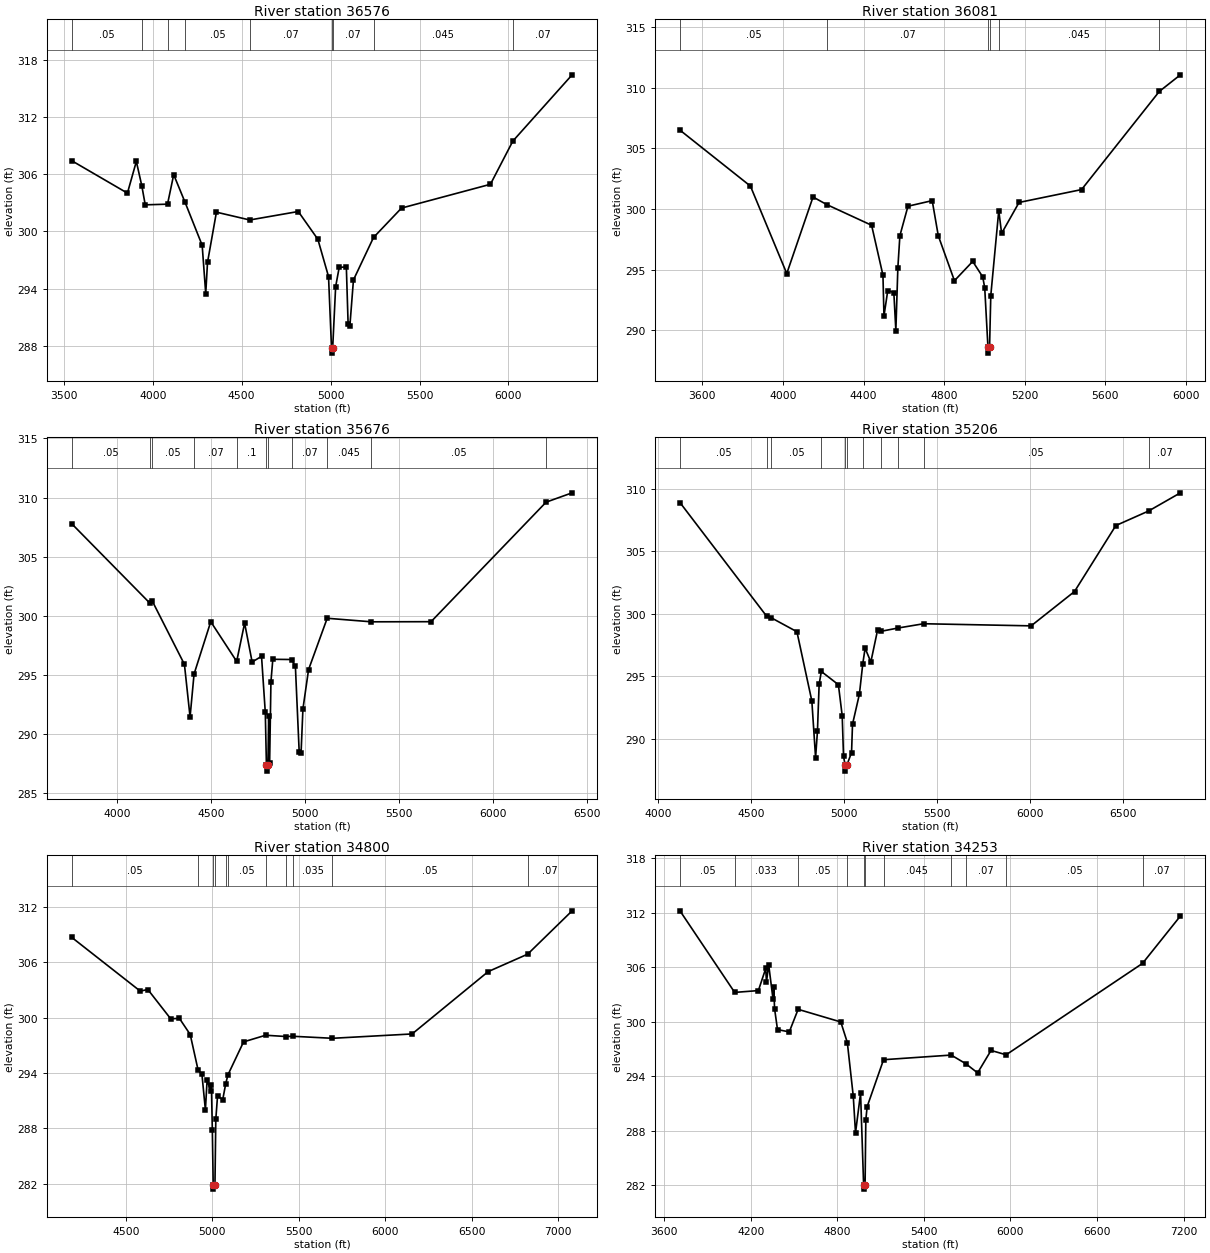
Type RM Length L Ch R = 1 ,36576   ,495,495,495
BEGIN DESCRIPTION:
H21607
END DESCRIPTION:
XS GIS Cut Line= 3
      2431228.23      13695520.1      2429325.41     13695589.54
      2428415.73      13695582.6
#Sta/Elev= 30
  3544.3  307.43  3857.7  304.02  3907.8  307.35  3938.6  304.79  3957.8  302.79
  4083.1  302.86  4117.9  305.96  4181.7  303.06    4278  298.54    4298  293.46
    4308  296.74  4358.1  302.02  4545.5   301.2  4818.4  302.09  4928.5  299.17
  4988.5  295.25  5005.3  287.71  5005.8  287.21  5011.7  287.71  5028.5   294.2
  5048.5  296.22  5088.6  296.27  5098.6  290.26  5108.6   290.1  5128.6   294.9
  5241.4  299.36  5398.8  302.45  5898.8  304.95  6024.9  309.49  6358.1  316.45
#Mann= 9 ,-1 , 0
  3544.3     .05       0  3938.6     .15       0  4083.1     .07       0
  4181.7     .05       0  4545.5     .07       0  5005.3     .05       0
  5011.7     .07       0  5241.4    .045       0  6024.9     .07       0
Bank Sta=5005.3,5011.7
XS Rating Curve= 0 ,0
Exp/Cntr=0.3,0.1

Type RM Length L Ch R = 1 ,36081   ,405,405,405
BEGIN DESCRIPTION:
H21606
END DESCRIPTION:
XS GIS Cut Line= 3
      2431033.78     13695131.21      2429408.74     13695242.32
      2428554.53     13695263.16
#Sta/Elev= 30
  3488.9  306.51  3838.5   301.9  4018.9  294.69  4149.2     301    4218  300.37
  4439.9  298.67  4496.2  294.55  4501.2  291.19  4520.1  293.29  4550.2  293.12
  4560.2  289.99  4570.2  295.18  4580.2  297.81  4620.3  300.24  4740.6   300.7
  4770.7  297.81  4850.9   294.1  4941.6  295.69  4991.2  294.42  5001.2  293.52
  5017.2  288.63  5017.7  288.13  5025.2  288.63  5031.3  292.88  5070.9  299.88
    5085     298  5171.5  300.55  5481.6  301.61  5867.5   309.7  5972.2  311.07
#Mann= 6 ,-1 , 0
  3488.9     .05       0    4218     .07       0  5017.2     .05       0
  5025.2     .07       0  5070.9    .045       0  5867.5     .05       0
Bank Sta=5017.2,5025.2
XS Rating Curve= 0 ,0
Exp/Cntr=0.3,0.1

Type RM Length L Ch R = 1 ,35676   ,470,470,470
BEGIN DESCRIPTION:
H21605
END DESCRIPTION:
XS GIS Cut Line= 3
      2430964.34     13694915.93      2429408.74     13694936.77
      2428304.57     13694978.43
#Sta/Elev= 30
  3760.2  307.79  4175.2  301.08  4188.5  301.25  4359.6  295.89  4389.6  291.44
  4410.8  295.07  4499.6   299.5  4637.4  296.14  4679.6  299.38  4719.6  296.09
  4769.6  296.57  4789.6  291.82  4795.6  287.36  4796.1  286.86  4803.6  287.36
  4807.6  291.51  4812.6  287.54  4819.6  294.43  4829.6  296.32  4929.3   296.3
  4949.6  295.72  4969.7  288.51  4979.7  288.38  4989.7  292.13  5019.7  295.45
  5118.7  299.79  5353.4  299.49  5670.9   299.5  6282.5  309.61  6420.9   310.4
#Mann= 11 ,-1 , 0
  3760.2     .05       0  4175.2     .07       0  4188.5     .05       0
  4410.8     .07       0  4637.4      .1       0  4795.6     .05       0
  4803.6      .1       0  4929.3     .07       0  5118.7    .045       0
  5353.4     .05       0  6282.5     .07       0
Bank Sta=4795.6,4803.6
XS Rating Curve= 0 ,0
Exp/Cntr=0.3,0.1

Type RM Length L Ch R = 1 ,35206   ,406,406,406
BEGIN DESCRIPTION:
H21604
END DESCRIPTION:
XS GIS Cut Line= 4
      2430901.77     13694679.82       2430151.8     13694728.43
      2429783.74      13694645.1      2428242.09     13694874.26
#Sta/Elev= 30
  4118.5  308.91    4585  299.79  4609.5  299.68  4746.6  298.57  4826.7  293.03
  4846.8  288.49  4856.8  290.59  4865.9  294.36  4877.6  295.39  4969.3  294.33
  4989.8  291.84  4996.9  288.59  5005.3  287.91  5005.8  287.41  5015.3  287.91
    5040   288.9  5045.1  291.16  5082.1  293.57  5100.4  296.02  5112.8  297.25
  5143.6  296.15  5179.7   298.7  5200.6  298.61    5287  298.86  5427.2  299.21
  6004.4  299.04  6237.4  301.79  6459.3  307.07  6635.9  308.24    6806  309.69
#Mann= 11 ,-1 , 0
  4118.5     .05       0    4585     .07       0  4609.5     .05       0
  4877.6      .1       0  5005.3     .05       0  5015.3      .1       0
  5100.4     .07       0  5200.6     .05       0    5287    .035       0
  5427.2     .05       0  6635.9     .07       0
Bank Sta=5005.3,5015.3
XS Rating Curve= 0 ,0
Exp/Cntr=0.3,0.1

Type RM Length L Ch R = 1 ,34800   ,547,547,547
BEGIN DESCRIPTION:
H21603
END DESCRIPTION:
XS GIS Cut Line= 4
        2430881.     13694534.01      2430443.46     13694304.82
      2429408.74     13694388.16      2428118.54     13694825.16
#Sta/Elev= 30
  4186.6  308.68    4583  302.86  4627.1  303.03  4759.2  299.86  4809.4  299.91
  4872.1  298.16  4917.9  294.29  4939.8  293.87  4959.9  289.99  4969.9  293.26
  4989.6  292.08  4994.6   292.7    5000  287.85    5005  281.92  5005.5  281.42
  5015.2  281.92  5020.1  288.98  5030.1   291.5  5060.2  291.12  5077.6  292.84
    5090  293.78  5180.6  297.36    5308  298.08  5427.6  297.94  5464.2  297.97
  5694.8  297.75  6155.4  298.22  6595.4  304.97  6823.8  306.86  7080.8  311.55
#Mann= 11 ,-1 , 0
  4186.6     .05       0  4917.9      .1       0    5005     .05       0
  5015.2      .1       0  5077.6     .07       0    5090     .05       0
    5308    .035       0  5427.6     .05       0  5464.2    .035       0
  5694.8     .05       0  6823.8     .07       0
Bank Sta=5005,5015.2
XS Rating Curve= 0 ,0
Exp/Cntr=0.3,0.1

Type RM Length L Ch R = 1 ,34253   ,566,566,566
BEGIN DESCRIPTION:
H21602
END DESCRIPTION:
XS GIS Cut Line= 3
      2431297.64     13693610.38      2429353.19     13694006.21
       2428075.4     13694763.16
#Sta/Elev= 30
  3708.6   312.2  4087.9  303.23  4252.2  303.43  4303.2  305.86  4308.3  304.38
  4323.6  306.28  4353.8  302.48  4358.9   303.8  4364.4  301.45  4384.8  299.14
  4466.5  298.89  4527.8  301.37  4823.6  299.98  4868.9  297.72  4910.1  291.82
  4925.7  287.78  4960.7  292.15  4981.8   282.1  4982.3   281.6    4992   282.1
  4997.1  289.19  5006.2  290.66    5120  295.83  5589.2  296.34  5690.2  295.39
  5772.2  294.38  5865.2  296.85  5969.9  296.37  6915.5  306.42  7178.1  311.63
#Mann= 11 ,-1 , 0
  3708.6     .05       0  4087.9    .033       0  4527.8     .05       0
  4868.9      .1       0  4981.8     .05       0    4992      .1       0
    5120    .045       0  5589.2     .05       0  5690.2     .07       0
  5969.9     .05       0  6915.5     .07       0
Bank Sta=4981.8,4992
XS Rating Curve= 0 ,0
Exp/Cntr=0.3,0.1

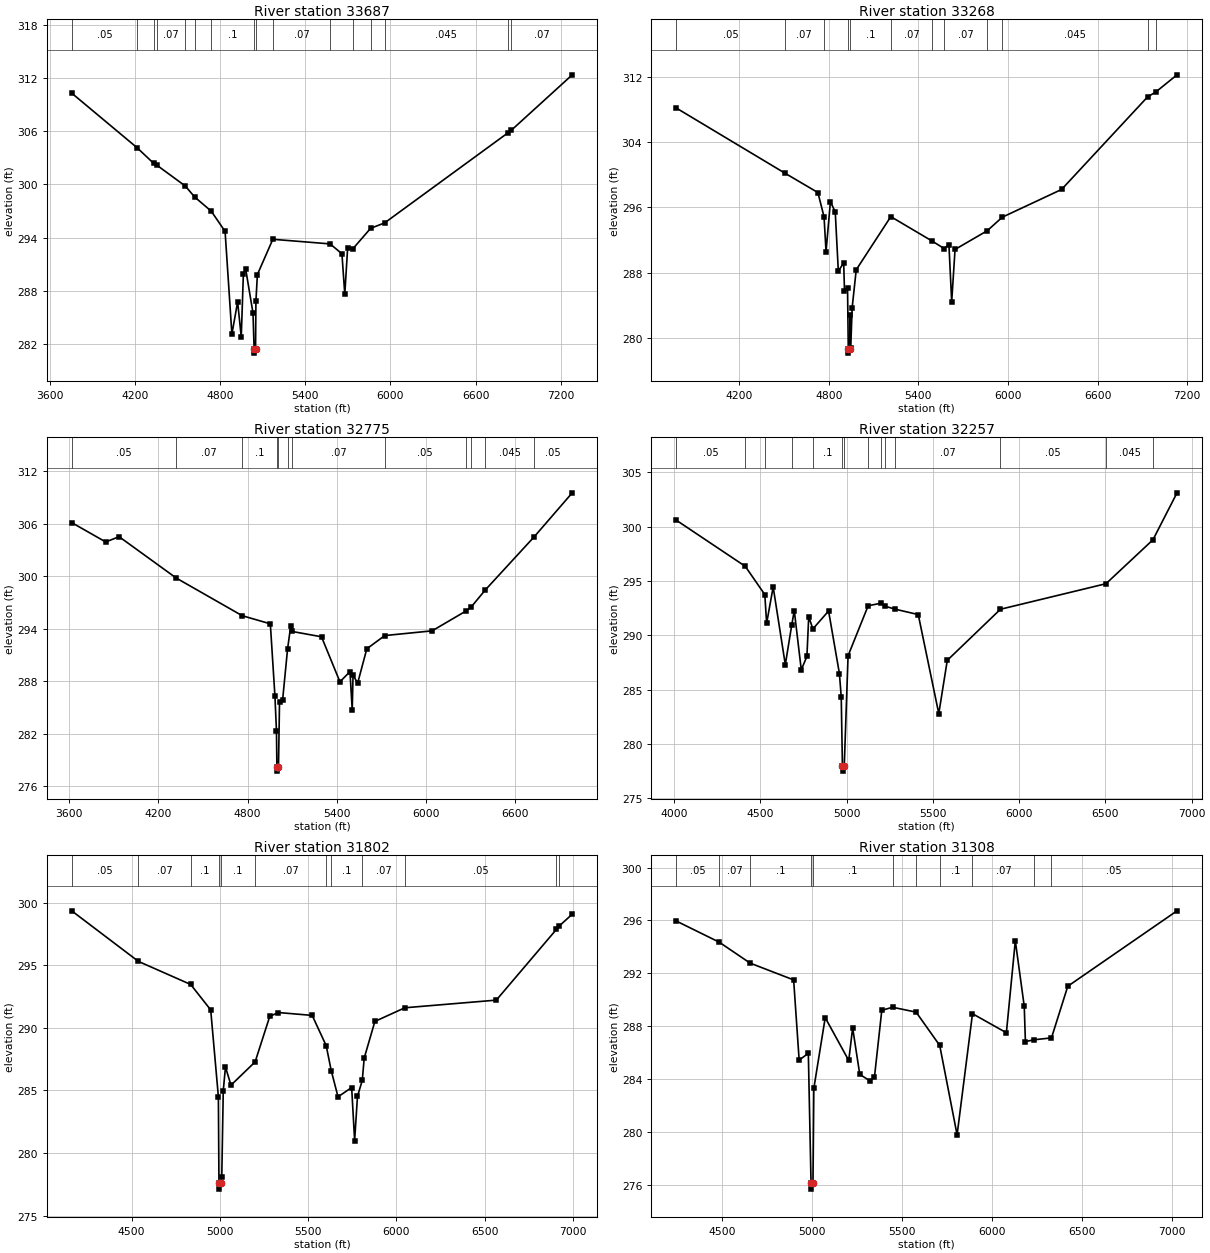
Type RM Length L Ch R = 1 ,33687   ,419,419,419
BEGIN DESCRIPTION:
H21601
END DESCRIPTION:
XS GIS Cut Line= 3
      2431019.88     13693103.43      2429325.41     13693547.88
      2427561.52     13693728.43
#Sta/Elev= 30
  3755.7  310.29  4215.5  304.15  4332.3  302.39  4356.5  302.16  4555.7  299.83
  4621.7  298.59  4738.2     297  4835.9  294.72  4883.8  283.15  4924.2  286.78
  4949.7  282.84  4964.6  289.87  4980.7   290.5  5032.4  285.53  5040.3  281.51
  5040.8  281.01  5050.5  281.51    5053  286.85  5063.4  289.86  5172.1  293.83
  5575.5  293.31  5658.7   292.2  5678.8  287.64  5698.9  292.85  5736.9  292.78
  5860.5  295.06  5959.7  295.68  6828.1  305.82  6851.8  306.11  7280.6  312.35
#Mann= 16 ,-1 , 0
  3755.7     .05       0  4215.5     .07       0  4332.3     .05       0
  4356.5     .07       0  4555.7     .05       0  4621.7     .07       0
  4738.2      .1       0  5040.3     .05       0  5050.5      .1       0
  5172.1     .07       0  5575.5     .12       0  5736.9     .07       0
  5860.5     .05       0  5959.7    .045       0  6828.1     .05       0
  6851.8     .07       0
Bank Sta=5040.3,5050.5
XS Rating Curve= 0 ,0
Exp/Cntr=0.3,0.1

Type RM Length L Ch R = 1 ,33268   ,493,493,493
BEGIN DESCRIPTION:
H21600
END DESCRIPTION:
XS GIS Cut Line= 3
       2430908.7     13692797.89      2429033.74     13693249.27
      2427638.99     13693533.77
#Sta/Elev= 30
  3780.2  308.16    4504  300.22  4727.2  297.82  4768.4  294.84  4781.7  290.59
    4811  296.69  4843.4  295.45    4864  288.18    4900  289.22  4905.2  285.77
  4925.7  286.15  4930.7  278.65  4931.2  278.15  4941.3  278.65    4942  282.83
  4947.1  278.77  4956.6  283.71  4983.9  288.36  5215.4  294.87  5490.9  291.89
  5572.9  290.96  5604.6  291.45  5623.2  284.45  5645.7  290.85    5861  293.14
    5962   294.8  6359.2   298.2  6935.7  309.55  6988.1  310.11  7132.2  312.24
#Mann= 12 ,-1 , 0
  3780.2     .05       0    4504     .07       0  4768.4      .1       0
  4930.7     .05       0  4941.3      .1       0  5215.4     .07       0
  5490.9     .12       0  5572.9     .07       0    5861     .05       0
    5962    .045       0  6935.7     .07       0  6988.1     .05       0
Bank Sta=4930.7,4941.3
XS Rating Curve= 0 ,0
Exp/Cntr=0.3,0.1

Type RM Length L Ch R = 1 ,32775   ,518,518,518
BEGIN DESCRIPTION:
H21599
END DESCRIPTION:
XS GIS Cut Line= 3
      2430832.35     13692547.88      2429575.41     13692679.82
      2427533.75     13693186.76
#Sta/Elev= 30
  3616.1  306.12  3844.7  303.91  3935.2  304.51  4319.4  299.79  4763.1  295.49
  4952.5  294.56  4983.4  286.31  4993.7  282.33  4996.7  278.24  4997.2  277.74
  5007.4  278.24  5014.3  285.63  5034.9  285.83  5068.3  291.67  5089.9  294.35
  5098.8  293.69  5296.7  293.08  5420.7  287.94  5488.3   289.1  5503.4  284.71
  5508.9  288.73  5539.6  287.77  5601.6  291.71  5722.3  293.22  6041.1  293.76
  6266.3     296  6302.2  296.45  6397.7  298.41  6728.7  304.52  6983.6  309.52
#Mann= 12 ,-1 , 0
  3616.1     .05       0  4319.4     .07       0  4763.1      .1       0
  4996.7     .05       0  5007.4      .1       0  5068.3     .12       0
  5098.8     .07       0  5722.3     .05       0  6266.3    .045       0
  6302.2     .05       0  6397.7    .045       0  6728.7     .05       0
Bank Sta=4996.7,5007.4
XS Rating Curve= 0 ,0
Exp/Cntr=0.3,0.1

Type RM Length L Ch R = 1 ,32257   ,455,455,455
BEGIN DESCRIPTION:
H21598
END DESCRIPTION:
XS GIS Cut Line= 3
      2430367.11     13691984.67      2428485.13     13692568.02
      2427569.26     13692734.54
#Sta/Elev= 30
  4014.1  300.58  4412.8  296.35    4526  293.75  4536.6  291.11  4574.5  294.45
  4644.9   287.3  4681.7  290.91  4696.8  292.28  4737.4  286.83    4770  288.06
  4780.6  291.72  4804.7  290.59  4895.7  292.24  4958.5  286.48    4969  284.33
  4975.9  278.01  4976.4  277.51  4986.6  278.01  5008.6  288.12    5125  292.72
  5197.5  292.95  5225.3  292.67    5281  292.41  5415.4  291.91  5534.4   282.8
  5583.6   287.7  5891.8   292.4  6503.5  294.75  6775.7  298.79  6915.3  303.11
#Mann= 14 ,-1 , 0
  4014.1     .05       0  4412.8     .07       0    4526     .12       0
  4681.7     .07       0  4804.7      .1       0  4975.9     .05       0
  4986.6      .1       0    5125     .12       0  5197.5     .07       0
  5225.3     .12       0    5281     .07       0  5891.8     .05       0
  6503.5    .045       0  6775.7     .05       0
Bank Sta=4975.9,4986.6
XS Rating Curve= 0 ,0
Exp/Cntr=0.3,0.1

Type RM Length L Ch R = 1 ,31802   ,494,494,494
BEGIN DESCRIPTION:
H21597
END DESCRIPTION:
XS GIS Cut Line= 3
      2430228.19     13691609.68      2428512.91     13692130.52
      2427540.64     13692505.53
#Sta/Elev= 30
  4160.9  299.34    4539   295.3  4834.8  293.46  4948.1  291.43  4991.6   284.5
  4994.9  277.62  4995.4  277.12  5005.8  277.62  5010.8  278.07  5019.2  284.96
  5031.7  286.87    5063  285.42  5199.7  287.28  5282.5  290.91  5330.9  291.22
  5522.8  290.99  5602.3  288.57  5630.7  286.58  5669.2  284.49  5746.4  285.23
  5763.2  280.99  5779.3  284.52  5806.6  285.81  5817.4  287.58  5877.9  290.51
  6047.7   291.6  6565.5  292.21  6905.6  297.85  6923.4  298.15  6995.6  299.07
#Mann= 12 ,-1 , 0
  4160.9     .05       0    4539     .07       0  4834.8      .1       0
  4994.9     .05       0  5005.8      .1       0  5199.7     .07       0
  5602.3     .12       0  5630.7      .1       0  5806.6     .07       0
  6047.7     .05       0  6905.6    .045       0  6923.4     .05       0
Bank Sta=4994.9,5005.8
XS Rating Curve= 0 ,0
Exp/Cntr=0.3,0.1

Type RM Length L Ch R = 1 ,31308   ,770,770,770
BEGIN DESCRIPTION:
H21596
END DESCRIPTION:
XS GIS Cut Line= 3
      2430012.95     13691297.18       2428464.3     13691609.68
      2427526.76     13692359.71
#Sta/Elev= 30
  4247.6  295.94  4484.6  294.35  4656.8  292.76  4898.4  291.49    4929  285.42
    4980  285.93    4995  276.15  4995.5  275.65  5005.9  276.15  5010.6  283.28
  5073.8  288.63  5204.5  285.39  5226.2  287.85  5265.7  284.34  5322.6  283.84
  5347.3  284.13  5388.1  289.19    5448  289.42  5578.7  289.05  5709.8  286.53
  5806.4  279.76  5891.9  288.93  6080.2  287.49  6129.8  294.45  6179.4  289.49
  6185.8  286.82  6235.1  286.96  6330.7   287.1  6421.2  291.01  7028.1  296.72
#Mann= 11 ,-1 , 0
  4247.6     .05       0  4484.6     .07       0  4656.8      .1       0
    4995     .05       0  5005.9      .1       0    5448     .07       0
  5578.7     .12       0  5709.8      .1       0  5891.9     .07       0
  6235.1    .035       0  6330.7     .05       0
Bank Sta=4995,5005.9
XS Rating Curve= 0 ,0
Exp/Cntr=0.3,0.1