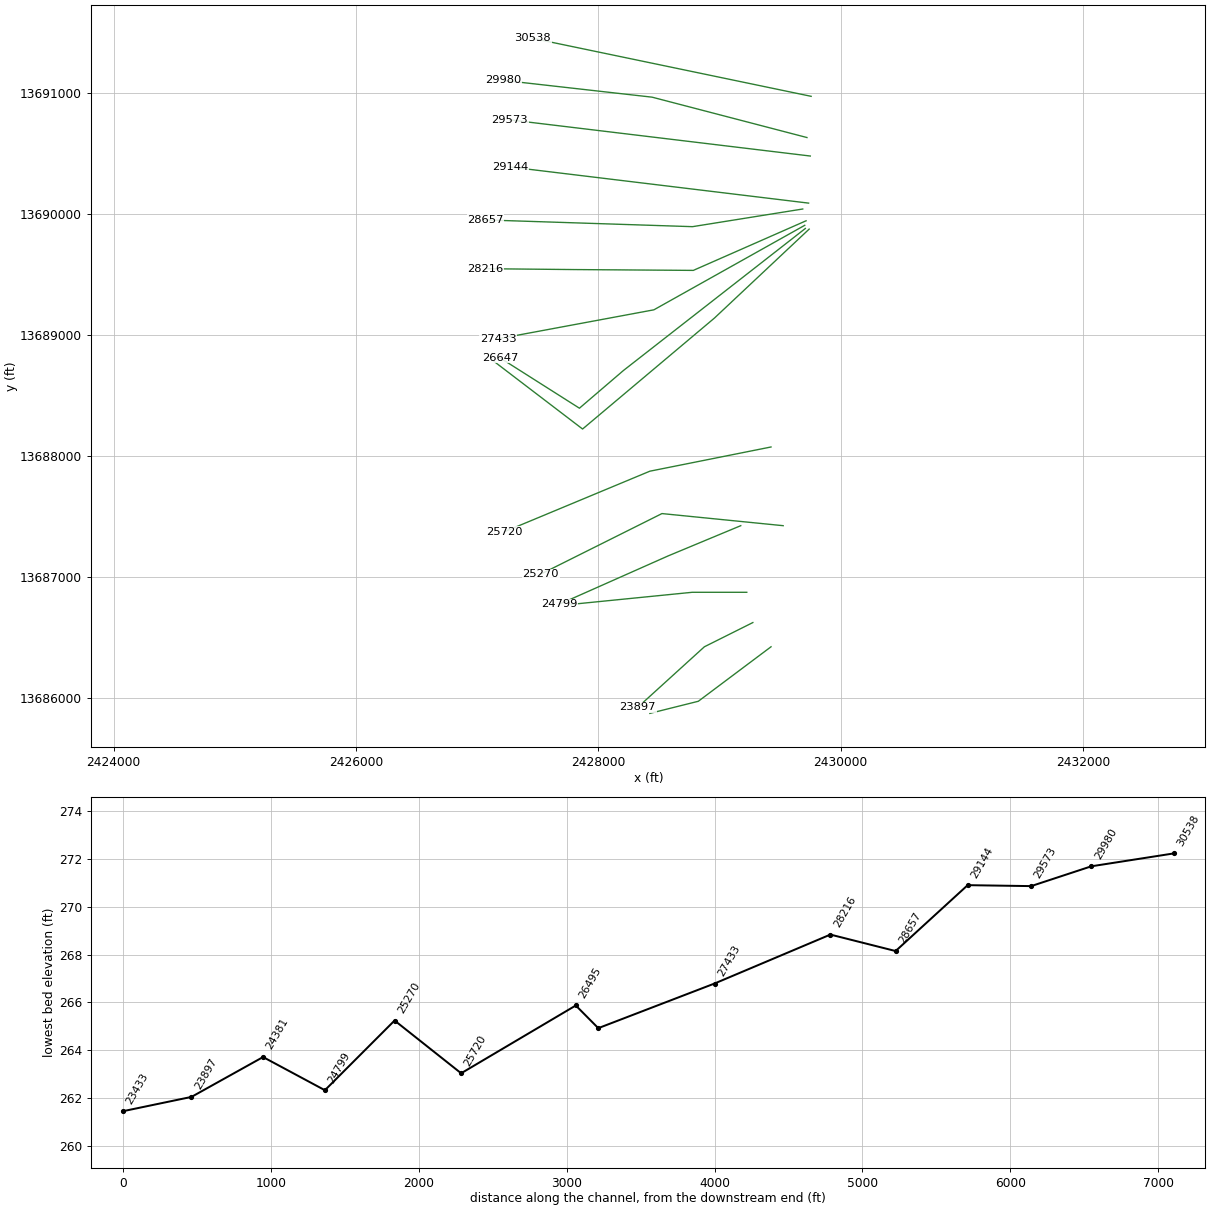
HEC-RAS study WEST BRUSHY CREEK.prj: WEST BRUSHY CREEK Base Level Engineering

--- WEST BRUSHY CREEK.g01 (geometry) --- (continued)

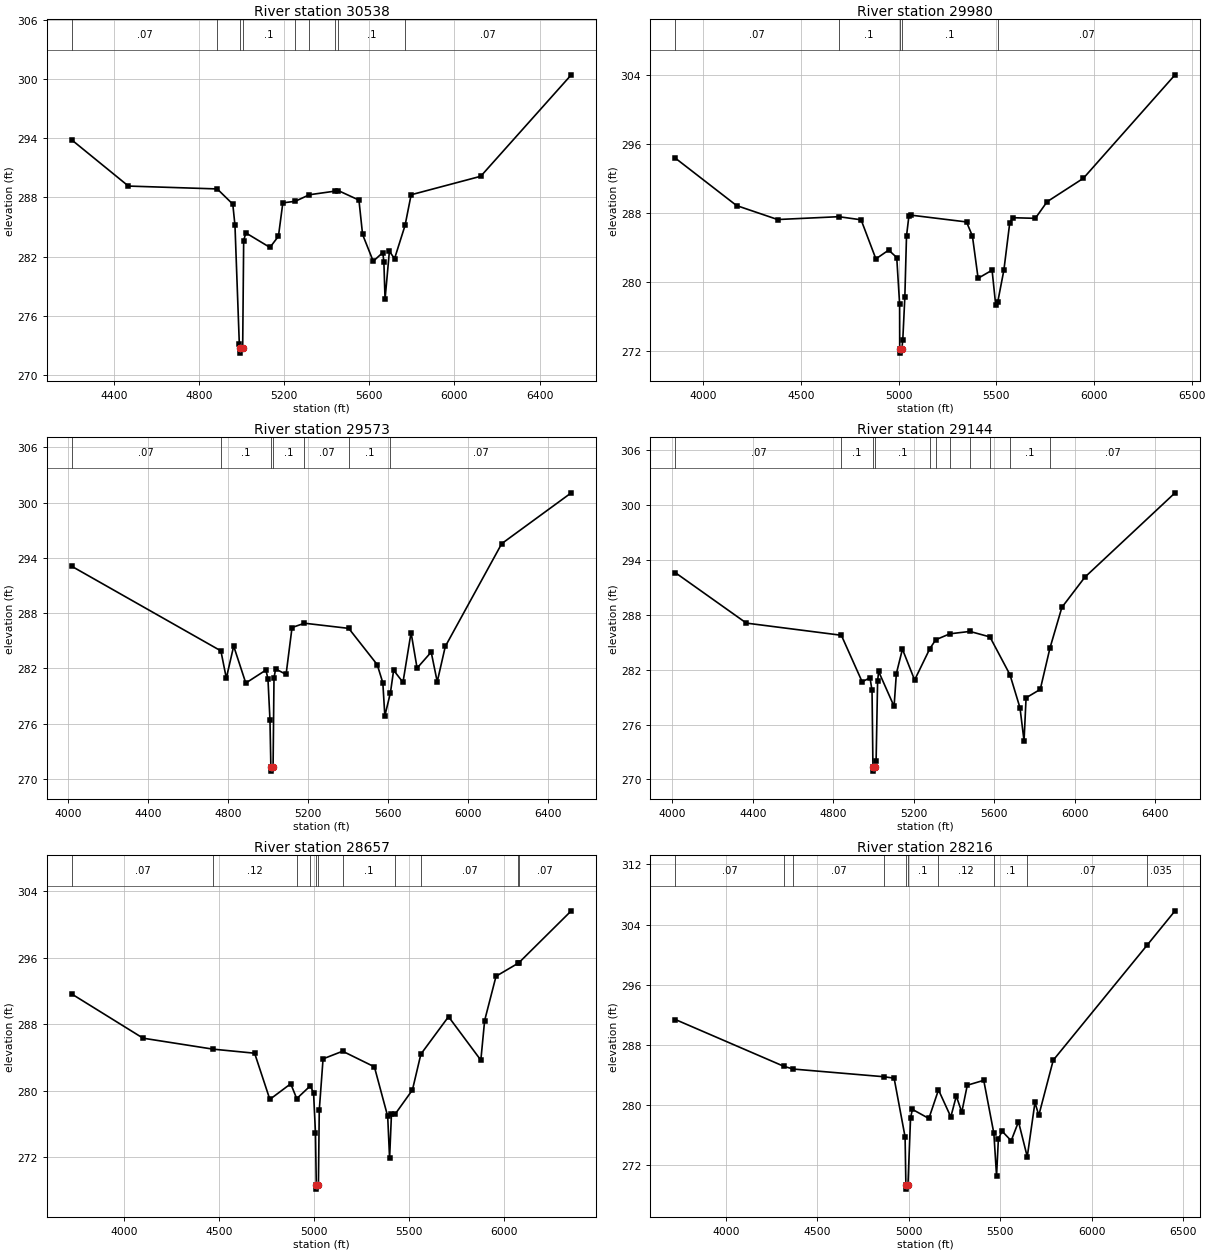
Type RM Length L Ch R = 1 ,30538   ,558,558,558
BEGIN DESCRIPTION:
H21595
END DESCRIPTION:
XS GIS Cut Line= 2
      2429755.99     13690970.79      2427458.67     13691449.69
#Sta/Elev= 30
  4202.4  293.83    4469  289.15  4886.2  288.86  4959.3  287.32  4969.5  285.17
    4990  273.14  4994.6  272.74  4995.1  272.24  5005.7  272.74  5010.4  283.64
  5020.6  284.41  5133.8  282.94  5173.7  284.07  5194.3  287.45  5252.9  287.61
  5318.5  288.27    5437  288.63  5453.9   288.7  5551.8  287.73  5568.9  284.25
  5618.9  281.54  5663.8  282.42  5668.9  281.46  5674.4  277.69  5694.8  282.55
    5719   281.8  5768.4  285.17  5796.9  288.27  6123.8  290.14  6549.1  300.41
#Mann= 9 ,-1 , 0
  4202.4     .07       0  4886.2      .1       0  4994.6     .05       0
  5005.7      .1       0  5252.9     .12       0  5318.5      .1       0
    5437     .07       0  5453.9      .1       0  5768.4     .07       0
Bank Sta=4994.6,5005.7
XS Rating Curve= 0 ,0
Exp/Cntr=0.3,0.1

Type RM Length L Ch R = 1 ,29980   ,407,407,407
BEGIN DESCRIPTION:
H21594
END DESCRIPTION:
XS GIS Cut Line= 3
      2429721.24     13690630.52      2428443.46     13690963.85
      2427214.33     13691102.74
#Sta/Elev= 30
  3857.5  294.33  4170.6  288.83  4380.7  287.21  4693.6  287.54  4807.9  287.18
  4883.7  282.64  4949.1  283.66  4990.4   282.8  5005.1   277.4  5005.6   272.2
  5006.1   271.7  5016.7   272.2  5021.4  273.27  5031.8  278.16  5040.4   285.3
  5052.4  287.57  5062.8  287.72  5347.6  286.93  5377.8  285.29  5406.9  280.39
  5478.4  281.33  5496.8  277.32  5507.5  277.65  5538.8  281.33    5569  286.85
  5586.6  287.42  5699.8  287.35  5760.2  289.28  5945.8     292    6415  304.01
#Mann= 5 ,-1 , 0
  3857.5     .07       0  4693.6      .1       0  5005.6     .05       0
  5016.7      .1       0  5507.5     .07       0
Bank Sta=5005.6,5016.7
XS Rating Curve= 0 ,0
Exp/Cntr=0.3,0.1

Type RM Length L Ch R = 1 ,29573   ,429,429,429
BEGIN DESCRIPTION:
H21593
END DESCRIPTION:
XS GIS Cut Line= 2
      2429749.01     13690477.74      2427269.93     13690776.34
#Sta/Elev= 30
  4019.1  293.09    4765  283.91  4792.1  280.95  4828.9  284.43  4889.4  280.42
  4990.1  281.83  5000.2  280.87  5010.2  276.45  5014.7  271.37  5015.2  270.87
  5025.8  271.37  5030.4  280.97  5038.4  281.95  5090.8  281.36  5120.5  286.44
  5182.6  286.91  5403.9  286.35  5546.2  282.42  5574.3  280.45  5584.3  276.86
  5612.2  279.36  5628.3  281.81    5675   280.5  5715.4   285.9  5745.5  282.04
    5816  283.78  5846.2  280.56  5886.5  284.39  6168.5  295.54  6516.1  301.05
#Mann= 7 ,-1 , 0
  4019.1     .07       0    4765      .1       0  5014.7     .05       0
  5025.8      .1       0  5182.6     .07       0  5403.9      .1       0
  5612.2     .07       0
Bank Sta=5014.7,5025.8
XS Rating Curve= 0 ,0
Exp/Cntr=0.3,0.1

Type RM Length L Ch R = 1 ,29144   ,487,487,487
BEGIN DESCRIPTION:
H21592
END DESCRIPTION:
XS GIS Cut Line= 2
      2429735.13     13690088.85      2427269.95     13690387.45
#Sta/Elev= 30
  4015.2  292.61  4367.9   287.1  4839.9  285.77  4943.3  280.68  4982.3  281.12
  4992.4  279.73  4996.9  271.41  4997.4  270.91    5008  271.41  5012.6  271.98
  5020.1  280.77  5025.2  281.81    5102  277.99  5113.3  281.58  5143.5  284.25
    5204  280.88  5279.8  284.31  5309.1  285.28  5379.3  285.93  5478.8  286.19
  5578.3  285.59  5677.8  281.46  5727.8  277.83  5747.9  274.21    5758  278.93
  5828.5  279.85  5876.8  284.38  5935.9  288.82  6050.1  292.12  6498.4  301.35
#Mann= 11 ,-1 , 0
  4015.2     .07       0  4839.9      .1       0  4996.9     .05       0
    5008      .1       0  5279.8     .12       0  5309.1     .07       0
  5379.3     .12       0  5478.8     .07       0  5578.3     .12       0
  5677.8      .1       0  5876.8     .07       0
Bank Sta=4996.9,5008
XS Rating Curve= 0 ,0
Exp/Cntr=0.3,0.1

Type RM Length L Ch R = 1 ,28657   ,441,441,441
BEGIN DESCRIPTION:
H21591
END DESCRIPTION:
XS GIS Cut Line= 3
       2429686.5     13690040.24       2428776.8     13689894.41
      2427069.22     13689949.94
#Sta/Elev= 30
    3726  291.66  4101.9  286.33    4470  285.01  4689.1  284.52  4769.2  278.96
  4879.2  280.84  4910.7  279.05  4981.9  280.58  4999.3  279.77  5009.3  274.96
  5013.7  268.65  5014.2  268.15  5024.9  268.65  5029.3  277.63  5049.3  283.84
  5152.3  284.76  5319.5  282.88  5389.5  276.92  5399.5  271.85  5409.5  277.25
  5427.7  277.15  5519.6  280.09  5564.2  284.41  5709.7  288.92  5879.8  283.68
  5899.8  288.46  5959.8  293.79  6074.8  295.34  6078.8  295.39  6355.8  301.67
#Mann= 11 ,-1 , 0
    3726     .07       0    4470     .12       0  4910.7      .1       0
  4981.9     .12       0  5013.7     .05       0  5024.9     .12       0
  5152.3      .1       0  5427.7     .12       0  5564.2     .07       0
  6074.8     .05       0  6078.8     .07       0
Bank Sta=5013.7,5024.9
XS Rating Curve= 0 ,0
Exp/Cntr=0.3,0.1

Type RM Length L Ch R = 1 ,28216   ,783,783,783
BEGIN DESCRIPTION:
H21590
END DESCRIPTION:
XS GIS Cut Line= 4
      2429714.28     13689943.01      2428783.74     13689533.29
      2427783.74     13689540.24      2427069.24     13689547.18
#Sta/Elev= 30
  3723.9  291.38  4317.1  285.16  4367.9   284.8  4862.8  283.78  4919.4  283.59
  4979.4  275.78  4983.8  269.34  4984.3  268.84    4995  269.34  5009.4  278.33
  5019.4  279.44  5109.4  278.23    5162  282.03  5229.4  278.44  5259.4  281.21
  5289.4  279.07  5319.4  282.65  5409.4   283.3  5464.7  276.26  5479.4   270.6
  5489.4  275.49  5509.4  276.55  5559.4  275.27  5599.4   277.8  5647.3  273.14
  5689.4  280.37  5710.3  278.64  5789.4  285.98  6304.3  301.32  6455.2  305.83
#Mann= 10 ,-1 , 0
  3723.9     .07       0  4317.1    .035       0  4367.9     .07       0
  4862.8      .1       0  4983.8     .05       0    4995      .1       0
    5162     .12       0  5464.7      .1       0  5647.3     .07       0
  6304.3    .035       0
Bank Sta=4983.8,4995
XS Rating Curve= 0 ,0
Exp/Cntr=0.3,0.1

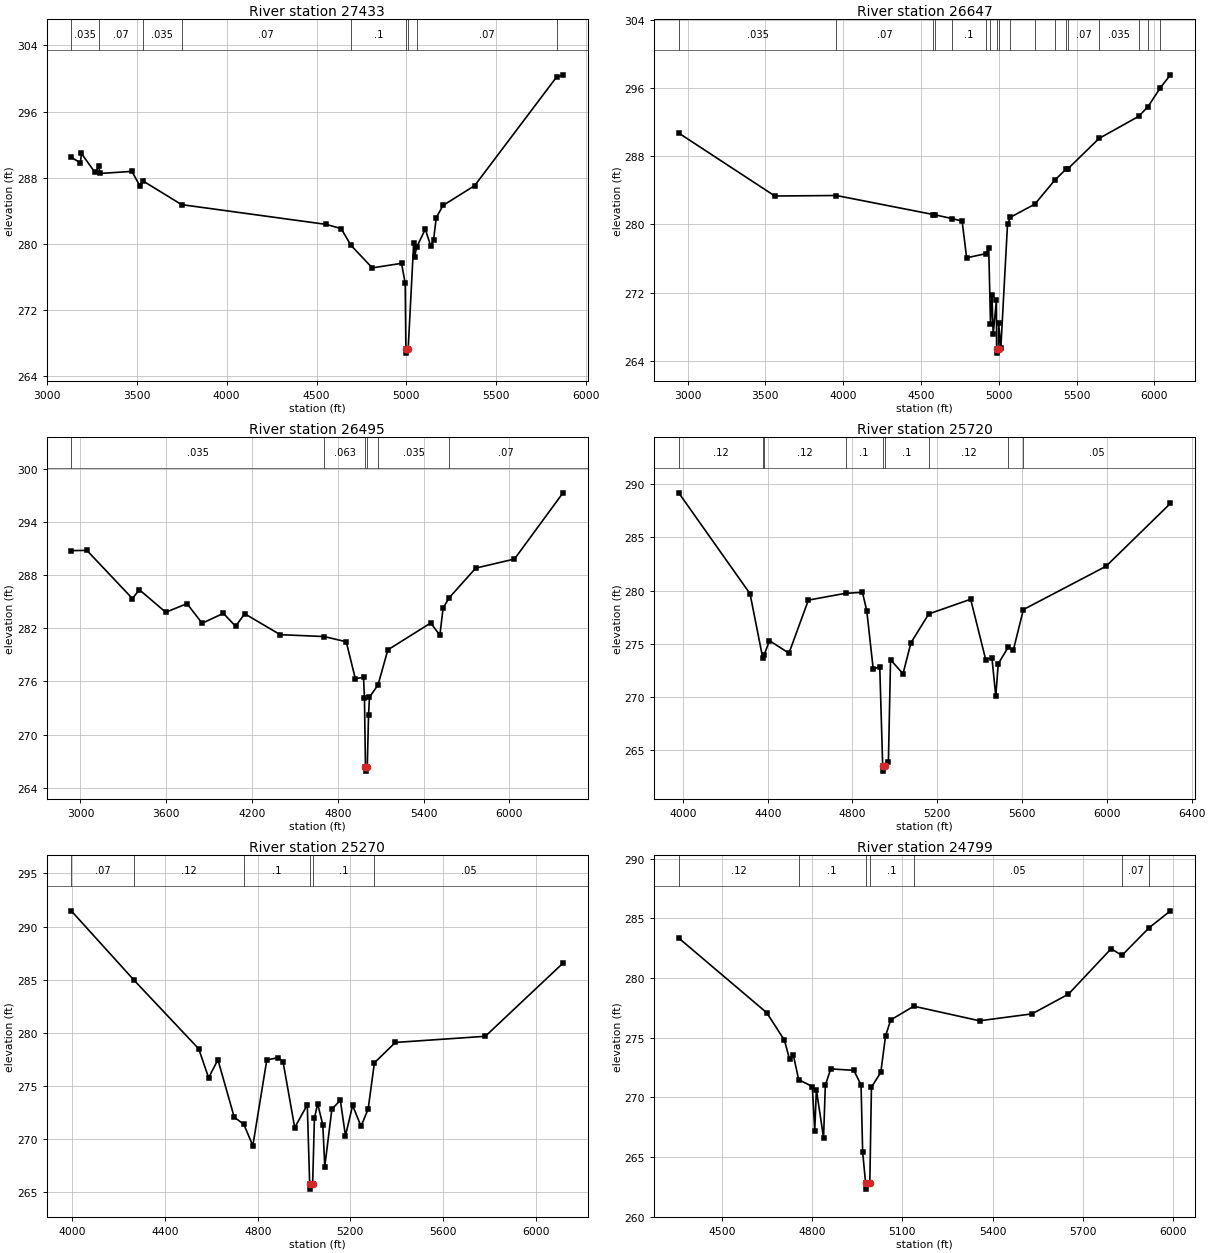
Type RM Length L Ch R = 1 ,27433   ,786,786,786
BEGIN DESCRIPTION:
WBC21676
END DESCRIPTION:
XS GIS Cut Line= 3
      2429703.18     13689905.62       2428458.4     13689207.71
       2427171.9     13688968.12
#Sta/Elev= 30
  3135.5  290.46  3186.4  289.82  3192.2  290.94  3267.5  288.64  3288.6  289.37
  3294.9  288.52  3472.9  288.77  3516.3  287.05  3533.4  287.63  3749.3  284.75
  4553.6  282.36  4637.2  281.85  4690.6  279.85  4810.2   277.1  4972.9  277.65
  4993.3  275.22  4997.1  267.29  4997.6  266.79  5009.8  267.29  5040.3  280.09
  5045.4  278.44  5057.3  279.62  5105.1  281.78  5135.7  279.72  5150.9  280.49
  5166.2  283.19  5203.6  284.65  5379.8  287.05  5835.2  300.18  5871.2  300.45
#Mann= 9 ,-1 , 0
  3135.5    .035       0  3288.6     .07       0  3533.4    .035       0
  3749.3     .07       0  4690.6      .1       0  4997.1     .05       0
  5009.8      .1       0  5057.3     .07       0  5835.2    .035       0
Bank Sta=4997.1,5009.8
XS Rating Curve= 0 ,0
Exp/Cntr=0.3,0.1

Type RM Length L Ch R = 1 ,26647   ,152,152,152
BEGIN DESCRIPTION:
WBC21677
END DESCRIPTION:
XS GIS Cut Line= 5
      2429708.37     13689879.57       2428208.4     13688707.71
      2427860.54     13688409.55      2427843.81     13688395.21
      2427187.56     13688811.88
#Sta/Elev= 30
  2942.9  290.71    3561  283.33    3956  283.39  4579.4  281.16  4591.6  281.12
  4699.3  280.69  4764.8  280.39  4793.7  276.09  4919.3  276.58  4935.7  277.24
  4947.1  268.38  4956.6  271.75  4964.3  267.15  4985.1  271.12  4986.4  265.42
  4986.9  264.92  4999.2  265.42  4999.4  268.42  5013.7  265.57  5056.5  280.02
  5074.8  280.84  5232.4  282.38  5359.4  285.17  5432.2  286.47  5445.4  286.53
  5645.3  290.08  5900.2  292.67  5959.5   293.8  6039.2  296.02  6103.9  297.53
#Mann= 18 ,-1 , 0
  2942.9    .035       0    3956     .07       0  4579.4      .1       0
  4591.6     .07       0  4699.3      .1       0  4919.3    .035       0
  4947.1      .1       0  4986.4     .05       0  4999.2      .1       0
  5074.8     .07       0  5232.4    .035       0  5359.4     .07       0
  5432.2    .035       0  5445.4     .07       0  5645.3    .035       0
  5900.2     .07       0  5959.5    .035       0  6039.2     .07       0
Bank Sta=4986.4,4999.2
XS Rating Curve= 0 ,0
Exp/Cntr=0.3,0.1

Type RM Length L Ch R = 1 ,26495   ,775,775,775
BEGIN DESCRIPTION:
WBC21678
END DESCRIPTION:
XS GIS Cut Line= 4
      2429739.66     13689874.39       2428958.4       13689140.
      2427869.85     13688223.34      2427119.95     13688796.18
#Sta/Elev= 30
  2935.8  290.74  3044.8  290.77  3363.2  285.34  3412.6  286.32  3596.7  283.79
  3745.2  284.76  3851.2  282.55  3999.6  283.67    4085  282.21  4148.8  283.62
  4397.2  281.26  4704.4  281.05  4858.8  280.46  4922.5  276.29  4979.7  276.45
  4986.3  274.07  4993.1  266.37  4993.6  265.87  5005.9  266.37  5014.9  272.23
  5021.4  274.21  5081.3   275.6  5149.9  279.55  5449.8  282.58  5513.5   281.2
  5536.3  284.26  5577.9  285.41  5764.4  288.77  6035.1  289.79  6374.8  297.26
#Mann= 6 ,-1 , 0
  2935.8    .035       0  4704.4    .063       0  4993.1    .063       0
  5005.9    .063       0  5081.3    .035       0  5577.9     .07       0
Bank Sta=4993.1,5005.9
XS Rating Curve= 0 ,0
Exp/Cntr=0.3,0.1

Type RM Length L Ch R = 1 ,25720   ,450,450,450
BEGIN DESCRIPTION:
WEST BRUSHY CREEK 39.0
END DESCRIPTION:
XS GIS Cut Line= 3
      2429424.96     13688074.99        2428425.       13687875.
      2427224.96     13687374.98
#Sta/Elev= 30
  3980.2  289.18  4316.7   279.7  4376.6  273.67  4382.4   273.9  4408.5  275.29
  4500.3  274.11    4592   279.1  4767.8  279.74    4847  279.83  4867.4  278.09
    4898  272.59  4928.6  272.86  4942.5  263.53    4943  263.03  4955.4  263.53
  4969.4  263.92  4979.6  273.49  5038.4  272.18  5075.8  275.09  5159.8   277.8
  5357.5  279.18  5428.4  273.51  5457.7  273.69  5476.1  270.05  5487.5  273.12
  5535.4   274.7  5558.4  274.37  5606.2  278.21  5996.1  282.28    6300  288.19
#Mann= 9 ,-1 , 0
  3980.2     .12       0  4376.6    .045       0  4382.4     .12       0
  4767.8      .1       0  4942.5     .05       0  4955.4      .1       0
  5159.8     .12       0  5535.4      .1       0  5606.2     .05       0
Bank Sta=4942.5,4955.4
XS Rating Curve= 0 ,0
Exp/Cntr=0.3,0.1

Type RM Length L Ch R = 1 ,25270   ,471,471,471
BEGIN DESCRIPTION:
WEST BRUSHY CREEK 38.0
END DESCRIPTION:
XS GIS Cut Line= 3
      2429525.05       13687425.        2428525.       13687525.
      2427524.97     13687024.99
#Sta/Elev= 30
    3995  291.48  4266.5  284.93  4545.3  278.47    4588  275.74  4628.2  277.44
  4698.5  272.03  4740.3  271.34  4778.9  269.33  4839.2  277.42  4889.5  277.64
  4909.6  277.22  4959.8  271.04    5014  273.19  5024.3  265.74  5024.8  265.24
  5037.2  265.74  5044.8   271.9  5058.7  273.29  5081.1  271.29  5089.5  267.37
  5120.2  272.78  5156.6  273.62  5178.9  270.27  5209.7  273.13    5246  271.17
  5276.7  272.78  5303.8  277.15  5394.1  279.07  5782.7  279.65  6118.1  286.55
#Mann= 6 ,-1 , 0
    3995     .07       0  4266.5     .12       0  4740.3      .1       0
  5024.3     .05       0  5037.2      .1       0  5303.8     .05       0
Bank Sta=5024.3,5037.2
XS Rating Curve= 0 ,0
Exp/Cntr=0.3,0.1

Type RM Length L Ch R = 1 ,24799   ,418,418,418
BEGIN DESCRIPTION:
WEST BRUSHY CREEK 37.0
END DESCRIPTION:
XS GIS Cut Line= 3
      2429175.04     13687425.01        2428575.       13687175.
      2427675.02     13686775.01
#Sta/Elev= 30
  4356.3  283.35  4648.8   277.1  4707.9  274.79  4724.7   273.2  4737.1  273.59
  4755.2  271.49  4800.5  270.91  4808.6   267.2    4814  270.65  4837.9  266.62
  4843.8  271.02  4861.7  272.39  4938.6  272.27  4962.5  271.04  4967.9  265.41
  4977.7  262.82  4978.2  262.32  4991.7  262.82  4997.1  270.86  5028.2   272.1
    5044  275.15  5061.1  276.49  5137.8  277.64  5356.5  276.42  5530.9     277
    5652  278.65  5794.2  282.46  5829.6  281.89  5920.1  284.21  5991.2  285.63
#Mann= 7 ,-1 , 0
  4356.3     .12       0  4755.2      .1       0  4977.7     .05       0
  4991.7      .1       0  5137.8     .05       0  5829.6     .07       0
  5920.1     .05       0
Bank Sta=4977.7,4991.7
XS Rating Curve= 0 ,0
Exp/Cntr=0.3,0.1

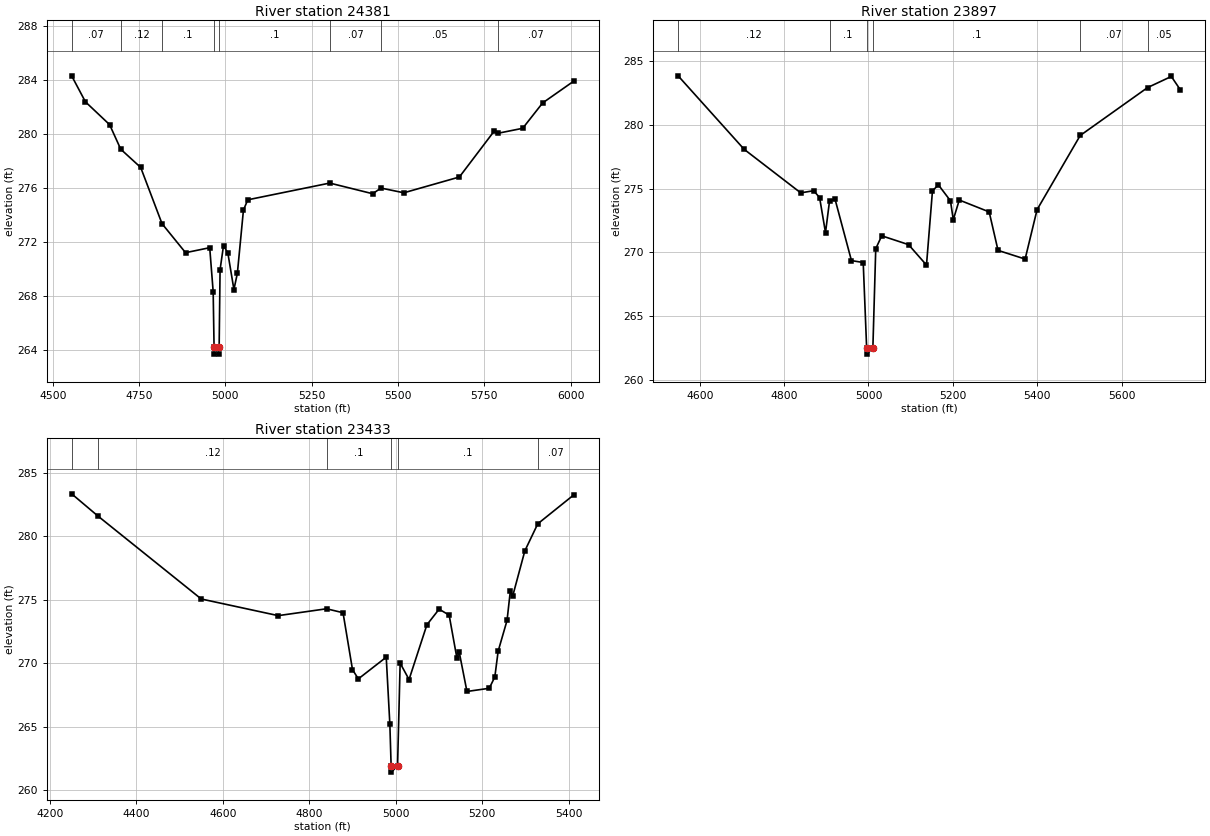
Type RM Length L Ch R = 1 ,24381   ,484,484,484
BEGIN DESCRIPTION:
WEST BRUSHY CREEK 36.0
END DESCRIPTION:
XS GIS Cut Line= 3
      2429224.96       13686875.        2428775.       13686875.
      2427775.04       13686775.
#Sta/Elev= 30
  4554.7  284.34  4594.7  282.41  4664.7  280.72  4696.9   278.9  4754.7  277.55
  4816.5  273.38  4884.7  271.23  4954.7   271.6  4964.7  268.34  4967.3  264.21
  4967.8  263.71  4981.5  263.71    4982  264.21  4984.7  269.97  4994.7  271.76
  5007.2  271.21  5024.8   268.5  5034.8   269.7  5052.4  274.39    5065  275.15
  5302.4  276.39  5426.8   275.6  5450.8  276.02  5517.2  275.67    5678  276.84
  5778.5  280.23  5789.4  280.08  5861.4  280.45  5919.2  282.33  6009.6  283.95
#Mann= 8 ,-1 , 0
  4554.7     .07       0  4696.9     .12       0  4816.5      .1       0
  4967.3     .05       0    4982      .1       0  5302.4     .07       0
  5450.8     .05       0  5789.4     .07       0
Bank Sta=4967.3,4982
XS Rating Curve= 0 ,0
Exp/Cntr=0.3,0.1

Type RM Length L Ch R = 1 ,23897   ,464,464,464
BEGIN DESCRIPTION:
WEST BRUSHY CREEK 35.0
END DESCRIPTION:
XS GIS Cut Line= 3
      2429275.01       13686625.        2428875.       13686425.
      2428325.02     13685925.02
#Sta/Elev= 30
  4548.7  283.82  4705.2  278.07  4839.4  274.66  4870.1  274.83  4884.1  274.29
  4898.1  271.55  4907.6  274.01  4920.5  274.19  4959.6  269.36  4987.5  269.21
  4995.6  262.54  4996.1  262.04  5010.4  262.54  5017.2  270.29  5031.4   271.3
  5094.9  270.61  5137.5  269.01  5151.7  274.83  5165.9  275.28  5194.3  274.04
    5201  272.56  5215.2   274.1  5286.1  273.17  5307.1  270.16  5371.3  269.48
  5399.7  273.35  5501.9  279.15  5661.6   282.9  5717.9  283.77  5739.2  282.73
#Mann= 6 ,-1 , 0
  4548.7     .12       0  4907.6      .1       0  4995.6     .05       0
  5010.4      .1       0  5501.9     .07       0  5661.6     .05       0
Bank Sta=4995.6,5010.4
XS Rating Curve= 0 ,0
Exp/Cntr=0.3,0.1

Type RM Length L Ch R = 1 ,23433   ,465,465,465
BEGIN DESCRIPTION:
WEST BRUSHY CREEK 34.0
END DESCRIPTION:
XS GIS Cut Line= 3
      2429425.01       13686425.        2428825.       13685975.
      2428425.02       13685875.
#Sta/Elev= 30
    4250  283.35  4311.6  281.58    4550  275.07  4728.1  273.76  4839.9   274.3
  4878.1  273.99    4900  269.51  4913.5  268.78  4978.1  270.49  4986.5  265.19
  4989.4  261.94  4989.9  261.44  5004.3  261.94  5010.3  270.02  5030.9  268.73
  5072.2  273.04  5100.5  274.27  5123.7   273.8  5141.7  270.41  5146.9  270.91
  5164.9  267.79  5216.5  268.04  5229.4  268.93  5237.1  270.96  5257.7  273.38
  5265.4  275.73  5270.6  275.28  5298.9  278.86  5328.8  280.99  5412.3  283.27
#Mann= 6 ,-1 , 0
    4250     .07       0  4311.6     .12       0  4839.9      .1       0
  4989.4     .05       0  5004.3      .1       0  5328.8     .07       0
Bank Sta=4989.4,5004.3
XS Rating Curve= 0 ,0
Exp/Cntr=0.3,0.1