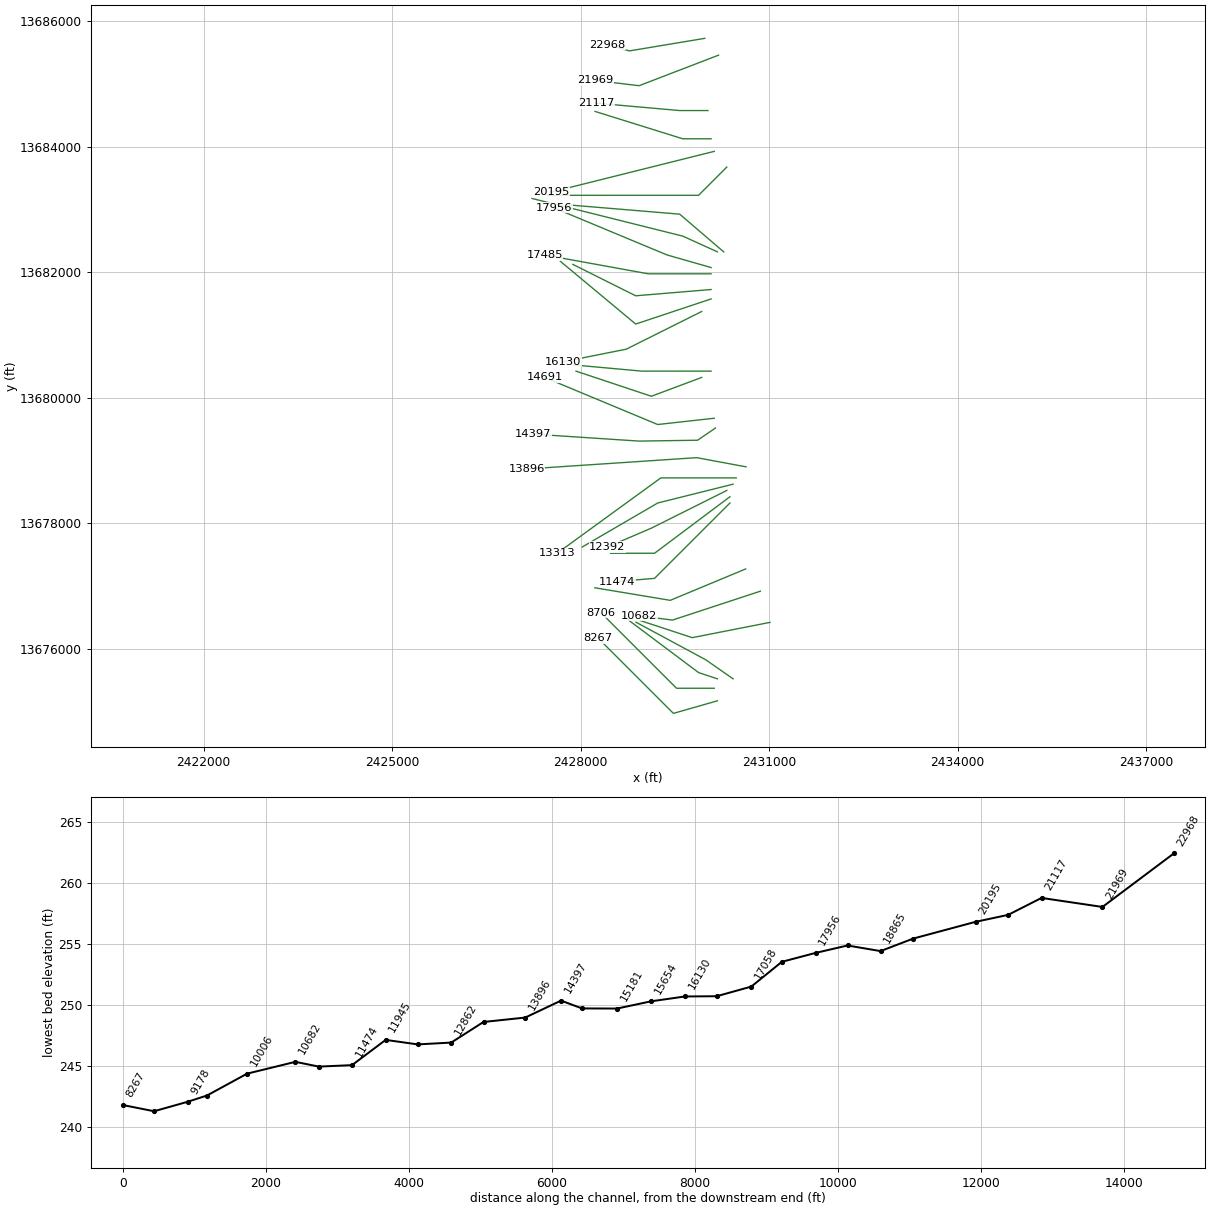
HEC-RAS study WEST BRUSHY CREEK.prj: WEST BRUSHY CREEK Base Level Engineering

--- WEST BRUSHY CREEK.g01 (geometry) --- (continued)

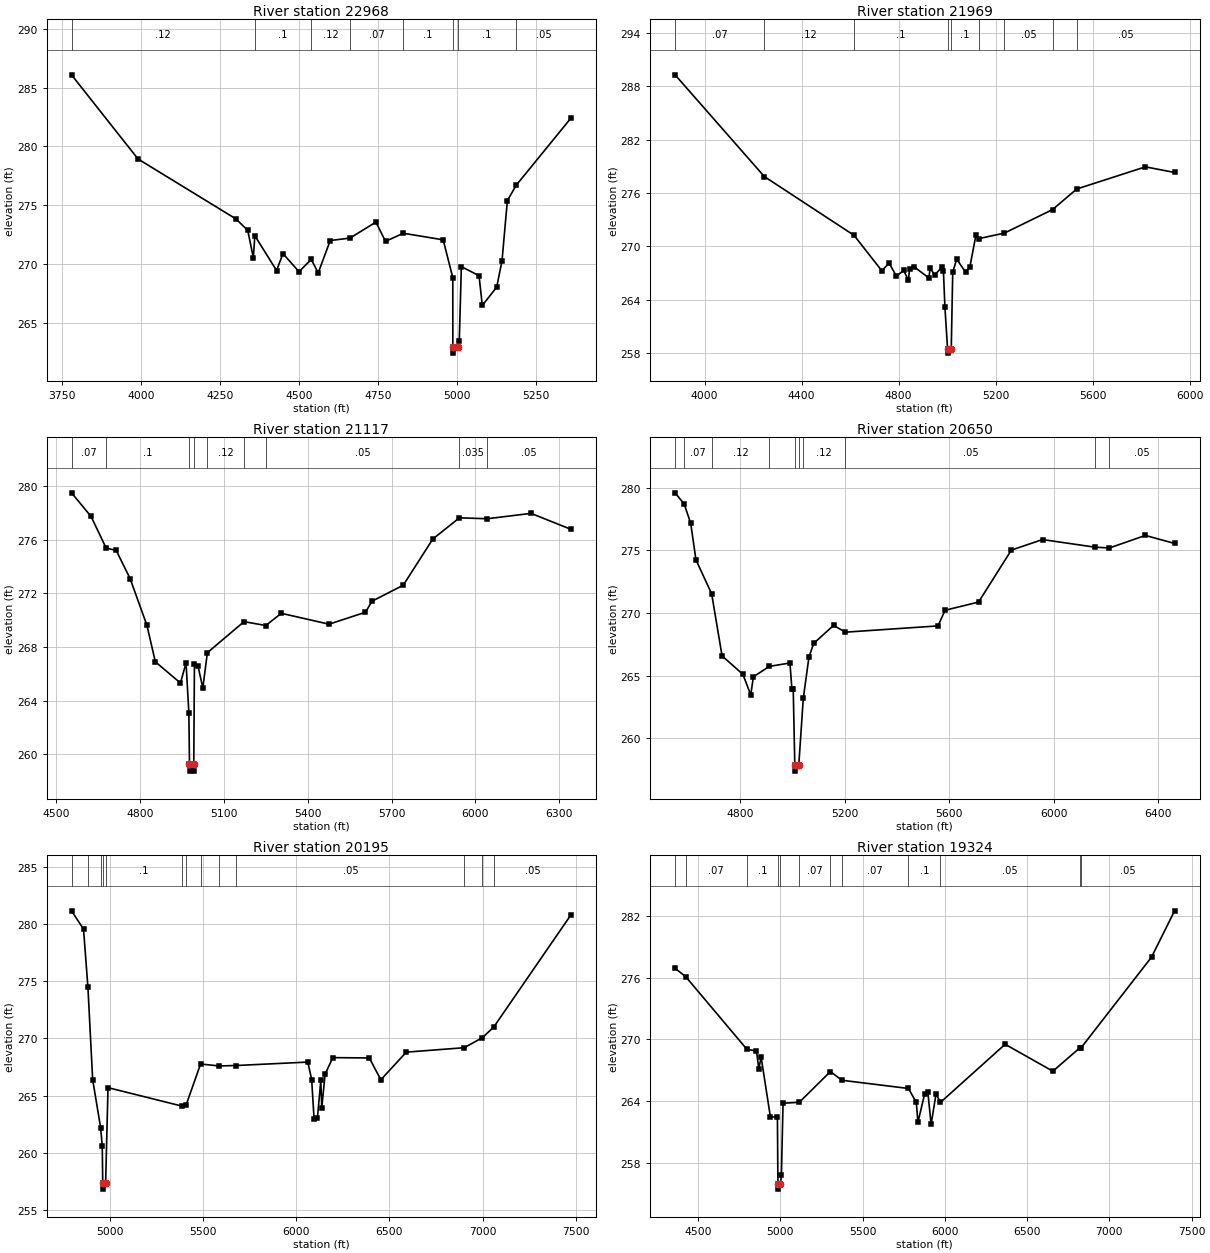
Type RM Length L Ch R = 1 ,22968   ,999,999,999
BEGIN DESCRIPTION:
WEST BRUSHY CREEK 33.0
END DESCRIPTION:
XS GIS Cut Line= 3
        2429975.       13685725.        2428775.       13685525.
      2428424.96     13685625.01
#Sta/Elev= 30
  3779.3  286.09  3989.7  278.93  4298.9  273.84  4336.9  272.86  4354.6  270.52
  4359.3   272.4  4428.1  269.44  4448.4  270.88  4499.1  269.34  4537.8  270.38
  4559.9  269.24  4597.9  271.99  4660.6   272.2  4742.4  273.56  4772.8  271.92
  4829.1  272.61  4955.3  272.05  4985.7  268.83  4985.9  262.91  4986.4  262.41
  5000.8  262.91  5006.3  263.48  5012.8  269.77  5068.7     269  5079.1  266.47
  5124.6  268.02  5141.5  270.28  5158.4  275.39  5186.5   276.7  5359.9  282.42
#Mann= 8 ,-1 , 0
  3779.3     .12       0  4359.3      .1       0  4537.8     .12       0
  4660.6     .07       0  4829.1      .1       0  4985.9     .05       0
  5000.8      .1       0  5186.5     .05       0
Bank Sta=4985.9,5000.8
XS Rating Curve= 0 ,0
Exp/Cntr=0.3,0.1

Type RM Length L Ch R = 1 ,21969   ,852,852,852
BEGIN DESCRIPTION:
H21588
END DESCRIPTION:
XS GIS Cut Line= 3
      2430193.45      13685456.9      2428929.58     13684970.79
      2428229.13     13685054.02
#Sta/Elev= 30
  3878.1  289.26  4246.2  277.84  4616.2  271.24  4730.6  267.26  4760.6  268.13
  4790.6  266.66  4820.6   267.3  4839.9  266.21  4845.3  267.49  4862.1  267.74
  4924.5  266.46  4929.9  267.58  4947.9  266.78  4979.2  267.68  4984.5  267.26
  4990.7  263.17  5001.6  258.52  5002.1  258.02  5016.8  258.52  5022.9  267.13
  5039.2  268.56  5076.4  267.09  5093.8  267.73  5118.5  271.26  5131.4  270.88
  5235.5  271.49  5434.4  274.13  5533.9  276.44  5817.3  278.93  5937.6   278.3
#Mann= 9 ,-1 , 0
  3878.1     .07       0  4246.2     .12       0  4616.2      .1       0
  5001.6     .05       0  5016.8      .1       0  5131.4     .07       0
  5235.5     .05       0  5434.4    .035       0  5533.9     .05       0
Bank Sta=5001.6,5016.8
XS Rating Curve= 0 ,0
Exp/Cntr=0.3,0.1

Type RM Length L Ch R = 1 ,21117   ,467,467,467
BEGIN DESCRIPTION:
WEST BRUSHY CREEK 32.0
END DESCRIPTION:
XS GIS Cut Line= 3
      2430024.96       13684575.        2429575.       13684575.
      2428242.07     13684693.02
#Sta/Elev= 30
  4554.5  279.48  4624.5  277.72  4678.3  275.37  4714.5  275.19  4764.5  273.08
  4824.5  269.61  4854.5   266.9  4944.5  265.32  4964.5  266.82  4974.5  263.12
  4976.8  259.26  4977.3  258.76  4991.6  258.76  4992.1  259.26  4994.5  266.74
    5007  266.61  5024.5  264.95  5040.8  267.58  5172.1  269.89  5249.7   269.6
  5305.6  270.51  5476.3   269.7  5606.8  270.59    5630  271.41  5741.9   272.6
  5847.7  276.04  5943.1  277.62  6042.1  277.55  6199.6  277.95  6342.6  276.76
#Mann= 9 ,-1 , 0
  4554.5     .07       0  4678.3      .1       0  4976.8     .05       0
  4992.1      .1       0  5040.8     .12       0  5172.1      .1       0
  5249.7     .05       0  5943.1    .035       0  6042.1     .05       0
Bank Sta=4976.8,4992.1
XS Rating Curve= 0 ,0
Exp/Cntr=0.3,0.1

Type RM Length L Ch R = 1 ,20650   ,455,455,455
BEGIN DESCRIPTION:
WEST BRUSHY CREEK 31.0
END DESCRIPTION:
XS GIS Cut Line= 3
      2430074.98       13684125.        2429625.       13684125.
      2428228.17     13684561.08
#Sta/Elev= 30
  4549.6  279.58  4584.5  278.69  4609.6  277.14  4629.6  274.23  4689.8  271.52
  4729.6  266.57  4809.6  265.09  4839.6  263.45  4849.6   264.9  4910.9  265.73
  4989.6     266  4997.1  263.92  5002.2  263.92  5008.2  257.87  5008.7  257.37
  5023.5  257.87  5040.7  263.17  5062.4  266.47  5080.8  267.57  5156.7     269
  5202.1  268.46  5556.7  268.96  5583.9  270.21    5712  270.86  5837.7  275.01
    5957  275.85  6158.9  275.24  6213.2  275.18    6351  276.18  6462.9  275.54
#Mann= 10 ,-1 , 0
  4549.6     .05       0  4584.5     .07       0  4689.8     .12       0
  4910.9      .1       0  5008.2     .05       0  5023.5      .1       0
  5040.7     .12       0  5202.1     .05       0  6158.9    .035       0
  6213.2     .05       0
Bank Sta=5008.2,5023.5
XS Rating Curve= 0 ,0
Exp/Cntr=0.3,0.1

Type RM Length L Ch R = 1 ,20195   ,871,871,871
BEGIN DESCRIPTION:
WEST BRUSHY CREEK 30.0
END DESCRIPTION:
XS GIS Cut Line= 3
      2430124.98     13683924.99        2429925.       13683875.
        2427525.       13683275.
#Sta/Elev= 30
  4794.2  281.18  4858.6  279.58  4882.2  274.49  4907.6   266.4  4950.7  262.15
  4959.1  260.56  4961.7   257.3  4962.2   256.8  4977.1   257.3    4990  265.69
  5385.2  264.08  5409.5  264.19  5486.6  267.76  5587.3  267.59  5678.7  267.63
    6062  267.93  6082.6   266.4  6095.5  262.94  6113.6  263.05  6131.6  266.32
  6136.8  263.94  6154.8  266.88    6196  268.32  6391.9  268.29  6453.7  266.38
  6590.3   268.8  6901.4  269.19  6997.5  270.06  7058.7  270.98  7474.2  280.84
#Mann= 13 ,-1 , 0
  4794.2      .1       0  4882.2     .12       0  4950.7      .1       0
  4961.7     .05       0  4977.1      .1       0  5385.2     .12       0
  5409.5     .07       0  5486.6     .12       0  5587.3     .07       0
  5678.7     .05       0  6901.4    .035       0  6997.5     .07       0
  7058.7     .05       0
Bank Sta=4961.7,4977.1
XS Rating Curve= 0 ,0
Exp/Cntr=0.3,0.1

Type RM Length L Ch R = 1 ,19324   ,459,459,459
BEGIN DESCRIPTION:
WEST BRUSHY CREEK 29.0
END DESCRIPTION:
XS GIS Cut Line= 3
      2430324.99     13683674.99        2429875.       13683225.
      2427474.99       13683225.
#Sta/Elev= 30
  4359.9  276.91  4424.3   276.1  4796.6  269.03  4854.9  268.87    4869  267.12
  4883.1  268.27  4939.7  262.42  4982.1  262.49  4985.1  255.93  4985.6  255.43
  5000.5  255.93  5006.3  256.83  5016.3  263.78  5115.4  263.88  5304.3  266.87
  5373.6  266.02  5778.8  265.22  5826.3  263.86  5836.3  261.93  5876.3  264.65
  5896.3   264.9  5916.3  261.73  5946.3   264.7  5972.7  263.86  6366.3  269.52
  6656.3   266.9  6819.5  269.16  6828.1  269.18  7256.3     278  7396.3   282.5
#Mann= 12 ,-1 , 0
  4359.9     .05       0  4424.3     .07       0  4796.6      .1       0
  4985.1     .05       0  5000.5      .1       0  5115.4     .07       0
  5304.3     .05       0  5373.6     .07       0  5778.8      .1       0
  5972.7     .05       0  6819.5    .035       0  6828.1     .05       0
Bank Sta=4985.1,5000.5
XS Rating Curve= 0 ,0
Exp/Cntr=0.3,0.1

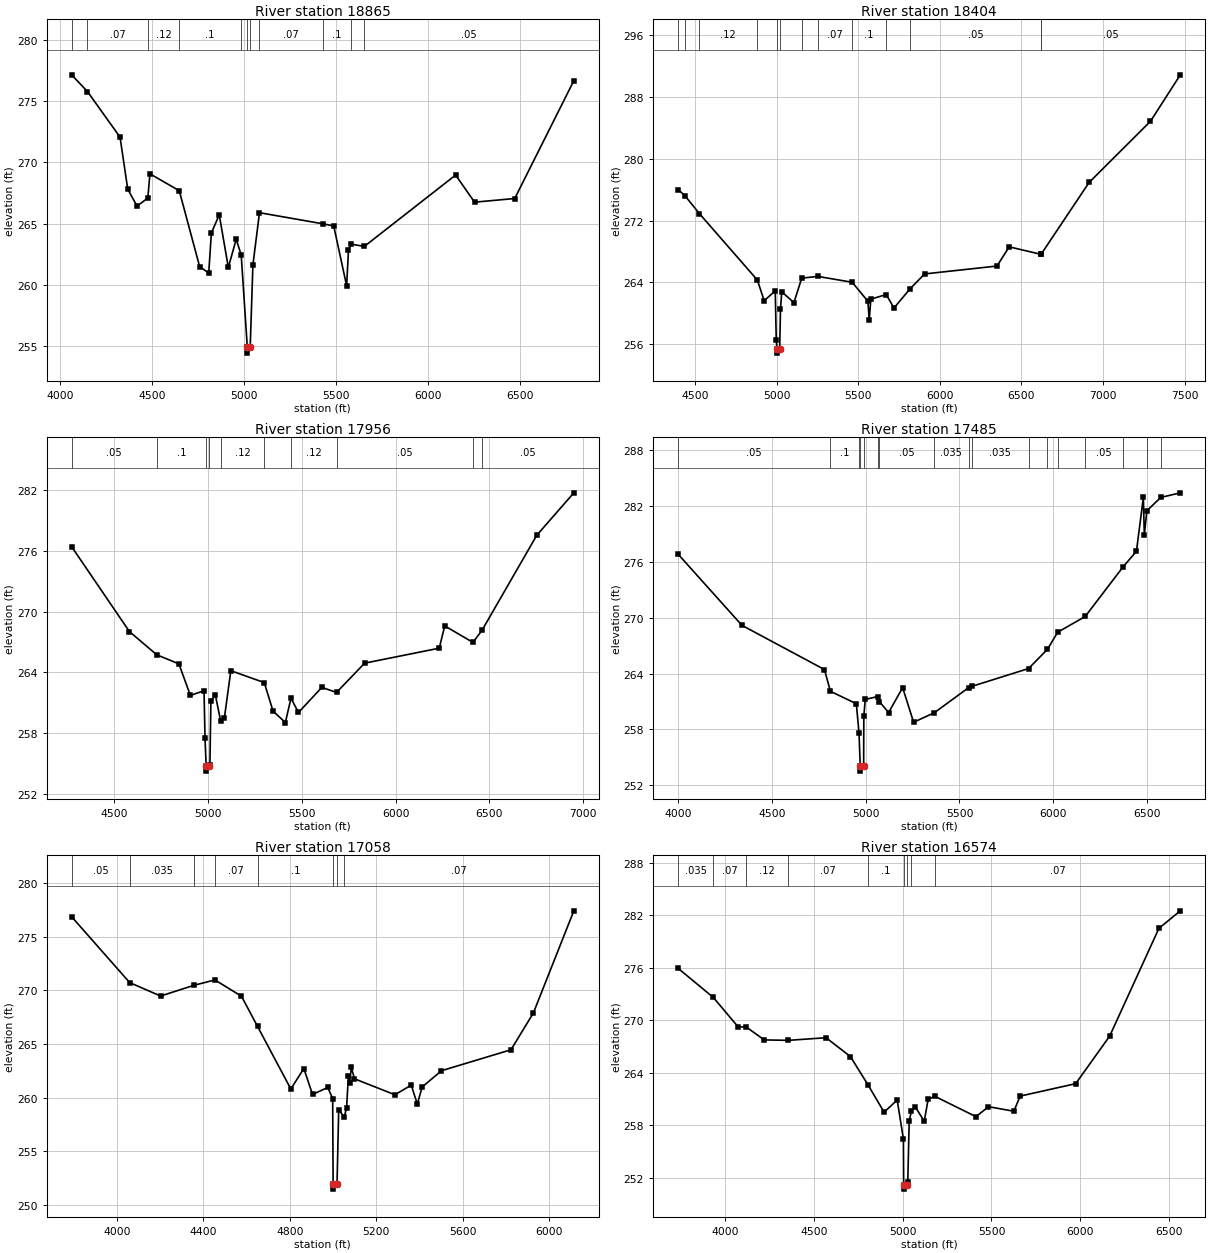
Type RM Length L Ch R = 1 ,18865   ,461,461,461
BEGIN DESCRIPTION:
WEST BRUSHY CREEK 28.0
END DESCRIPTION:
XS GIS Cut Line= 3
        2430275.       13682325.        2429575.       13682925.
        2427775.       13683075.
#Sta/Elev= 30
  4064.3  277.17  4150.3   275.8  4327.2  272.07  4368.9  267.82  4419.4  266.43
  4478.1  267.09  4489.6  269.07  4648.9  267.69  4759.6  261.48    4809  260.95
  4823.3  264.23  4866.1  265.72  4915.5  261.41  4958.3  263.72  4985.5  262.42
  5018.5   254.9    5019   254.4  5034.3   254.9    5049  261.61  5084.7  265.89
  5429.3  264.98    5488  264.81  5558.2  259.91  5568.3  262.86  5584.5  263.31
  5654.2  263.13  6150.3  268.97  6253.1  266.75  6471.4  267.05  6792.5  276.69
#Mann= 11 ,-1 , 0
  4064.3     .05       0  4150.3     .07       0  4478.1     .12       0
  4648.9      .1       0  4985.5     .12       0  5018.5     .05       0
  5034.3     .12       0  5084.7     .07       0  5429.3      .1       0
  5584.5     .12       0  5654.2     .05       0
Bank Sta=5018.5,5034.3
XS Rating Curve= 0 ,0
Exp/Cntr=0.3,0.1

Type RM Length L Ch R = 1 ,18404   ,448,448,448
BEGIN DESCRIPTION:
WEST BRUSHY CREEK 27.0
END DESCRIPTION:
XS GIS Cut Line= 3
      2430175.02     13682324.99        2429625.       13682575.
      2427225.03     13683174.99
#Sta/Elev= 30
    4396  276.01  4437.7  275.21    4526  272.91    4882   264.3  4923.3  261.64
  4991.4  262.91  4997.4  256.62  5002.5  255.36    5003  254.86  5018.5  255.36
  5023.4  260.53  5031.1  262.79  5105.8  261.39  5153.5  264.55  5252.1  264.78
  5463.2  264.02  5559.4  261.56  5567.1  259.13  5577.4  261.84  5671.5  262.43
  5719.1  260.69    5818  263.19  5907.3   265.1  6350.5  266.12  6425.2   268.6
    6619  267.64  6622.7   267.7  6914.8  276.92  7291.1  284.83    7474  290.84
#Mann= 13 ,-1 , 0
    4396     .05       0  4437.7     .07       0    4526     .12       0
    4882      .1       0  5002.5     .05       0  5018.5      .1       0
  5153.5     .12       0  5252.1     .07       0  5463.2      .1       0
  5671.5     .12       0    5818     .05       0    6619    .035       0
  6622.7     .05       0
Bank Sta=5002.5,5018.5
XS Rating Curve= 0 ,0
Exp/Cntr=0.3,0.1

Type RM Length L Ch R = 1 ,17956   ,471,471,471
BEGIN DESCRIPTION:
WEST BRUSHY CREEK 26.0
END DESCRIPTION:
XS GIS Cut Line= 3
      2430074.99       13682075.        2429375.       13682275.
        2427575.       13683025.
#Sta/Elev= 30
    4272  276.41  4580.1  268.03  4725.6  265.74    4844  264.84  4905.1  261.72
  4977.9  262.19  4983.1  257.55  4989.3  254.75  4989.8  254.25  5005.4  254.75
  5009.2  254.85  5014.6   261.2  5038.5  261.76  5066.3  259.23  5086.1  259.45
  5120.8  264.17  5299.2  262.99  5346.1  260.17  5411.7  259.05  5441.6  261.45
  5481.5  260.04  5606.1  262.52  5684.5  262.02  5834.2  264.91  6232.3  266.39
  6261.5  268.59  6412.1  266.96  6460.2  268.15  6752.3  277.54    6950  281.73
#Mann= 10 ,-1 , 0
    4272     .05       0  4725.6      .1       0  4989.3     .05       0
  5005.4      .1       0  5066.3     .12       0  5299.2      .1       0
  5441.6     .12       0  5684.5     .05       0  6412.1    .035       0
  6460.2     .05       0
Bank Sta=4989.3,5005.4
XS Rating Curve= 0 ,0
Exp/Cntr=0.3,0.1

Type RM Length L Ch R = 1 ,17485   ,427,427,427
BEGIN DESCRIPTION:
WEST BRUSHY CREEK 25.0
END DESCRIPTION:
XS GIS Cut Line= 3
        2430075.       13681975.        2429075.       13681975.
      2427424.95     13682275.01
#Sta/Elev= 30
    4000  276.82    4340  269.18    4780  264.43    4812  262.09    4950  260.76
  4964.2  257.65    4971  254.02  4971.5  253.52    4989  254.02    4990  259.41
  4997.5  261.22    5064  261.53  5072.8  260.99    5122  259.81  5196.9  262.49
  5255.4  258.77  5365.7  259.79  5548.2  262.48  5566.8  262.63  5868.5  264.54
  5969.1  266.61  6023.5  268.44  6170.2  270.13  6371.3  275.44  6443.3  277.13
  6480.1  282.92  6485.2   278.9  6498.9  281.48  6572.4  282.91  6677.1  283.41
#Mann= 17 ,-1 , 0
    4000     .05       0    4812      .1       0  4964.2     .05       0
    4971     .05       0    4989     .05       0    5064    .035       0
  5072.8     .05       0  5365.7    .035       0  5548.2     .05       0
  5566.8    .035       0  5868.5     .05       0  5969.1     .07       0
  6023.5    .035       0  6170.2     .05       0  6371.3     .07       0
  6498.9     .05       0  6572.4     .07       0
Bank Sta=4971,4989
XS Rating Curve= 0 ,0
Exp/Cntr=0.3,0.1

Type RM Length L Ch R = 1 ,17058   ,484,484,484
BEGIN DESCRIPTION:
WEST BRUSHY CREEK 24.0
END DESCRIPTION:
XS GIS Cut Line= 3
      2430075.04       13681725.        2428875.       13681625.
      2427875.03     13682124.99
#Sta/Elev= 30
  3791.2  276.84  4059.6  270.71  4202.7  269.46  4355.2  270.45  4453.7  270.96
  4576.5  269.44  4650.8  266.63  4804.7  260.81  4864.9  262.71  4905.1   260.3
  4975.3  260.95  4998.2  259.92  5000.3  251.99  5000.8  251.49  5018.4  251.99
  5026.1  258.88  5051.5   258.2  5062.5  259.05  5070.9  262.03  5076.5  261.38
  5084.8  262.82  5098.8  261.76  5286.1  260.27  5361.6  261.17  5389.5   259.4
  5411.9  260.99  5501.3  262.51  5822.7  264.46  5926.2  267.88  6113.4  277.39
#Mann= 8 ,-1 , 0
  3791.2     .05       0  4059.6    .035       0  4355.2     .05       0
  4453.7     .07       0  4650.8      .1       0  5000.3     .05       0
  5018.4      .1       0  5051.5     .07       0
Bank Sta=5000.3,5018.4
XS Rating Curve= 0 ,0
Exp/Cntr=0.3,0.1

Type RM Length L Ch R = 1 ,16574   ,444,444,444
BEGIN DESCRIPTION:
WEST BRUSHY CREEK 23.0
END DESCRIPTION:
XS GIS Cut Line= 3
      2430075.05     13681575.02        2428875.       13681175.
      2427675.01     13682174.99
#Sta/Elev= 30
  3735.9  275.93  3934.2   272.6  4073.3  269.25  4119.8  269.22  4220.8  267.75
  4356.2   267.7  4568.7     268  4705.7  265.85  4805.6  262.59  4895.4  259.49
  4969.2  260.88  5004.1  256.42  5005.5   251.2    5006   250.7  5023.6   251.2
  5028.8  251.57  5036.7  258.47  5049.6  259.65  5071.8  260.07  5121.3  258.46
  5143.4  260.96  5180.8  261.31  5412.8  258.98  5483.1  260.12  5625.7   259.6
  5661.5  261.33  5973.9  262.75  6165.2  268.18  6442.5   280.5  6562.9   282.5
#Mann= 9 ,-1 , 0
  3735.9    .035       0  3934.2     .07       0  4119.8     .12       0
  4356.2     .07       0  4805.6      .1       0  5005.5     .05       0
  5023.6      .1       0  5049.6     .12       0  5180.8     .07       0
Bank Sta=5005.5,5023.6
XS Rating Curve= 0 ,0
Exp/Cntr=0.3,0.1

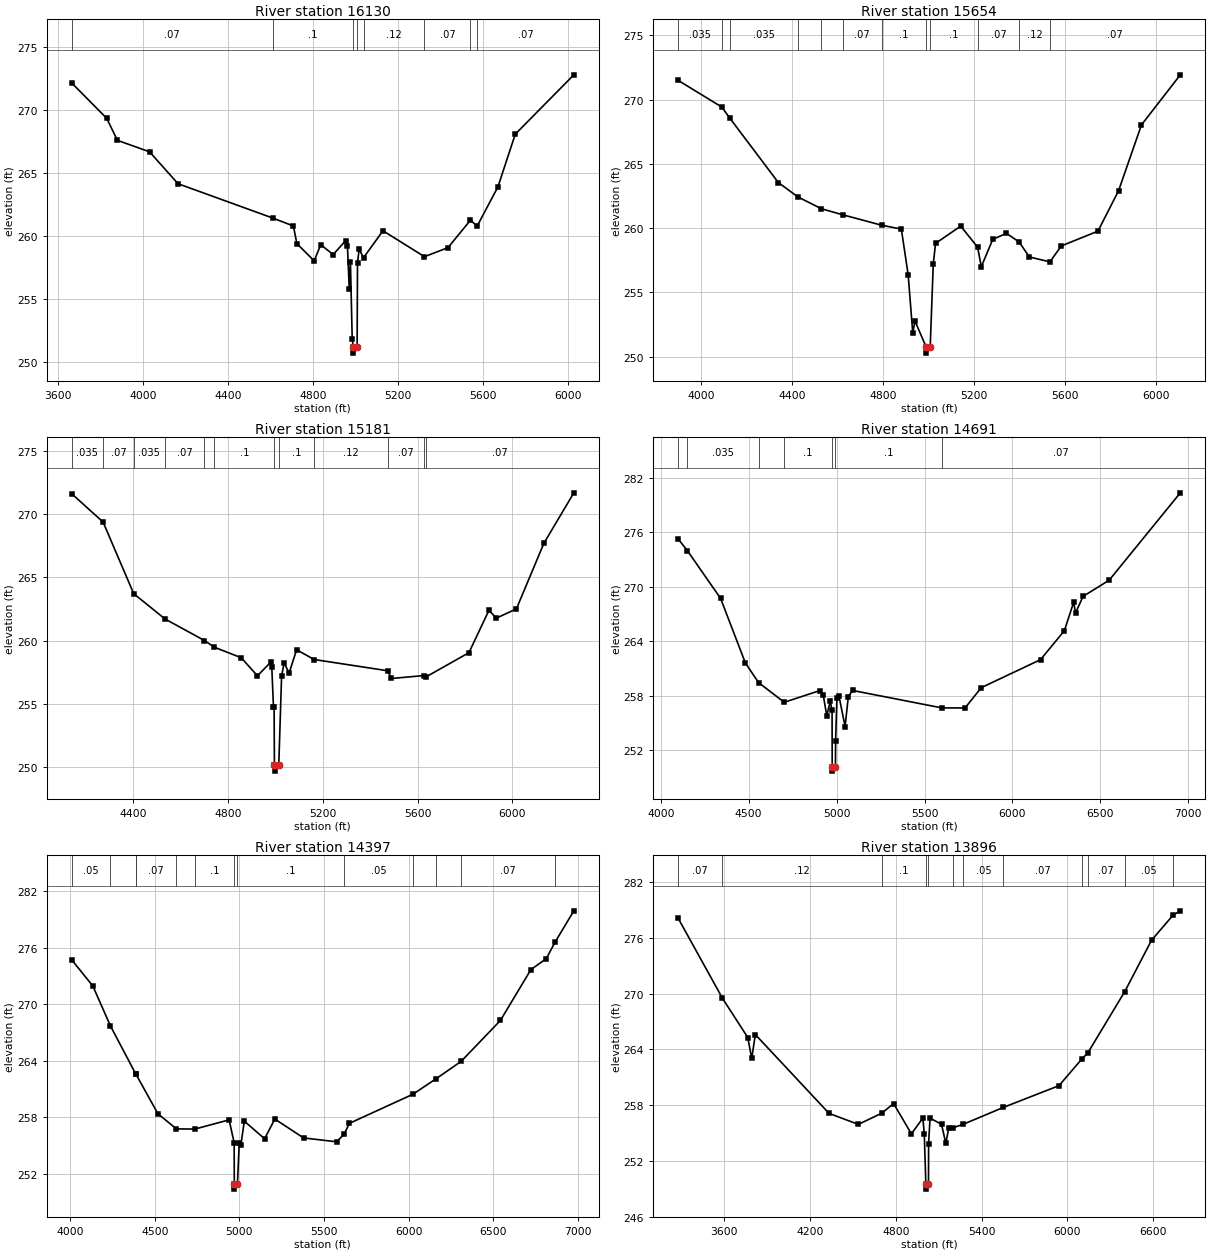
Type RM Length L Ch R = 1 ,16130   ,476,476,476
BEGIN DESCRIPTION:
WEST BRUSHY CREEK 22.0
END DESCRIPTION:
XS GIS Cut Line= 3
      2429925.01       13681375.        2428725.       13680775.
      2427724.96     13680574.99
#Sta/Elev= 30
  3664.9  272.17  3829.8  269.35  3880.1   267.6  4031.1  266.69  4165.2  264.15
  4610.8  261.42  4707.5  260.79  4724.2  259.38  4805.3  258.02  4836.1   259.3
  4894.7  258.52  4953.4  259.62  4961.8  259.22  4970.2  255.79  4975.8  257.95
  4984.2  251.81    4989  251.18  4989.5  250.68  5007.3  251.18  5009.1  257.86
  5016.7  258.94  5037.5  258.27  5128.9  260.41    5324  258.35  5434.9  259.07
  5540.1  261.25  5571.7  260.78  5669.4   263.9    5751  268.09  6026.4  272.81
#Mann= 8 ,-1 , 0
  3664.9     .07       0  4610.8      .1       0    4989     .05       0
  5007.3      .1       0  5037.5     .12       0    5324     .07       0
  5540.1     .12       0  5571.7     .07       0
Bank Sta=4989,5007.3
XS Rating Curve= 0 ,0
Exp/Cntr=0.3,0.1

Type RM Length L Ch R = 1 ,15654   ,473,473,473
BEGIN DESCRIPTION:
WEST BRUSHY CREEK 21.0
END DESCRIPTION:
XS GIS Cut Line= 3
      2430075.04       13680425.        2428975.       13680425.
      2427874.97       13680525.
#Sta/Elev= 30
    3900   271.5  4091.2  269.43  4127.4  268.55    4340  263.55  4426.1  262.43
  4529.3  261.51  4622.9  261.04  4793.7  260.23    4880  259.93    4910  256.36
    4930  251.86    4940  252.77  4988.3  250.78  4988.8  250.28  5006.7  250.78
  5020.1  257.22  5030.2  258.82  5140.6  260.16  5214.9  258.52    5231     257
  5281.2  259.13  5341.4   259.6  5397.4  258.92  5441.9  257.76    5532  257.38
  5582.4  258.62  5743.1  259.77  5833.5  262.91  5933.9  268.03  6104.6  271.93
#Mann= 12 ,-1 , 0
    3900    .035       0  4091.2     .07       0  4127.4    .035       0
  4426.1     .07       0  4529.3     .05       0  4622.9     .07       0
  4793.7      .1       0  4988.3     .05       0  5006.7      .1       0
  5214.9     .07       0  5397.4     .12       0    5532     .07       0
Bank Sta=4988.3,5006.7
XS Rating Curve= 0 ,0
Exp/Cntr=0.3,0.1

Type RM Length L Ch R = 1 ,15181   ,490,490,490
BEGIN DESCRIPTION:
WEST BRUSHY CREEK 20.0
END DESCRIPTION:
XS GIS Cut Line= 3
      2429925.01       13680325.        2429125.       13680025.
      2427925.02     13680424.99
#Sta/Elev= 30
  4139.7  271.61  4272.4  269.37  4401.6  263.71    4534  261.71  4700.1  260.01
    4742  259.48  4855.3  258.65  4923.8  257.22    4979  258.28  4984.3  257.92
  4991.4  254.75  4994.1  254.75  4995.4  250.19  4995.9  249.69  5013.8  250.19
  5025.7   257.2  5036.3  258.24  5057.4  257.44    5089  259.28    5163  258.51
  5473.4  257.62  5489.5  257.01  5625.6  257.24  5636.5  257.15  5816.3  259.05
  5900.6  262.39  5932.3  261.78  6016.6  262.51  6132.5  267.69    6259  271.68
#Mann= 12 ,-1 , 0
  4139.7    .035       0  4272.4     .07       0  4401.6    .035       0
    4534     .07       0  4700.1     .12       0    4742      .1       0
  4995.4     .05       0  5013.8      .1       0    5163     .12       0
  5473.4     .07       0  5625.6     .12       0  5636.5     .07       0
Bank Sta=4995.4,5013.8
XS Rating Curve= 0 ,0
Exp/Cntr=0.3,0.1

Type RM Length L Ch R = 1 ,14691   ,294,294,294
BEGIN DESCRIPTION:
WEST BRUSHY CREEK 19.0
END DESCRIPTION:
XS GIS Cut Line= 3
      2430125.02       13679675.        2429225.       13679575.
      2427424.96     13680325.02
#Sta/Elev= 30
  4098.8  275.26  4151.3  273.97  4340.3  268.71  4481.2  261.61  4556.3  259.44
  4702.5  257.28  4903.7  258.56  4923.9  258.09    4944  255.81  4964.1  257.38
  4974.2  256.39    4975   250.2  4975.5   249.7  4993.4   250.2  4994.3  253.06
  5001.8  257.75  5013.6  257.95  5048.2  254.61  5066.6  257.89  5090.5  258.58
  5598.3  256.66  5730.2  256.65  5822.8  258.89  6159.7  261.97  6295.1  265.16
  6348.2  268.29  6358.5  267.11  6401.9  268.94  6549.7  270.71  6954.4  280.33
#Mann= 7 ,-1 , 0
  4098.8     .05       0  4151.3    .035       0  4556.3     .12       0
  4702.5      .1       0    4975     .05       0  4993.4      .1       0
  5598.3     .07       0
Bank Sta=4975,4993.4
XS Rating Curve= 0 ,0
Exp/Cntr=0.3,0.1

Type RM Length L Ch R = 1 ,14397   ,501,501,501
BEGIN DESCRIPTION:
H21587
END DESCRIPTION:
XS GIS Cut Line= 4
      2430144.84      13679519.4      2429860.13     13679324.96
      2428929.58     13679311.07      2427242.05     13679422.19
#Sta/Elev= 30
  4009.3  274.71  4134.3  271.93  4238.4  267.68  4386.9  262.61  4388.3  262.58
  4519.2  258.34  4628.3  256.74  4736.9  256.72  4939.3   257.7  4969.3  255.27
  4970.1  250.84  4970.6  250.34  4988.5  250.84  4999.3  255.26  5009.3  255.08
  5029.3  257.56  5149.3  255.69  5209.3  257.79  5379.5  255.78  5573.9  255.37
  5618.9  256.17  5650.1  257.33  6025.2  260.42  6159.8  262.04  6309.9  263.91
    6542  268.26  6722.4  273.67  6812.6  274.82  6866.9  276.64  6975.9  279.91
#Mann= 13 ,-1 , 0
  4009.3     .05       0  4238.4     .07       0  4386.9     .12       0
  4388.3     .07       0  4628.3     .12       0  4736.9      .1       0
  4970.1     .05       0  4988.5      .1       0  5618.9     .05       0
  6025.2     .07       0  6159.8     .05       0  6309.9     .07       0
  6866.9     .05       0
Bank Sta=4970.1,4988.5
XS Rating Curve= 0 ,0
Exp/Cntr=0.3,0.1

Type RM Length L Ch R = 1 ,13896   ,583,583,583
BEGIN DESCRIPTION:
WEST BRUSHY CREEK 18.0
END DESCRIPTION:
XS GIS Cut Line= 3
      2430630.97     13678901.35      2429846.24     13679047.18
      2427138.91     13678866.69
#Sta/Elev= 30
  3278.2  278.12  3588.5  269.49  3765.4  265.27  3792.8  263.02  3818.2  265.59
  4333.9   257.1  4538.6  255.92  4701.4  257.12  4784.9  258.16  4909.4   254.9
  4989.6   256.6  4999.6  254.88  5010.5  249.45    5011  248.95  5028.9  249.45
  5029.7  253.84  5039.7   256.6  5119.9  255.93    5150  253.88    5170  255.48
  5197.6  255.54  5273.4  255.94  5552.7  257.75  5941.7  260.09  6099.4  262.93
  6143.1  263.62  6401.4  270.22  6588.9  275.75  6738.9  278.44  6789.7  278.91
#Mann= 12 ,-1 , 0
  3278.2     .07       0  3588.5     .12       0  4701.4      .1       0
  5010.5     .05       0  5028.9      .1       0  5197.6     .07       0
  5273.4     .05       0  5552.7     .07       0  6099.4     .05       0
  6143.1     .07       0  6401.4     .05       0  6738.9     .07       0
Bank Sta=5010.5,5028.9
XS Rating Curve= 0 ,0
Exp/Cntr=0.3,0.1

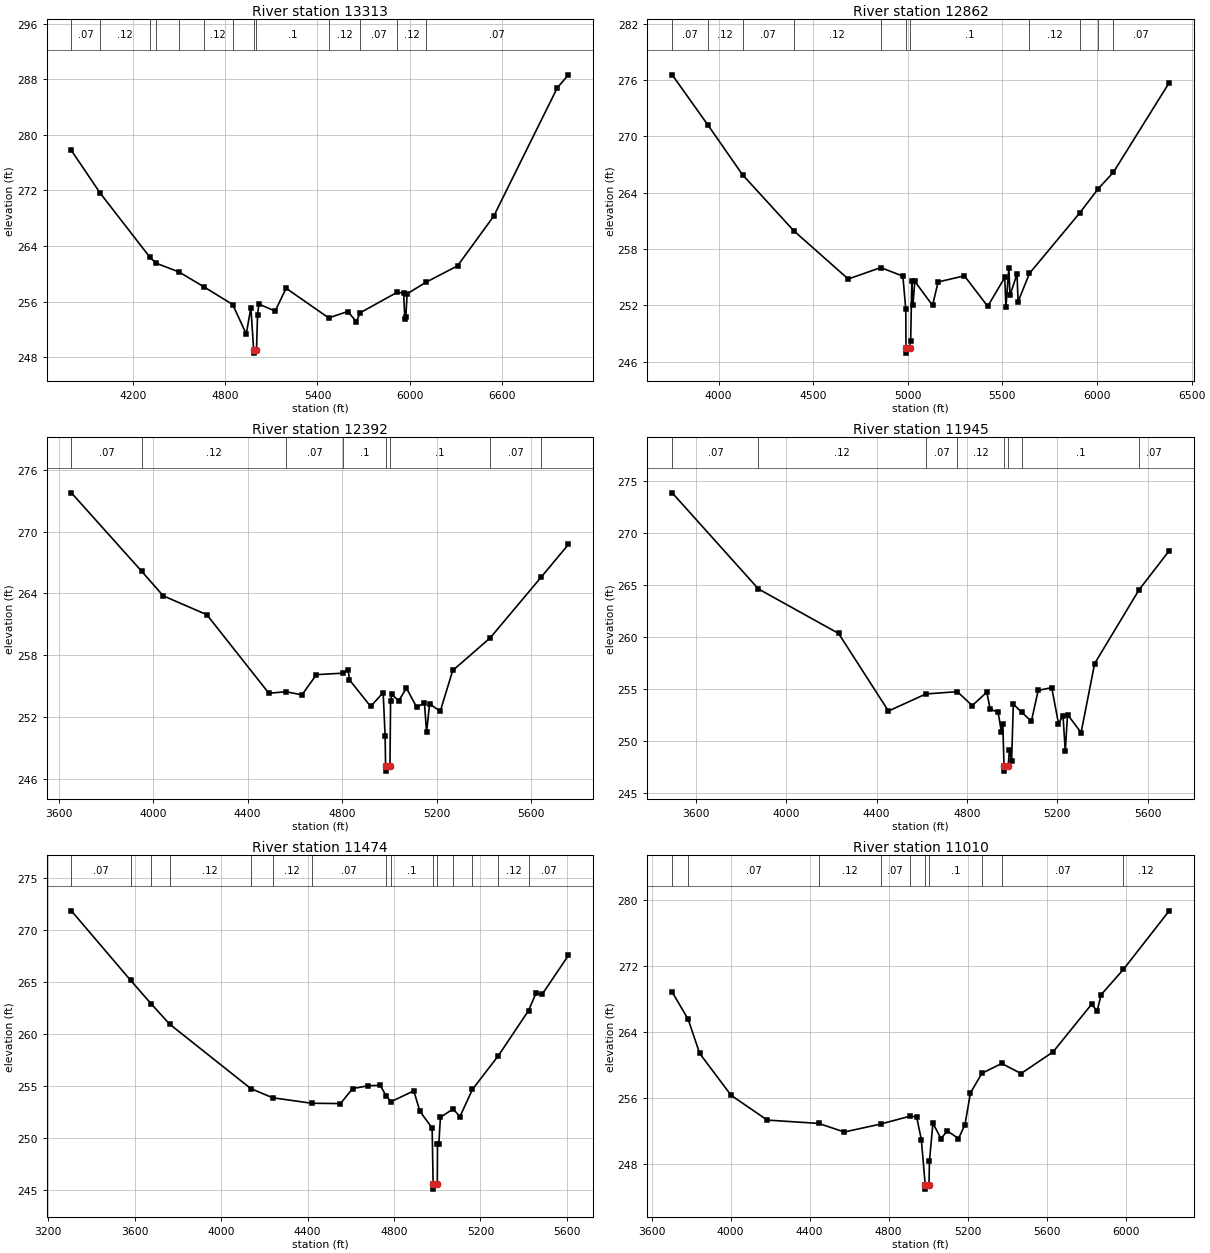
Type RM Length L Ch R = 1 ,13313   ,451,451,451
BEGIN DESCRIPTION:
WEST BRUSHY CREEK 17.0
END DESCRIPTION:
XS GIS Cut Line= 3
      2430474.98       13678725.        2429275.       13678725.
        2427625.       13677525.
#Sta/Elev= 30
  3795.7  277.76  3984.4  271.59  4308.5  262.36  4347.8  261.54  4496.5  260.28
  4657.1  258.17  4847.4  255.58  4935.7  251.34  4965.7  255.14  4983.9  249.09
  4984.4  248.59  5002.4  249.09  5009.2  254.03  5017.7  255.64  5124.3  254.65
  5195.4  257.93  5473.1  253.66  5597.3  254.58  5653.7  253.12  5677.6  254.39
  5917.2  257.32  5961.3  257.26  5969.8  253.55    5976  253.86  5984.5  257.13
  6108.7  258.81  6312.9  261.15  6549.4  268.32  6963.6  286.79  7035.9  288.65
#Mann= 13 ,-1 , 0
  3795.7     .07       0  3984.4     .12       0  4308.5     .07       0
  4347.8     .12       0  4496.5     .07       0  4657.1     .12       0
  4847.4      .1       0  4983.9     .05       0  5002.4      .1       0
  5473.1     .12       0  5677.6     .07       0  5917.2     .12       0
  6108.7     .07       0
Bank Sta=4983.9,5002.4
XS Rating Curve= 0 ,0
Exp/Cntr=0.3,0.1

Type RM Length L Ch R = 1 ,12862   ,470,470,470
BEGIN DESCRIPTION:
WEST BRUSHY CREEK 16.0
END DESCRIPTION:
XS GIS Cut Line= 3
      2430424.99       13678625.        2429225.       13678325.
      2428024.97     13677624.98
#Sta/Elev= 30
  3755.1  276.57  3944.6   271.2  4126.8  265.92  4397.3  259.95  4685.4   254.8
  4857.2  256.02    4974  255.11  4989.4  251.58  4990.6   247.4  4991.1   246.9
  5009.2   247.4  5015.2  248.16  5021.4  254.63  5027.2     252  5037.1  254.55
  5130.9  251.99  5160.3  254.49  5299.2  255.14  5422.4  251.89  5512.6  254.97
  5518.4  251.77  5534.1  255.98  5539.9  253.07  5577.1  255.32  5582.9  252.39
  5642.9   255.4  5907.6  261.82  6006.4  264.43  6086.2  266.17  6381.3  275.73
#Mann= 11 ,-1 , 0
  3755.1     .07       0  3944.6     .12       0  4126.8     .07       0
  4397.3     .12       0  4857.2      .1       0  4990.6     .05       0
  5009.2      .1       0  5642.9     .12       0  5907.6     .07       0
  6006.4     .12       0  6086.2     .07       0
Bank Sta=4990.6,5009.2
XS Rating Curve= 0 ,0
Exp/Cntr=0.3,0.1

Type RM Length L Ch R = 1 ,12392   ,447,447,447
BEGIN DESCRIPTION:
WEST BRUSHY CREEK 15.0
END DESCRIPTION:
XS GIS Cut Line= 3
      2430324.98     13678524.99        2429125.       13677925.
        2428425.       13677625.
#Sta/Elev= 30
  3654.2  273.77  3951.3  266.16  4042.7  263.77  4227.2  261.94  4489.9  254.31
  4562.7  254.46  4629.7  254.15  4691.2  256.12  4803.5  256.26  4825.3   256.6
  4830.9  255.61  4920.4  253.03  4973.5  254.37  4981.8  250.13  4983.7  247.25
  4984.2  246.75  5002.3  247.25  5004.9  253.57  5010.3  254.19  5039.3  253.58
    5072  254.81  5115.5  252.95  5148.1  253.38  5157.2  250.54  5169.9  253.27
  5215.2  252.57  5267.8  256.52    5427   259.7  5642.7   265.6  5757.4  268.76
#Mann= 8 ,-1 , 0
  3654.2     .07       0  3951.3     .12       0  4562.7     .07       0
  4803.5      .1       0  4983.7     .05       0  5002.3      .1       0
    5427     .07       0  5642.7     .12       0
Bank Sta=4983.7,5002.3
XS Rating Curve= 0 ,0
Exp/Cntr=0.3,0.1

Type RM Length L Ch R = 1 ,11945   ,471,471,471
BEGIN DESCRIPTION:
WEST BRUSHY CREEK 14.0
END DESCRIPTION:
XS GIS Cut Line= 3
        2430375.       13678425.        2429175.       13677525.
        2428475.       13677525.
#Sta/Elev= 30
    3495  273.84    3877  264.61  4231.5  260.34  4452.3  252.89  4618.1  254.53
  4757.2  254.75  4823.1  253.41  4887.7   254.7  4902.3  253.08  4937.7  252.77
  4952.3  250.87  4958.5  251.63  4963.8  247.62  4964.3  247.12  4982.4  247.62
  4987.7  249.14  4997.5  248.11    5005  253.55  5041.7  252.78    5085  251.91
    5115  254.87    5175  255.14    5205  251.69    5225  252.46    5235  249.02
    5245  252.55    5305  250.82    5365  257.45  5561.3  264.52    5695  268.28
#Mann= 8 ,-1 , 0
    3495     .07       0    3877     .12       0  4618.1     .07       0
  4757.2     .12       0  4963.8     .05       0  4982.4     .12       0
  5041.7      .1       0  5561.3     .07       0
Bank Sta=4963.8,4982.4
XS Rating Curve= 0 ,0
Exp/Cntr=0.3,0.1

Type RM Length L Ch R = 1 ,11474   ,464,464,464
BEGIN DESCRIPTION:
WEST BRUSHY CREEK 13.0
END DESCRIPTION:
XS GIS Cut Line= 3
      2430374.98     13678324.98        2429175.       13677125.
      2428575.01       13677075.
#Sta/Elev= 30
  3307.8  271.82  3582.3  265.12  3676.6  262.88  3762.3  260.92  4137.7  254.72
  4238.7  253.84  4419.1  253.31  4552.3  253.28  4608.8  254.72  4679.6  254.99
  4736.1  255.04  4763.6  254.03  4786.1  253.46  4891.7   254.5    4920  252.53
  4976.5  250.93  4981.1  245.55  4981.6  245.05  5000.3  245.55  5001.3  249.37
  5007.3  249.37  5014.9  251.96  5073.4  252.76  5105.2  252.03  5163.2  254.65
  5282.7  257.88  5422.4  262.22  5456.4  263.87  5486.5  263.82  5606.9  267.53
#Mann= 15 ,-1 , 0
  3307.8     .07       0  3582.3     .12       0  3676.6     .07       0
  3762.3     .12       0  4137.7     .07       0  4238.7     .12       0
  4419.1     .07       0  4763.6     .12       0  4786.1      .1       0
  4981.1     .05       0  5000.3      .1       0  5073.4     .12       0
  5163.2      .1       0  5282.7     .12       0  5422.4     .07       0
Bank Sta=4981.1,5000.3
XS Rating Curve= 0 ,0
Exp/Cntr=0.3,0.1

Type RM Length L Ch R = 1 ,11010   ,328,328,328
BEGIN DESCRIPTION:
WEST BRUSHY CREEK 12.0
END DESCRIPTION:
XS GIS Cut Line= 3
      2430625.04     13677275.01        2429425.       13676775.
      2428224.99       13676975.
#Sta/Elev= 30
  3704.5   268.8  3785.3  265.51  3843.7  261.37    4003  256.29  4186.1  253.29
  4446.1  252.89  4576.1  251.85  4759.7  252.81  4906.2  253.75  4942.2  253.69
  4966.1  250.93  4985.7  245.43  4986.2  244.93  5004.9  245.43  5007.1  248.31
  5024.8  252.91  5065.4  251.06  5098.3  251.98  5154.1  251.05    5187  252.74
  5214.9   256.6  5272.8  258.96  5373.1  260.15  5470.9  258.93  5633.1  261.55
  5828.2  267.32  5856.1  266.51  5876.4  268.48  5989.5  271.55  6221.1  278.64
#Mann= 10 ,-1 , 0
  3704.5     .05       0  3785.3     .07       0  4446.1     .12       0
  4759.7     .07       0  4906.2      .1       0  4985.7     .05       0
  5004.9      .1       0  5272.8     .12       0  5373.1     .07       0
  5989.5     .12       0
Bank Sta=4985.7,5004.9
XS Rating Curve= 0 ,0
Exp/Cntr=0.3,0.1

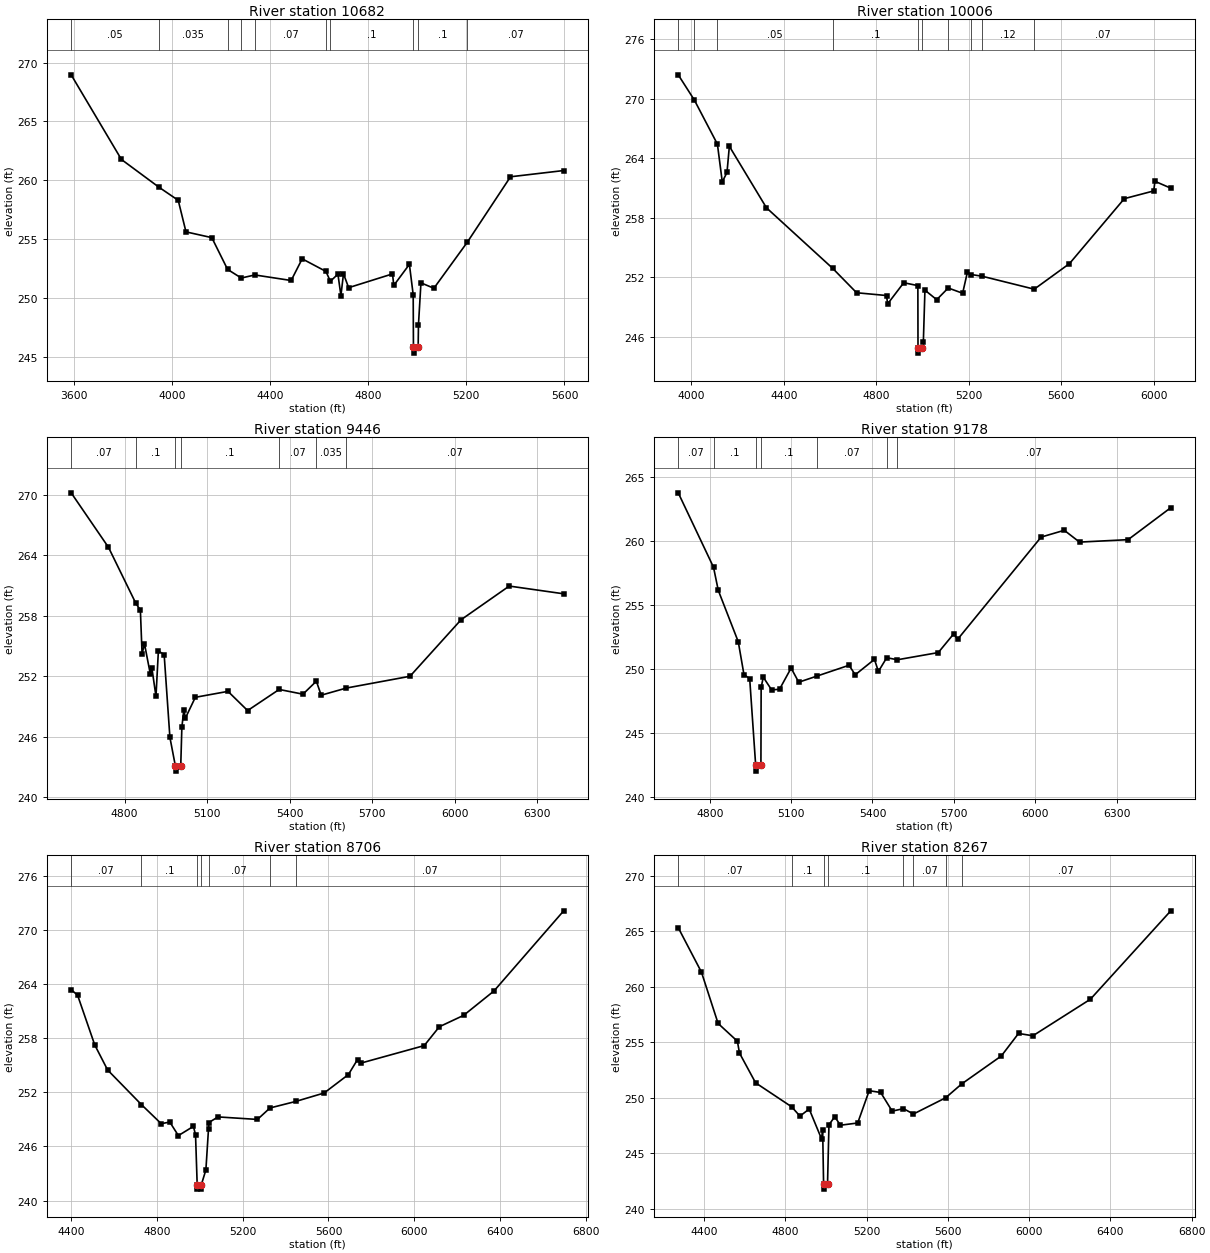
Type RM Length L Ch R = 1 ,10682   ,676,676,676
BEGIN DESCRIPTION:
H21586
END DESCRIPTION:
XS GIS Cut Line= 3
      2430859.67     13676921.05      2429459.33     13676460.32
      2428929.88     13676529.22
#Sta/Elev= 30
  3588.8  268.96  3793.7  261.77  3945.6  259.43  4025.3   258.3  4056.9  255.62
  4162.2  255.13  4226.6  252.43  4282.4   251.7  4337.6  251.96  4485.7  251.49
  4530.7  253.33  4627.6  252.26  4645.5  251.42  4676.4  252.03  4688.6  250.21
  4699.1  252.06  4720.1  250.88  4898.9  252.05  4904.2  251.07  4967.8  252.86
  4983.3  250.28  4984.3  245.82  4984.8  245.32  5003.5  245.82  5004.8  247.73
  5014.9  251.29  5067.7  250.83  5203.5  254.73    5380   260.3  5596.9  260.83
#Mann= 10 ,-1 , 0
  3588.8     .05       0  3945.6    .035       0  4226.6     .07       0
  4282.4    .035       0  4337.6     .07       0  4627.6     .12       0
  4645.5      .1       0  4984.3     .05       0  5003.5      .1       0
  5203.5     .07       0
Bank Sta=4984.3,5003.5
XS Rating Curve= 0 ,0
Exp/Cntr=0.3,0.1

Type RM Length L Ch R = 1 ,10006   ,560,560,560
BEGIN DESCRIPTION:
H21585
END DESCRIPTION:
XS GIS Cut Line= 3
      2431011.96     13676424.03      2429774.94     13676180.98
      2428948.95     13676452.69
#Sta/Elev= 30
  3942.8  272.42  4012.4  269.88  4112.2  265.43  4133.3  261.62  4153.7  262.58
  4163.9  265.21  4324.3  259.01  4610.8   252.9  4714.2  250.44  4843.6  250.16
  4848.6  249.32  4918.1  251.45  4979.2  251.16  4979.8  244.85  4980.3  244.35
    4999  244.85  5002.9  245.45  5009.8   250.7  5060.7  249.74  5110.5  250.92
  5172.8  250.39  5193.2  252.49  5209.6  252.28  5258.3   252.1  5482.5   250.8
    5635  253.38  5872.1  259.93  5999.3  260.71  6004.6  261.68    6073  260.99
#Mann= 10 ,-1 , 0
  3942.8     .05       0  4012.4    .035       0  4112.2     .05       0
  4610.8      .1       0  4979.8     .05       0    4999      .1       0
  5110.5     .07       0  5209.6    .035       0  5258.3     .12       0
  5482.5     .07       0
Bank Sta=4979.8,4999
XS Rating Curve= 0 ,0
Exp/Cntr=0.3,0.1

Type RM Length L Ch R = 1 ,9446    ,268,268,268
BEGIN DESCRIPTION:
WEST BRUSHY CREEK 11.0
END DESCRIPTION:
XS GIS Cut Line= 3
      2430425.04     13675524.97      2429991.58     13675827.52
      2428880.44     13676426.49
#Sta/Elev= 30
    4606  270.23  4741.7  264.81  4840.5  259.28  4857.7  258.55  4863.8  254.22
  4872.6  255.22  4893.5  252.25  4899.6  252.79  4914.4  249.99  4923.1   254.5
  4944.1  254.15    4965  245.92    4985  243.06  4985.5  242.56  5004.4  243.06
  5008.5  246.91  5015.6  248.67  5021.7  247.85  5057.5   249.9  5176.2  250.49
  5247.6  248.58  5362.3  250.68  5448.8  250.21  5497.5   251.5  5515.2  250.11
  5606.6  250.82    5838  251.99  6023.7  257.61  6198.9  260.96  6396.9  260.19
#Mann= 7 ,-1 , 0
    4606     .07       0  4840.5      .1       0    4985     .05       0
  5004.4      .1       0  5362.3     .07       0  5497.5    .035       0
  5606.6     .07       0
Bank Sta=4985,5004.4
XS Rating Curve= 0 ,0
Exp/Cntr=0.3,0.1

Type RM Length L Ch R = 1 ,9178    ,472,472,472
BEGIN DESCRIPTION:
WEST BRUSHY CREEK 10.0
END DESCRIPTION:
XS GIS Cut Line= 3
        2430175.       13675525.        2429875.       13675625.
      2428675.02     13676524.98
#Sta/Elev= 30
  4683.8  263.74  4813.9  257.94  4831.4  256.14  4905.2  252.13  4926.2  249.57
  4947.3  249.26  4969.2  242.55  4969.7  242.05  4988.7  242.55  4989.5  248.57
  4997.4  249.37  5028.2  248.38  5057.3  248.43    5100  250.08  5128.2  248.98
  5195.6  249.46  5313.6   250.3  5336.5  249.56  5407.3  250.76  5421.9  249.82
  5452.7  250.89    5492  250.73  5642.7  251.29    5700  252.76  5713.6  252.31
  6021.9  260.29  6107.3  260.82  6163.6   259.9  6342.7  260.09    6500  262.58
#Mann= 7 ,-1 , 0
  4683.8     .07       0  4813.9      .1       0  4969.2     .05       0
  4988.7      .1       0  5195.6     .07       0  5452.7    .035       0
    5492     .07       0
Bank Sta=4969.2,4988.7
XS Rating Curve= 0 ,0
Exp/Cntr=0.3,0.1

Type RM Length L Ch R = 1 ,8706    ,439,439,439
BEGIN DESCRIPTION:
WEST BRUSHY CREEK 9.0
END DESCRIPTION:
XS GIS Cut Line= 3
      2430124.98       13675375.        2429525.       13675375.
      2428325.02     13676574.98
#Sta/Elev= 30
  4399.9  263.37  4429.9  262.75  4509.9  257.24  4569.9  254.47  4727.7  250.63
  4819.9  248.52  4859.9   248.7  4899.9   247.2  4969.9  248.22  4979.9   247.3
  4987.6  241.77  4988.1  241.27  5006.6  241.27  5007.1  241.77  5028.2   243.4
  5040.5  247.98  5042.3  248.65  5084.7  249.27  5268.6  248.99  5327.1  250.26
  5446.7  250.98  5579.7  251.92  5692.8  253.96  5735.3  255.62  5749.4  255.22
  6046.4  257.17  6117.1  259.26  6230.2  260.52  6371.7  263.22  6696.9   272.1
#Mann= 7 ,-1 , 0
  4399.9     .07       0  4727.7      .1       0  4987.6     .05       0
  5007.1      .1       0  5040.5     .07       0  5327.1    .035       0
  5446.7     .07       0
Bank Sta=4987.6,5007.1
XS Rating Curve= 0 ,0
Exp/Cntr=0.3,0.1

Type RM Length L Ch R = 1 ,8267    ,471,471,471
BEGIN DESCRIPTION:
WEST BRUSHY CREEK 8.0
END DESCRIPTION:
XS GIS Cut Line= 3
      2430174.98     13675174.99        2429475.       13674975.
      2428275.03     13676174.97
#Sta/Elev= 30
  4272.1  265.34  4386.5  261.33  4468.4  256.71  4563.3  255.11  4573.7  254.04
    4653  251.36  4830.4   249.2  4871.4  248.36  4916.9     249    4978  246.29
  4983.2  247.12  4987.7  242.28  4988.2  241.78  5007.2  242.28  5014.2  247.58
  5042.5   248.3  5070.8  247.54  5155.7  247.74  5212.2  250.65  5268.8  250.49
  5325.4  248.81  5381.1  249.03  5430.2  248.55  5588.6  250.01  5667.7  251.26
  5862.8  253.78  5947.6  255.81  6018.3   255.6  6301.2  258.89  6697.1  266.86
#Mann= 8 ,-1 , 0
  4272.1     .07       0  4830.4      .1       0  4987.7     .05       0
  5007.2      .1       0  5381.1     .12       0  5430.2     .07       0
  5588.6    .035       0  5667.7     .07       0
Bank Sta=4987.7,5007.2
XS Rating Curve= 0 ,0
Exp/Cntr=0.3,0.1