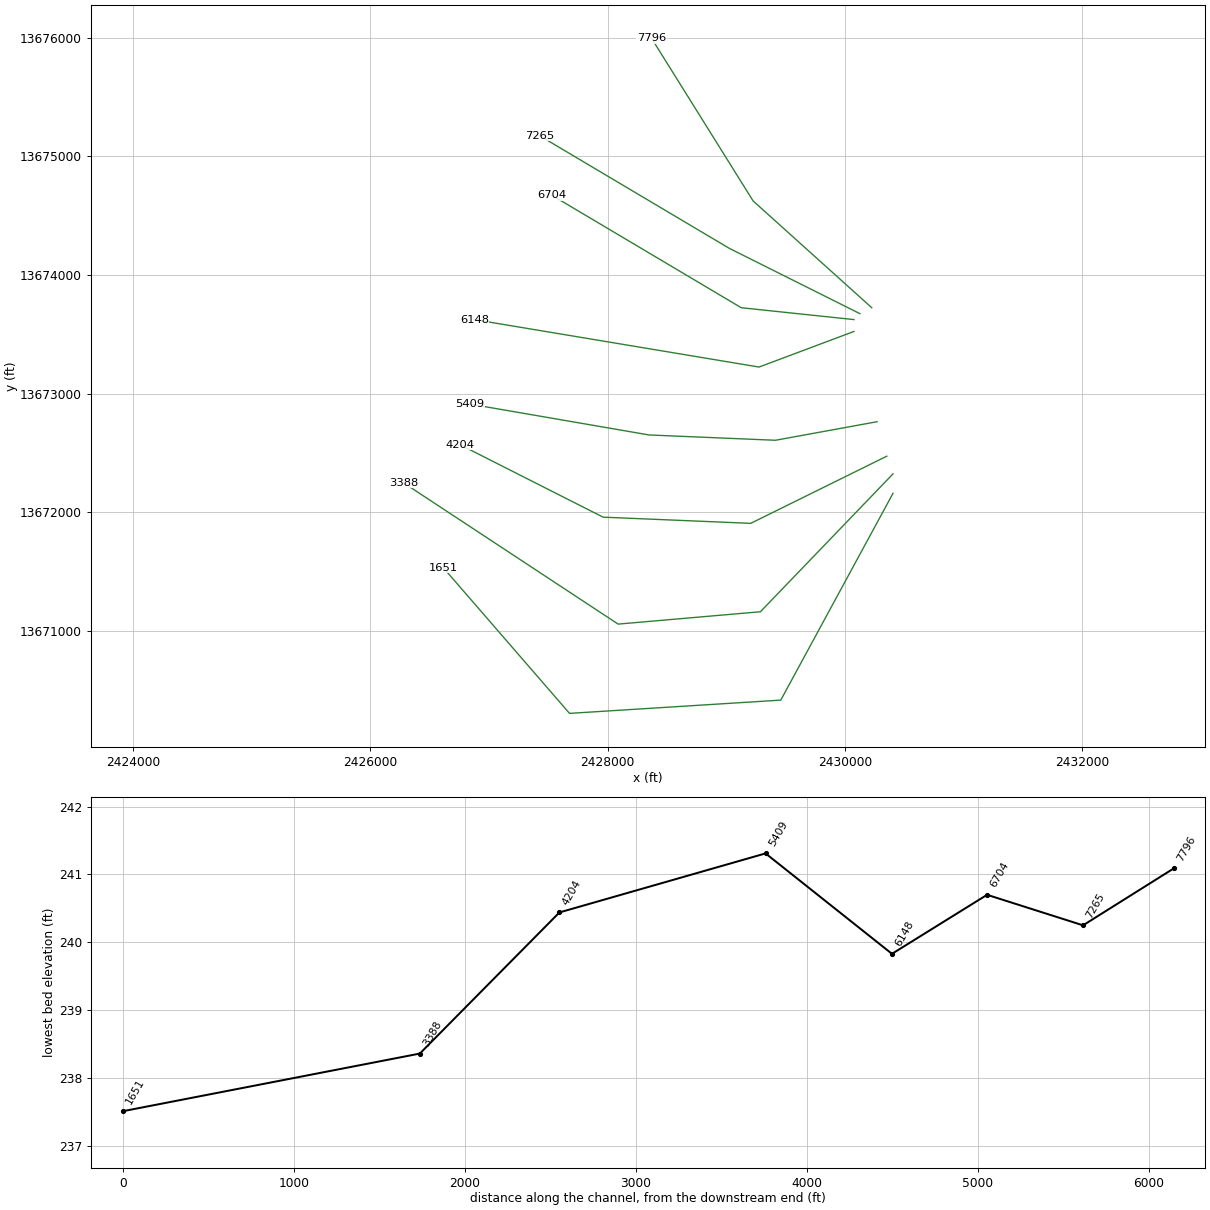
HEC-RAS study WEST BRUSHY CREEK.prj: WEST BRUSHY CREEK Base Level Engineering

--- WEST BRUSHY CREEK.g01 (geometry) --- (continued)

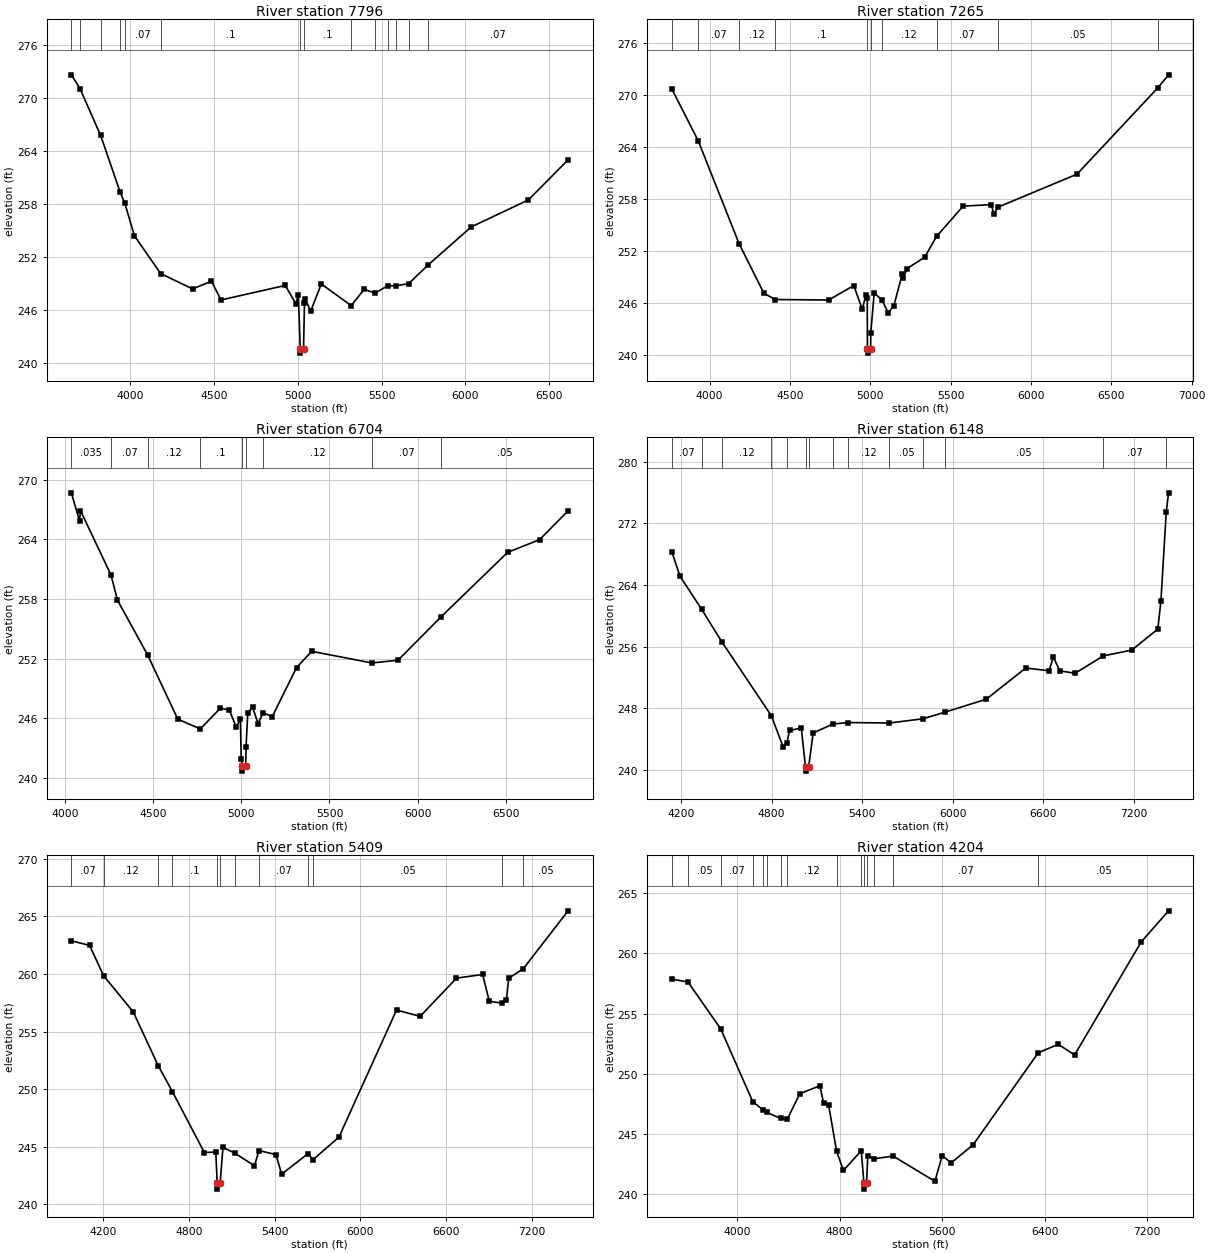
Type RM Length L Ch R = 1 ,7796    ,531,531,531
BEGIN DESCRIPTION:
WEST BRUSHY CREEK 7.0
END DESCRIPTION:
XS GIS Cut Line= 3
      2430224.98     13673725.02        2429225.       13674625.
      2428369.14     13675995.47
#Sta/Elev= 30
  3650.6   272.6  3702.1  271.04    3825  265.74  3941.2  259.32  3969.2  258.07
  4026.2  254.38  4182.7   250.1    4373  248.36  4485.8  249.23  4542.6  247.11
  4925.3  248.75  4988.8  246.69  5003.6  247.69  5015.1  241.59  5015.6  241.09
  5034.6  241.59  5040.2  246.75  5046.1   247.2  5076.7  245.81  5140.4  248.92
  5318.5  246.47  5396.4  248.32  5460.6  247.88  5535.7  248.71  5583.4  248.71
  5660.7  248.95  5774.8  251.03  6033.4  255.37  6375.3  258.44  6611.7  262.98
#Mann= 14 ,-1 , 0
  3650.6     .07       0  3702.1    .035       0    3825     .07       0
  3941.2     .05       0  3969.2     .07       0  4182.7      .1       0
  5015.1     .05       0  5034.6      .1       0  5318.5     .12       0
  5460.6      .1       0  5535.7     .12       0  5583.4     .07       0
  5660.7    .035       0  5774.8     .07       0
Bank Sta=5015.1,5034.6
XS Rating Curve= 0 ,0
Exp/Cntr=0.3,0.1

Type RM Length L Ch R = 1 ,7265    ,561,561,561
BEGIN DESCRIPTION:
WEST BRUSHY CREEK 6.0
END DESCRIPTION:
XS GIS Cut Line= 3
      2430125.03     13673674.98        2429025.       13674225.
      2427424.96     13675175.02
#Sta/Elev= 30
  3765.5  270.75    3930  264.75  4184.1  252.88  4338.5  247.15  4409.6  246.44
    4741  246.38  4897.5  248.05  4950.7  245.31    4973  246.98  4981.4  246.66
  4982.5  240.75    4983  240.25  5002.6  240.75  5003.2  242.54  5024.6  247.18
  5073.1  246.39  5111.7  244.89  5147.3  245.74    5200  249.44  5205.8  248.87
    5228     250  5338.3  251.31  5412.5  253.72  5577.9  257.22  5753.3   257.4
  5768.9  256.29  5794.5   257.1  6286.3  260.91  6790.1  270.89  6856.2  272.38
#Mann= 10 ,-1 , 0
  3765.5    .035       0    3930     .07       0  4184.1     .12       0
  4409.6      .1       0  4982.5     .05       0  5002.6      .1       0
  5073.1     .12       0  5412.5     .07       0  5794.5     .05       0
  6790.1     .07       0
Bank Sta=4982.5,5002.6
XS Rating Curve= 0 ,0
Exp/Cntr=0.3,0.1

Type RM Length L Ch R = 1 ,6704    ,556,556,556
BEGIN DESCRIPTION:
WEST BRUSHY CREEK 5.0
END DESCRIPTION:
XS GIS Cut Line= 3
      2430074.96       13673625.        2429125.       13673725.
      2427524.99     13674675.01
#Sta/Elev= 30
  4036.8  268.69  4083.3  265.85  4088.3  266.91  4261.3  260.43  4298.2  257.89
  4469.7  252.36  4640.1  245.93  4767.5  244.94  4881.4  247.03  4931.7  246.86
  4971.9  245.11  4994.9  245.96  4999.8  241.87  5005.2   241.2  5005.7   240.7
  5025.3   241.2    5027  243.16  5036.8  246.54  5064.1  247.14  5095.3  245.48
  5124.5  246.58  5175.2  246.17  5313.5  251.12  5399.2  252.75  5739.8  251.58
  5888.3  251.85  6133.4  256.23  6509.9   262.7    6691  263.98  6852.8  266.88
#Mann= 9 ,-1 , 0
  4036.8    .035       0  4261.3     .07       0  4469.7     .12       0
  4767.5      .1       0  5005.2     .05       0  5025.3      .1       0
  5124.5     .12       0  5739.8     .07       0  6133.4     .05       0
Bank Sta=5005.2,5025.3
XS Rating Curve= 0 ,0
Exp/Cntr=0.3,0.1

Type RM Length L Ch R = 1 ,6148    ,739,739,739
BEGIN DESCRIPTION:
WEST BRUSHY CREEK 4.0
END DESCRIPTION:
XS GIS Cut Line= 3
      2430075.01       13673525.        2429275.       13673225.
      2426875.02       13673625.
#Sta/Elev= 30
  4140.3  268.31  4193.7  265.17  4338.1  260.83    4473  256.57  4798.8  247.03
  4877.2  242.96  4902.8  243.54  4919.1  245.12  4997.2  245.42    5025  240.33
  5025.5  239.83  5045.5  240.33  5075.8  244.79  5206.9  245.95  5307.1  246.14
  5580.8  246.08  5803.7  246.63  5948.5  247.49  6221.4  249.17  6482.5  253.22
  6637.1  252.86  6664.9  254.66    6708  252.85  6809.4  252.54  6996.8   254.8
  7184.5  255.55  7356.9  258.28  7377.1  261.89  7412.5  273.46  7427.8  275.97
#Mann= 14 ,-1 , 0
  4140.3     .07       0  4338.1    .035       0    4473     .12       0
  4798.8     .07       0  4902.8      .1       0    5025     .05       0
  5045.5      .1       0  5206.9     .07       0  5307.1     .12       0
  5580.8     .05       0  5803.7     .07       0  5948.5     .05       0
  6996.8     .07       0  7412.5    .033       0
Bank Sta=5025,5045.5
XS Rating Curve= 0 ,0
Exp/Cntr=0.3,0.1

Type RM Length L Ch R = 1 ,5409    ,1205,1205,1205
BEGIN DESCRIPTION:
H21584
END DESCRIPTION:
XS GIS Cut Line= 4
      2430270.03     13672764.35      2429413.36     13672607.92
      2428348.11     13672652.61      2426835.94     13672913.33
#Sta/Elev= 30
  3979.4  262.88  4106.5  262.49  4204.2  259.86  4411.5  256.71  4585.7  252.05
  4685.2  249.79  4908.6  244.49  4988.7  244.53  4998.5  241.81    4999  241.31
    5019  241.81  5038.8  244.94    5121  244.44    5259  243.34  5290.3  244.66
  5409.1  244.31  5449.1  242.61  5634.2   244.4  5667.5  243.86  5849.3  245.83
  6251.8  256.87  6416.8  256.32  6670.9  259.64  6853.2  259.96  6900.2  257.64
  6988.2  257.47  7019.9  257.77  7035.8  259.64  7136.4  260.44  7450.9  265.49
#Mann= 12 ,-1 , 0
  3979.4     .07       0  4204.2     .12       0  4585.7    .035       0
  4685.2      .1       0  4998.5     .05       0    5019      .1       0
    5121     .12       0  5290.3     .07       0  5634.2      .1       0
  5667.5     .05       0  6988.2     .07       0  7136.4     .05       0
Bank Sta=4998.5,5019
XS Rating Curve= 0 ,0
Exp/Cntr=0.3,0.1

Type RM Length L Ch R = 1 ,4204    ,816,816,816
BEGIN DESCRIPTION:
H21583
END DESCRIPTION:
XS GIS Cut Line= 4
      2430351.94     13672473.81      2429204.78     13671907.68
      2427960.74     13671959.83      2426754.63     13672570.33
#Sta/Elev= 30
  3490.8  257.87  3617.3  257.63  3872.7  253.73  4122.7  247.69    4200  247.04
  4230.9  246.81  4339.2  246.31  4391.6  246.24  4489.5  248.36  4646.7  249.02
  4674.7  247.58    4714  247.45  4776.5  243.58  4830.1  241.99  4969.1  243.63
  4989.7  240.94  4990.2  240.44  5010.3  240.94    5020   243.2  5067.7  242.96
  5217.7  243.18  5543.6  241.09  5600.6  243.22  5670.6  242.62  5840.8  244.11
  6350.5  251.76  6505.9  252.46    6634  251.58  7153.6  260.96    7367  263.54
#Mann= 15 ,-1 , 0
  3490.8     .07       0  3617.3     .05       0  3872.7     .07       0
  4122.7     .12       0    4200    .035       0  4230.9     .12       0
  4339.2     .07       0  4391.6     .12       0  4776.5      .1       0
  4969.1     .12       0  4989.7     .05       0  5010.3     .12       0
  5067.7     .05       0  5217.7     .07       0  6350.5     .05       0
Bank Sta=4989.7,5010.3
XS Rating Curve= 0 ,0
Exp/Cntr=0.3,0.1

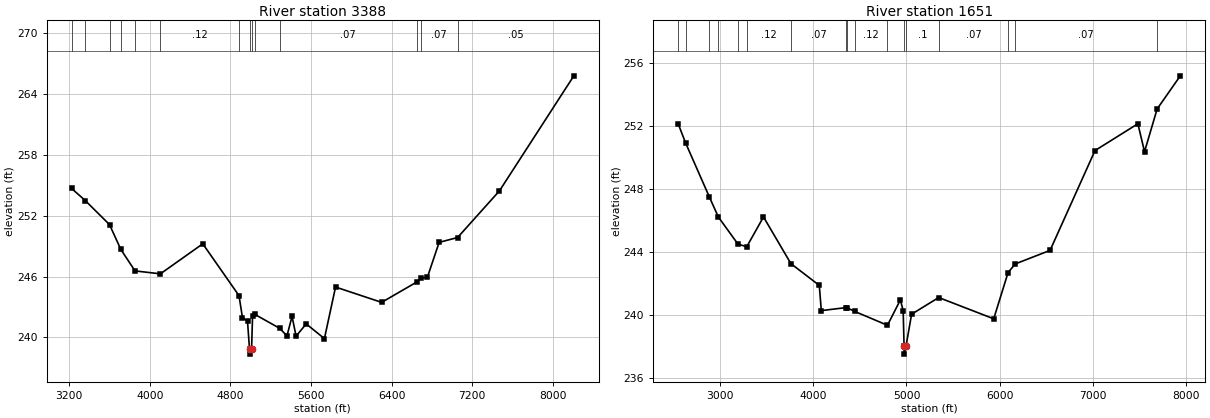
Type RM Length L Ch R = 1 ,3388    ,1737,1737,1737
BEGIN DESCRIPTION:
H21582
END DESCRIPTION:
XS GIS Cut Line= 4
      2430404.14     13672324.87      2429286.72     13671162.75
      2428087.38     13671058.46      2426278.86     13672249.25
#Sta/Elev= 30
  3225.7  254.68  3361.9  253.48  3601.3  251.12  3713.8  248.67  3854.3  246.56
    4106  246.27  4526.4  249.23  4885.8  244.12  4919.9  241.96  4970.1   241.6
  4989.9  238.86  4990.4  238.36  5010.5  238.86  5020.3  242.14    5042  242.28
  5288.1  240.91  5361.6  240.16  5411.8  242.08  5451.9  240.13  5552.3  241.34
    5733  239.89  5843.4  244.97  6300.6  243.46  6650.3  245.47  6688.9  245.82
  6755.4  245.96  6870.7  249.37  7054.1  249.85  7469.4  254.45  8207.1  265.78
#Mann= 14 ,-1 , 0
  3225.7     .07       0  3361.9     .05       0  3601.3     .07       0
  3713.8    .035       0  3854.3     .07       0    4106     .12       0
  4885.8      .1       0  4989.9     .05       0  5010.5      .1       0
    5042     .05       0  5288.1     .07       0  6650.3     .12       0
  6688.9     .07       0  7054.1     .05       0
Bank Sta=4989.9,5010.5
XS Rating Curve= 0 ,0
Exp/Cntr=0.3,0.1

Type RM Length L Ch R = 1 ,1651    ,0,0,0
BEGIN DESCRIPTION:
H21581
END DESCRIPTION:
XS GIS Cut Line= 4
       2430404.1     13672160.94      2429458.05     13670417.82
      2427677.67     13670306.08      2426612.41     13671535.22
#Sta/Elev= 30
  2547.1  252.13  2626.9  250.91    2881   247.5  2978.9  246.21  3189.5  244.49
  3284.2  244.32  3464.1  246.21  3758.3  243.25  4063.3  241.87  4085.1  240.27
  4350.2  240.46  4365.2  240.44  4442.9  240.22  4795.5  239.34  4934.2  240.95
  4964.3  240.27  4973.9  238.01  4974.4  237.51  4994.8  238.01  5054.5  240.04
  5345.7   241.1  5936.8  239.75  6090.8  242.68  6167.7  243.23  6542.1  244.09
  7024.6  250.42  7485.2  252.12  7556.5  250.35  7692.1  253.06  7940.8  255.16
#Mann= 17 ,-1 , 0
  2547.1     .07       0  2626.9     .05       0    2881    .035       0
  2978.9     .05       0  3189.5     .07       0  3284.2     .12       0
  3758.3     .07       0  4350.2     .12       0  4365.2     .07       0
  4442.9     .12       0  4795.5      .1       0  4973.9     .05       0
  4994.8      .1       0  5345.7     .07       0  6090.8     .05       0
  6167.7     .07       0  7692.1     .05       0
Bank Sta=4973.9,4994.8
XS Rating Curve= 0 ,0
Exp/Cntr=0.3,0.1

Chan Stop Cuts=-1
Use User Specified Reach Order=0
Composite Channel Slope=5