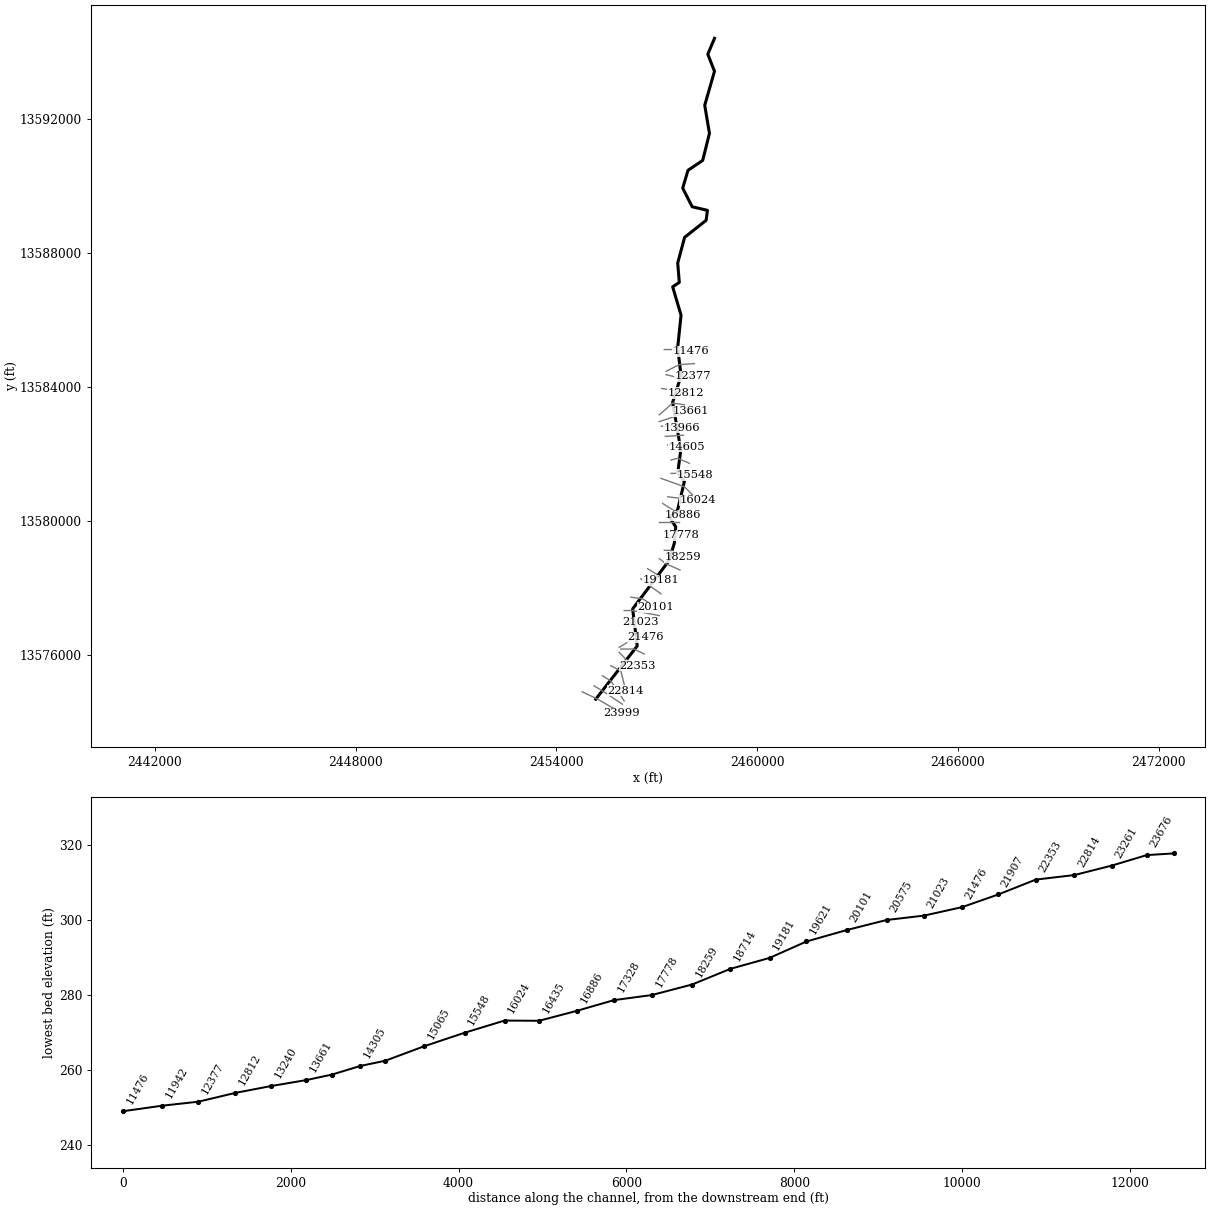
--- ANDERSON CREEK.prj (project) ---

Proj Title=ANDERSON CREEK Base Level Engineering
Current Plan=p01
Default Exp/Contr=0.3,0.1
English Units
Geom File=g01
Flow File=f01
Plan File=p01
Y Axis Title=Elevation
X Axis Title(PF)=Main Channel Distance
X Axis Title(XS)=Station
BEGIN DESCRIPTION:
ANDERSON CREEK
END DESCRIPTION:
DSS Export Rating Curves= 0
DSS Export Rating Curve Sorted= 0
DSS Export Volume Flow Curves= 0
DXF OffsetX= 0
DXF OffsetY= 0
DXF ScaleX= 1
DXF ScaleY= 10

--- ANDERSON CREEK.p01 (plan) ---

Plan Title=Multiple Run
Short Identifier=Multiple
Geom File=g01
Flow File=f01
Subcritical Flow
K Sum by GR= 0
Std Step Tol= 0.01
Critical Tol= 0.01
Num of Std Step Trials= 20
Max Error Tol= 0.3
Flow Tol Ratio= 0.001
Split Flow NTrial= 30
Split Flow Tol= 0.02
Split Flow Ratio= 0.02
Log Output Level= 0
Friction Slope Method= 1
Unsteady Friction Slope Method= 2
Unsteady Bridges Friction Slope Method= 1
Parabolic Critical Depth
Global Vel Dist=  1 , 1 , 1
Global Log Level= 0
CheckData=True
Encroach Param= -1, 0, 0, 0
BEGIN DESCRIPTION:
Multiple Run
END DESCRIPTION:

--- ANDERSON CREEK.f01 (steady flow) ---

Flow Title=Multiple
Number of Profiles=7
Profile Names=10-year,25-year,50-year,1pct_min,100-year,1pct_plu,500-year
River Rch & RM= ANDERSON CREEK,Reach-1,23999
     629    1017    1368     891    1777    3547    2974
River Rch & RM= ANDERSON CREEK,Reach-1,20575
     842    1381    1874    1231    2456    4900    4178
River Rch & RM= ANDERSON CREEK,Reach-1,13661
    1295    2171    2992    1992    3974    7928    6951
River Rch & RM= ANDERSON CREEK,Reach-1,12812
    1733    2943    4091    2746    5478   10930    9740
River Rch & RM= ANDERSON CREEK,Reach-1,11942
    1928    3281    4566    3066    6118   12207   10893
River Rch & RM= ANDERSON CREEK,Reach-1,8284
    1959    3315    4597    3073    6132   12235   10822
Boundary for River Rch & Prof#=ANDERSON CREEK,Reach-1,1
Up Type=0
Dn Type=3
Dn Slope=0.005
Boundary for River Rch & Prof#=ANDERSON CREEK,Reach-1,2
Up Type=0
Dn Type=3
Dn Slope=0.005
Boundary for River Rch & Prof#=ANDERSON CREEK,Reach-1,3
Up Type=0
Dn Type=3
Dn Slope=0.005
Boundary for River Rch & Prof#=ANDERSON CREEK,Reach-1,4
Up Type=0
Dn Type=3
Dn Slope=0.005
Boundary for River Rch & Prof#=ANDERSON CREEK,Reach-1,5
Up Type=0
Dn Type=3
Dn Slope=0.005
Boundary for River Rch & Prof#=ANDERSON CREEK,Reach-1,6
Up Type=0
Dn Type=3
Dn Slope=0.005
Boundary for River Rch & Prof#=ANDERSON CREEK,Reach-1,7
Up Type=0
Dn Type=3
Dn Slope=0.005

--- ANDERSON CREEK.g01 (geometry) ---

Geom Title=Existing Conditions
Program Version=4.10

River Reach=ANDERSON CREEK  ,Reach-1
Reach XY= 30
        2455175.       13574675.       2456415.7     13576268.33
      2456278.13     13577373.37      2457367.17     13578818.81
       2457523.8      13579335.5      2457567.19     13579828.41
      2457375.49     13580114.51      2457621.39      13580326.5
      2457825.51     13581185.21      2457626.04     13581435.44
      2457717.47     13582125.01      2457474.59       13583550.
      2457724.61     13584340.16      2457624.55     13585185.19
       2457725.4       13586150.      2457474.38      13587000.3
      2457672.95     13587130.84      2457625.37     13587709.73
      2457831.06     13588477.23      2458474.07     13588985.48
      2458514.04       13589285.      2458058.29     13589391.29
      2457774.68     13589950.11       2457932.5     13590481.05
      2458371.47     13590776.45      2458573.78      13591585.5
      2458432.78      13592424.9       2458724.5     13593440.22
      2458524.59       13593950.        2458725.       13594425.

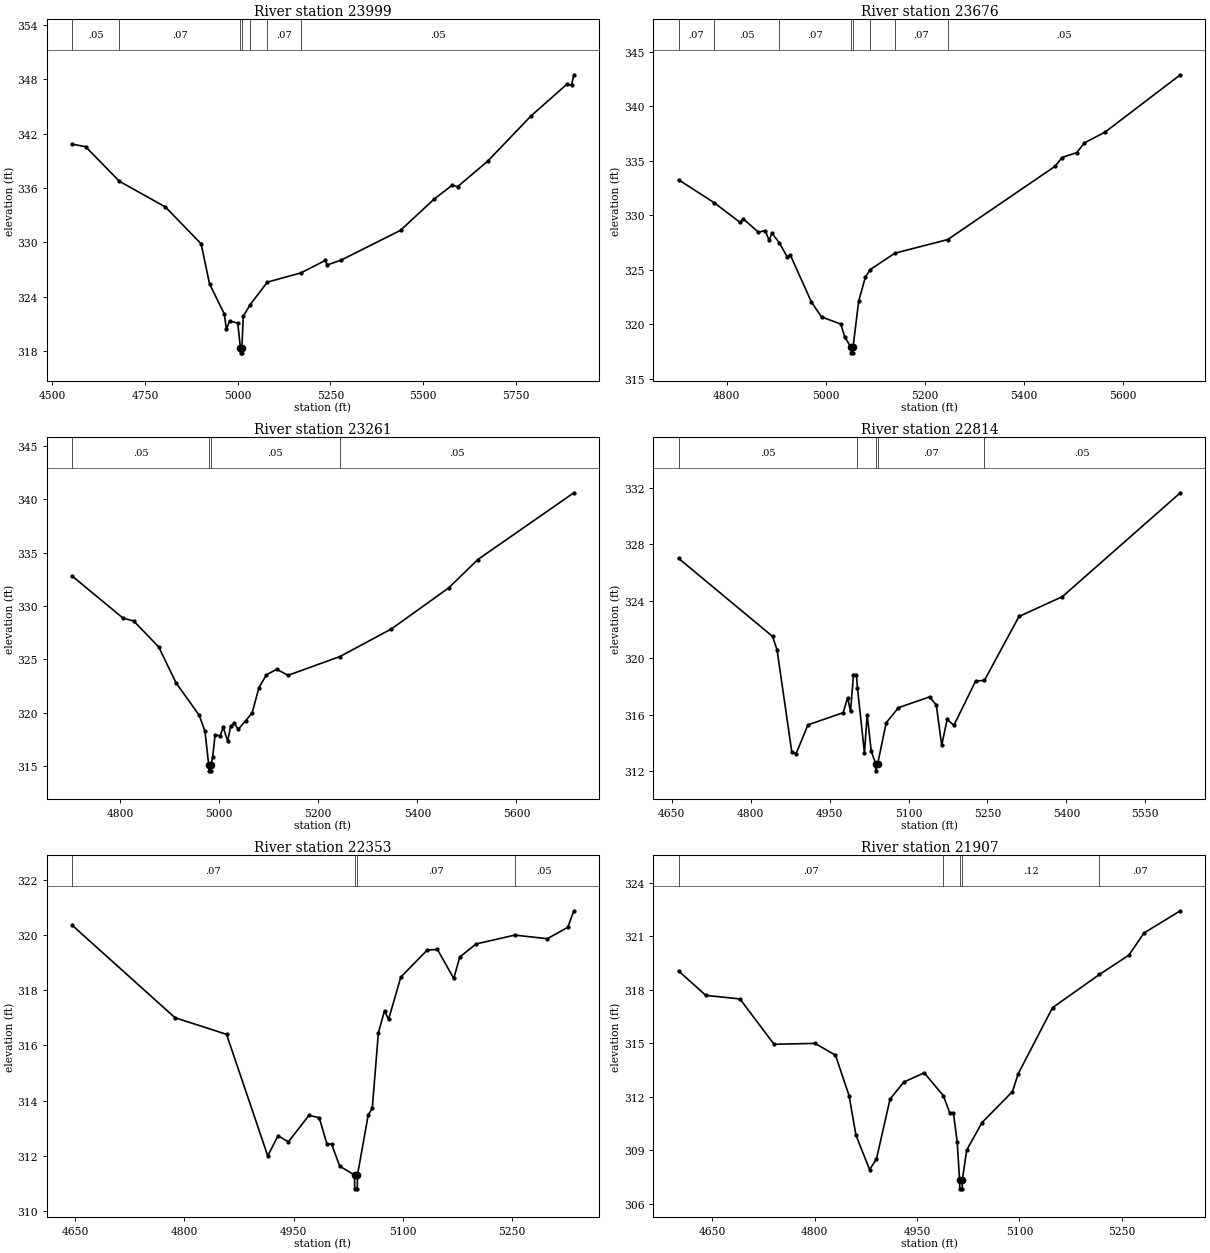
Type RM Length L Ch R = 1 ,23999   ,323,323,323
BEGIN DESCRIPTION:
X18047
END DESCRIPTION:
XS GIS Cut Line= 3
      2454771.05     13574897.56      2455220.81     13574683.56
       2455960.4     13574252.14
#Sta/Elev= 30
  4552.9  340.86  4589.4  340.58  4680.6  336.76  4804.8  333.92  4901.2  329.85
  4923.9  325.43  4963.8   322.1  4969.4   320.4  4978.1  321.33  5000.2  321.09
  5007.3  318.31  5007.5  317.81    5011  317.81  5011.3  318.31  5014.8  321.84
  5033.5  323.12  5079.9  325.62  5170.6  326.64    5236  328.01  5241.8  327.52
    5279  328.05  5439.4  331.34  5529.5  334.77  5578.3  336.31    5594  336.18
  5674.2  338.96  5791.7  343.98  5887.6  347.45    5901  347.38  5907.2  348.52
#Mann= 7 ,-1 , 0
  4552.9     .05       0  4680.6     .07       0  5007.3     .05       0
  5011.3     .07       0  5033.5     .12       0  5079.9     .07       0
  5170.6     .05       0
Bank Sta=5007.3,5011.3
XS Rating Curve= 0 ,0
Exp/Cntr=0.3,0.1

Type RM Length L Ch R = 1 ,23676   ,415,415,415
BEGIN DESCRIPTION:
ANDERSON CREEK 46.0
END DESCRIPTION:
XS GIS Cut Line= 3
      2455125.03     13575074.98        2455375.       13574925.
      2455974.98     13574525.01
#Sta/Elev= 30
  4703.2  333.25  4775.3  331.14  4827.6  329.33  4833.4  329.68  4864.5  328.43
  4878.1  328.59  4885.9   327.7  4891.7  328.35  4906.2  327.48  4922.8  326.15
  4928.6  326.36  4971.4  322.02  4991.8  320.66  5030.8     320  5038.3  318.84
  5051.3  317.86  5051.6  317.36  5055.1  317.36  5055.3  317.86  5066.8  322.12
  5080.3  324.32  5090.2  325.01  5139.8  326.51  5246.4  327.76  5463.4   334.5
    5477  335.29    5507  335.75    5522  336.63  5564.1  337.63  5715.8  342.89
#Mann= 8 ,-1 , 0
  4703.2     .07       0  4775.3     .05       0  4906.2     .07       0
  5051.3     .05       0  5055.3     .07       0  5090.2     .12       0
  5139.8     .07       0  5246.4     .05       0
Bank Sta=5051.3,5055.3
XS Rating Curve= 0 ,0
Exp/Cntr=0.3,0.1

Type RM Length L Ch R = 1 ,23261   ,447,447,447
BEGIN DESCRIPTION:
ANDERSON CREEK 45.0
END DESCRIPTION:
XS GIS Cut Line= 3
      2455375.03     13575374.98        2455625.       13575225.
      2456024.99     13574625.02
#Sta/Elev= 30
  4703.2  332.81  4806.2  328.86  4827.6   328.6  4878.1  326.16  4913.1   322.8
  4959.7  319.78  4971.4  318.27  4979.1  315.07  4979.4  314.57  4982.9  314.57
  4983.1  315.07  4986.9  315.83  4991.8  317.94  5002.2  317.85  5008.2  318.66
  5017.2  317.34  5023.3  318.77  5030.8  319.01  5038.3  318.46  5053.3  319.24
  5066.8  320.02  5080.3  322.36  5095.4  323.56  5116.4  324.08  5138.9  323.51
  5243.8  325.27  5347.8  327.86  5463.4   331.7    5522  334.35  5715.8   340.6
#Mann= 4 ,-1 , 0
  4703.2     .05       0  4979.1     .05       0  4983.1     .05       0
  5243.8     .05       0
Bank Sta=4979.1,4983.1
XS Rating Curve= 0 ,0
Exp/Cntr=0.3,0.1

Type RM Length L Ch R = 1 ,22814   ,461,461,461
BEGIN DESCRIPTION:
ANDERSON CREEK 44.0
END DESCRIPTION:
XS GIS Cut Line= 3
        2455625.       13575675.        2455925.       13575525.
      2456075.01     13574924.97
#Sta/Elev= 30
  4662.8  327.01  4841.7   321.5  4850.1  320.55    4878  313.39  4886.4  313.25
  4908.8  315.27  4975.8  316.13  4984.2  317.18  4989.8  316.22  4995.4  318.81
  5000.8  318.81    5003  317.85  5016.2   313.3  5021.4  315.97  5029.1  313.43
  5037.4  312.53  5037.7  312.03  5041.4  312.53  5057.5  315.41  5080.7  316.48
  5139.9  317.24  5152.8  316.67  5163.1  313.83  5173.4  315.65  5186.3  315.24
  5227.6  318.36  5244.2   318.4    5310  322.91  5392.5  324.31  5616.7  331.63
#Mann= 5 ,-1 , 0
  4662.8     .05       0    5003     .07       0  5037.4     .05       0
  5041.4     .07       0  5244.2     .05       0
Bank Sta=5037.4,5041.4
XS Rating Curve= 0 ,0
Exp/Cntr=0.3,0.1

Type RM Length L Ch R = 1 ,22353   ,446,446,446
BEGIN DESCRIPTION:
ANDERSON CREEK 43.0
END DESCRIPTION:
XS GIS Cut Line= 3
        2455875.       13576075.        2456125.       13575825.
      2456425.03     13575674.98
#Sta/Elev= 30
  4645.9  320.35  4787.3     317    4858   316.4  4914.6     312  4928.7  312.73
  4942.9  312.51  4971.2  313.47  4985.3  313.38  4995.9  312.43  5002.2  312.43
  5013.4  311.63  5033.8  311.31    5034  310.81  5037.5  310.81  5037.8  311.31
  5052.6  313.49  5058.1  313.72  5066.5  316.46  5074.9  317.25  5080.5  316.94
  5097.3  318.47  5133.6  319.45  5147.6  319.47    5170  318.42  5178.3   319.2
  5200.7  319.67  5253.8  319.99  5298.5  319.86  5326.5  320.27  5334.9  320.87
#Mann= 4 ,-1 , 0
  4645.9     .07       0  5033.8     .05       0  5037.8     .07       0
  5253.8     .05       0
Bank Sta=5033.8,5037.8
XS Rating Curve= 0 ,0
Exp/Cntr=0.3,0.1

Type RM Length L Ch R = 1 ,21907   ,431,431,431
BEGIN DESCRIPTION:
ANDERSON CREEK 42.0
END DESCRIPTION:
XS GIS Cut Line= 3
      2455925.03       13576175.        2456325.       13576175.
      2456625.02     13576024.99
#Sta/Elev= 30
  4600.4  319.05  4640.4  317.68  4690.4  317.48  4740.4  314.94  4800.4  314.99
  4830.4  314.33  4850.4  312.05  4860.4  309.85  4880.4  307.92  4890.4   308.5
  4910.4  311.87  4930.4  312.82  4960.4  313.34  4988.5  312.06  4997.9  311.09
  5003.2  311.09  5008.8  309.47  5012.3  307.34  5012.6  306.84  5016.1  306.84
  5016.3  307.34  5022.7  309.01  5045.1  310.55  5089.8  312.29  5098.2  313.29
  5148.5  316.99  5217.3  318.85  5260.3  319.93  5282.7  321.18  5335.8  322.42
#Mann= 5 ,-1 , 0
  4600.4     .07       0  4988.5     .12       0  5012.3     .05       0
  5016.3     .12       0  5217.3     .07       0
Bank Sta=5012.3,5016.3
XS Rating Curve= 0 ,0
Exp/Cntr=0.3,0.1

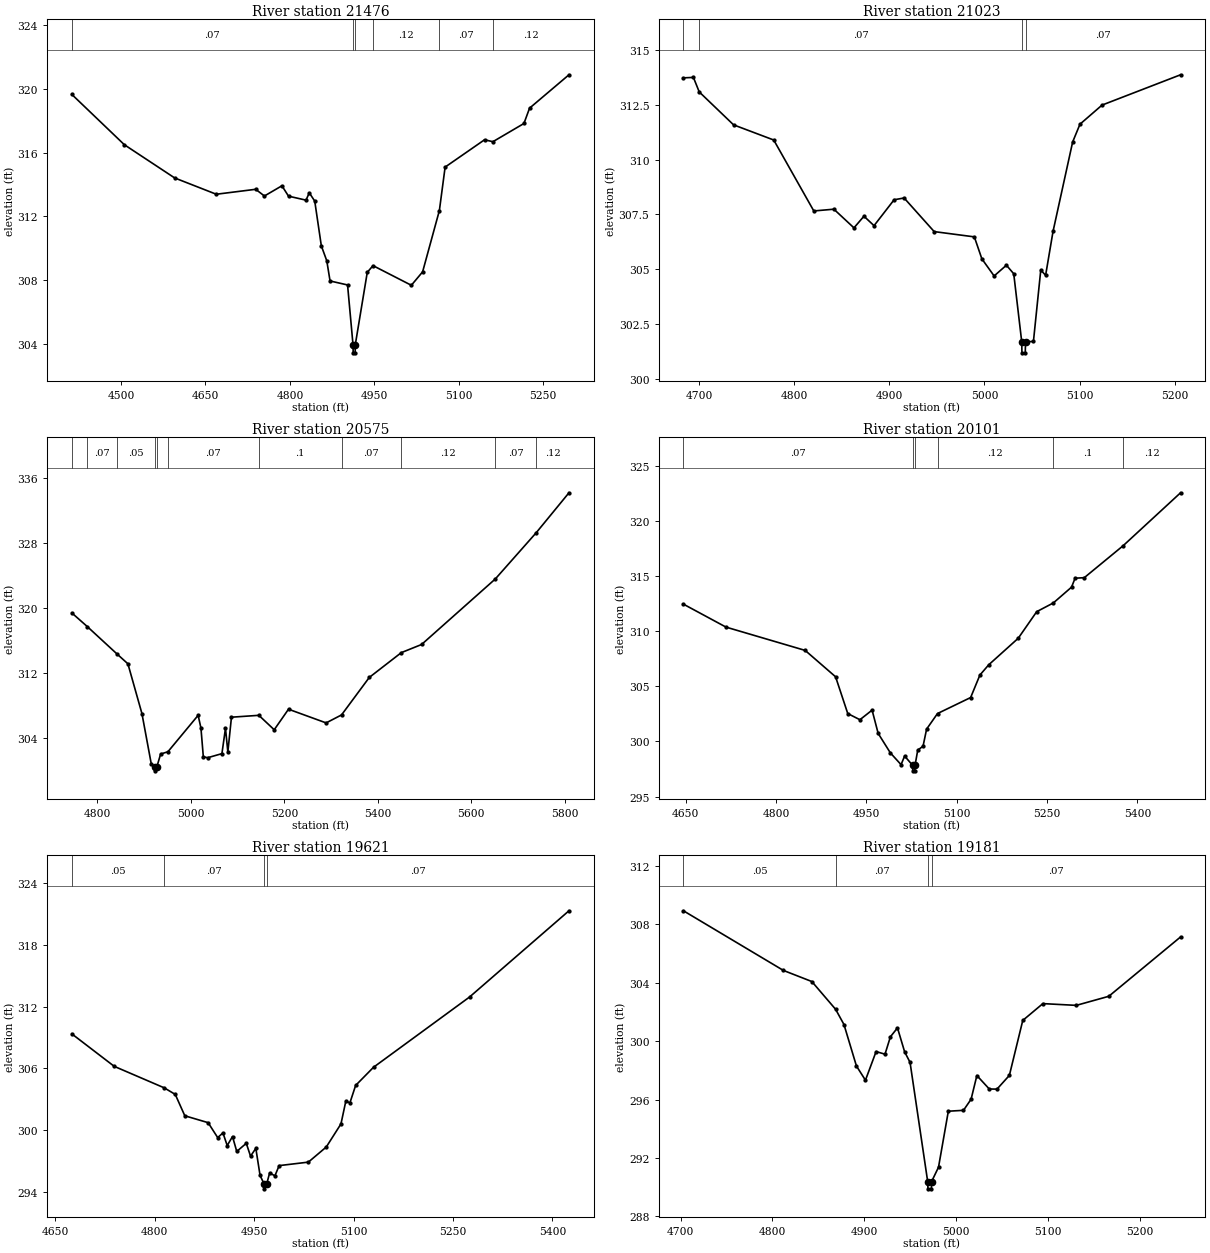
Type RM Length L Ch R = 1 ,21476   ,453,453,453
BEGIN DESCRIPTION:
ANDERSON CREEK 41.0
END DESCRIPTION:
XS GIS Cut Line= 3
      2455874.97     13576224.98        2456375.       13576525.
      2456674.97       13576525.
#Sta/Elev= 30
  4412.6  319.64  4505.9  316.49  4595.3  314.41  4669.2  313.39  4739.2   313.7
  4754.7  313.28  4785.8  313.92  4797.5  313.27  4828.6  313.02  4834.4  313.48
  4844.1  312.96  4855.8  310.16  4865.5  309.22  4871.3  307.96  4902.4  307.71
  4912.1  303.96  4912.4  303.46  4915.9  303.46  4916.1  303.96  4937.4   308.5
  4947.6  308.92  5015.7  307.69  5035.7  308.53  5065.5  312.37  5075.7  315.09
  5145.7   316.8  5160.6  316.68  5215.7  317.82  5225.7  318.78  5295.7  320.87
#Mann= 6 ,-1 , 0
  4412.6     .07       0  4912.1     .05       0  4916.1     .07       0
  4947.6     .12       0  5065.5     .07       0  5160.6     .12       0
Bank Sta=4912.1,4916.1
XS Rating Curve= 0 ,0
Exp/Cntr=0.3,0.1

Type RM Length L Ch R = 1 ,21023   ,448,448,448
BEGIN DESCRIPTION:
ANDERSON CREEK 40.0
END DESCRIPTION:
XS GIS Cut Line= 3
        2456025.       13577025.        2456325.       13576925.
      2456525.02       13576975.
#Sta/Elev= 30
  4683.7  313.72  4694.2  313.74  4700.3  313.08  4736.4  311.58  4778.6  310.89
  4820.7  307.66  4841.8  307.74  4862.9  306.89  4873.4  307.42    4884  306.99
  4905.1  308.17  4915.6  308.25  4947.2  306.72  4989.4  306.48  4997.3  305.48
  5010.2   304.7  5023.1  305.19  5030.8   304.8  5039.2   301.7  5039.4   301.2
  5042.9   301.2  5043.2   301.7  5051.5  301.72  5059.2  304.97  5064.3  304.73
  5072.1  306.73  5092.7   310.8  5100.4  311.61  5123.6  312.48  5206.1  313.86
#Mann= 4 ,-1 , 0
  4683.7     .05       0  4700.3     .07       0  5039.2     .05       0
  5043.2     .07       0
Bank Sta=5039.2,5043.2
XS Rating Curve= 0 ,0
Exp/Cntr=0.3,0.1

Type RM Length L Ch R = 1 ,20575   ,474,474,474
BEGIN DESCRIPTION:
ANDERSON CREEK 39.0
END DESCRIPTION:
XS GIS Cut Line= 3
        2456025.       13577325.        2456275.       13577325.
      2457074.96     13577175.01
#Sta/Elev= 30
  4745.2  319.39  4778.4  317.71    4842  314.35  4865.2  313.15  4895.2  307.05
  4915.2  300.87  4923.2  300.52  4923.4  300.02  4927.2  300.52  4935.2  302.08
  4950.8  302.36  5015.5  306.83  5021.5  305.27  5026.6  301.74  5035.9  301.63
  5066.4  302.13    5074  305.24  5079.1  302.33  5086.8   306.6  5145.4  306.83
  5178.3  305.06  5208.9  307.58  5289.4   305.9  5322.4  306.88  5381.8  311.48
  5450.3  314.52  5493.7  315.52  5651.5  323.56  5739.3  329.25  5809.1  334.13
#Mann= 11 ,-1 , 0
  4745.2     .05       0  4778.4     .07       0    4842     .05       0
  4923.2     .05       0  4927.2     .05       0  4950.8     .07       0
  5145.4      .1       0  5322.4     .07       0  5450.3     .12       0
  5651.5     .07       0  5739.3     .12       0
Bank Sta=4923.2,4927.2
XS Rating Curve= 0 ,0
Exp/Cntr=0.3,0.1

Type RM Length L Ch R = 1 ,20101   ,480,480,480
BEGIN DESCRIPTION:
ANDERSON CREEK 38.0
END DESCRIPTION:
XS GIS Cut Line= 3
      2456224.96     13577725.01        2456575.       13577675.
      2456975.01     13577424.99
#Sta/Elev= 30
  4646.4  312.44  4717.1  310.36  4848.5  308.25    4899  305.86  4919.2  302.53
  4939.4  301.97  4959.6  302.84  4969.7  300.73  4989.9  298.97  5007.7   297.9
  5013.6  298.68  5026.9  297.84  5027.1  297.34  5030.6  297.34  5030.9  297.84
  5035.4  299.22  5044.2  299.57  5050.1  301.12  5068.2  302.53  5123.2  303.98
  5138.6  306.02  5153.3  306.95  5202.2  309.35  5232.9  311.76  5260.5  312.55
  5290.7  313.98  5296.6  314.79  5311.9  314.84  5376.5  317.74  5471.7  322.53
#Mann= 6 ,-1 , 0
  4646.4     .07       0  5026.9     .05       0  5030.9     .07       0
  5068.2     .12       0  5260.5      .1       0  5376.5     .12       0
Bank Sta=5026.9,5030.9
XS Rating Curve= 0 ,0
Exp/Cntr=0.3,0.1

Type RM Length L Ch R = 1 ,19621   ,440,440,440
BEGIN DESCRIPTION:
ANDERSON CREEK 37.0
END DESCRIPTION:
XS GIS Cut Line= 3
      2456525.01     13578274.99        2456775.       13578075.
      2457125.04     13577824.97
#Sta/Elev= 30
  4674.7  309.36  4738.7   306.2  4814.1  304.11  4830.8  303.47  4845.2  301.39
  4880.4  300.72  4894.8  299.27  4902.8  299.72  4909.2  298.49  4917.2  299.37
  4923.6  297.92    4938  298.71  4944.4  297.46  4952.4  298.22  4958.8  295.58
  4964.7  294.78    4965  294.28  4968.9  294.78  4973.2  295.82  4981.2  295.55
  4987.6  296.54  5031.7  296.88  5058.7  298.35  5080.9   300.6  5088.2  302.81
  5094.4  302.65    5103  304.34    5130  306.11    5275  312.95    5425  321.34
#Mann= 4 ,-1 , 0
  4674.7     .05       0  4814.1     .07       0  4964.7     .05       0
  4968.9     .07       0
Bank Sta=4964.7,4968.9
XS Rating Curve= 0 ,0
Exp/Cntr=0.3,0.1

Type RM Length L Ch R = 1 ,19181   ,467,467,467
BEGIN DESCRIPTION:
ANDERSON CREEK 36.0
END DESCRIPTION:
XS GIS Cut Line= 3
      2456724.99       13578575.        2456975.       13578425.
      2457125.03     13578224.96
#Sta/Elev= 30
    4703  308.91  4811.9  304.83  4842.9  304.07  4868.8  302.17  4877.9  301.13
  4891.5  298.29  4901.3  297.32  4912.9  299.28  4922.6   299.1  4928.5  300.29
  4936.2   300.9    4944  299.26  4949.9  298.54  4969.1  290.39  4969.4  289.89
  4973.1  289.89  4973.4  290.39  4980.9  291.37  4991.6   295.2  5008.1  295.26
  5016.4  296.02  5022.7  297.64  5036.2  296.72  5044.6  296.71  5058.1  297.65
  5072.7  301.41  5094.6  302.56    5131  302.44  5166.4  303.06  5244.6  307.12
#Mann= 4 ,-1 , 0
    4703     .05       0  4868.8     .07       0  4969.1     .05       0
  4973.4     .07       0
Bank Sta=4969.1,4973.4
XS Rating Curve= 0 ,0
Exp/Cntr=0.3,0.1

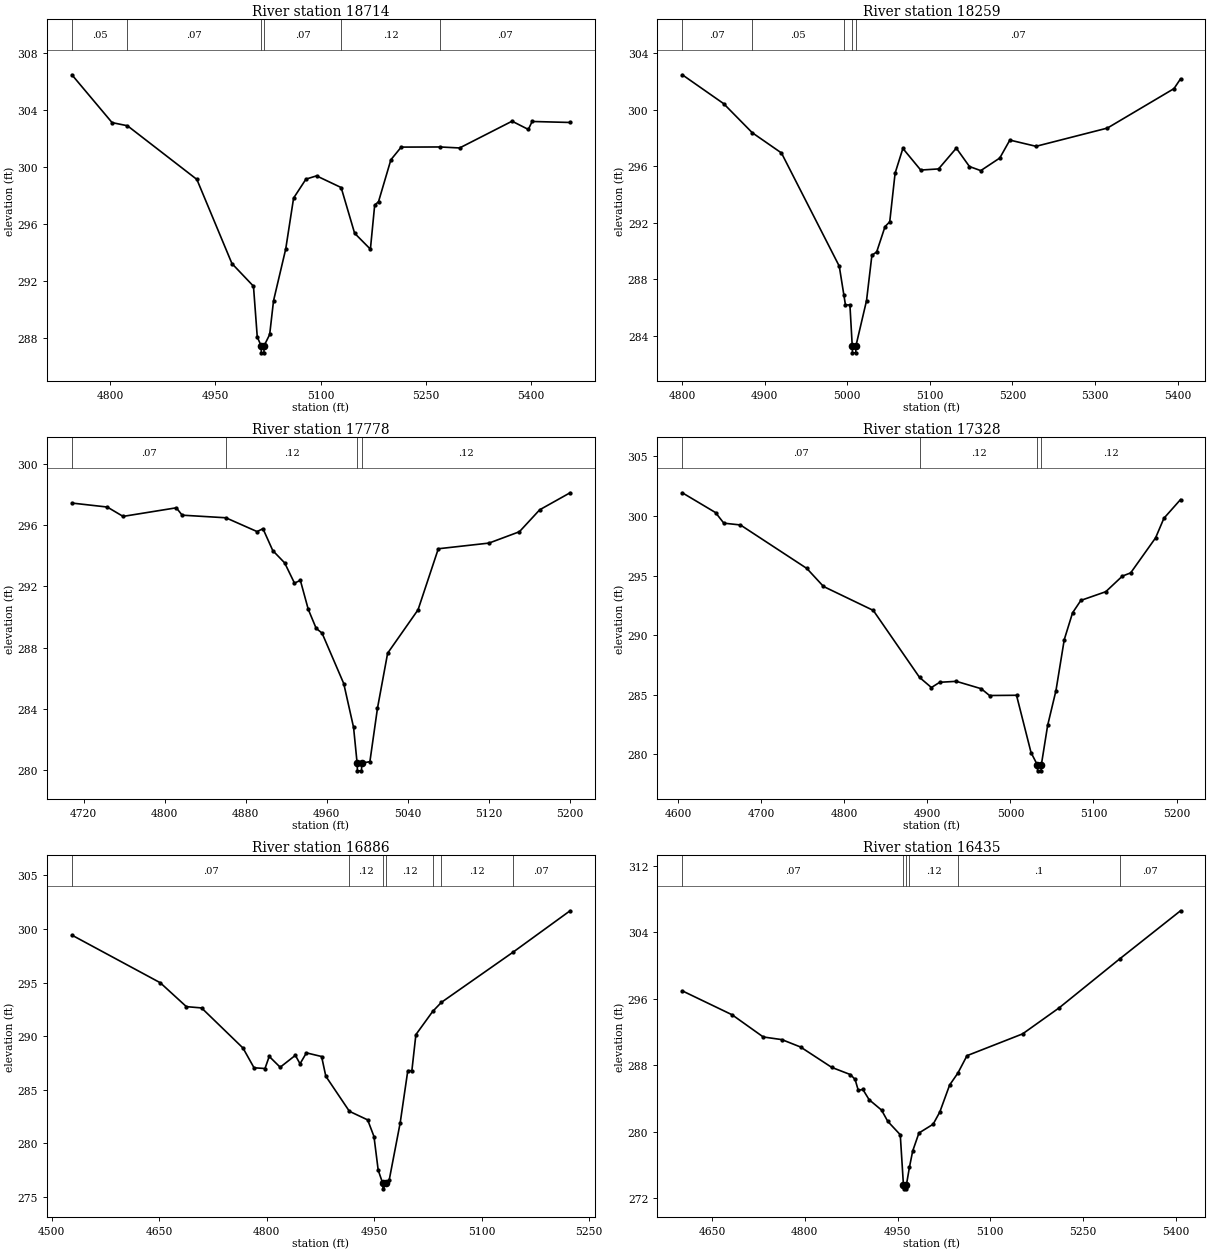
Type RM Length L Ch R = 1 ,18714   ,455,455,455
BEGIN DESCRIPTION:
ANDERSON CREEK 35.0
END DESCRIPTION:
XS GIS Cut Line= 3
      2457074.97     13578875.03        2457275.       13578725.
      2457694.48      13578535.6
#Sta/Elev= 30
  4745.3   306.5  4802.6  303.14  4824.5  302.92  4923.5  299.15  4973.5  293.24
  5004.2  291.65  5009.6  288.08  5015.1  287.47  5015.4  286.97  5019.1  286.97
  5019.4  287.47  5027.3  288.26  5032.8  290.63  5050.2  294.27  5061.4  297.84
    5079  299.17  5094.1   299.4  5129.2  298.58  5148.4  295.37  5170.9  294.25
    5177  297.34  5182.5  297.59  5200.1  300.53  5214.8  301.42  5270.1  301.43
  5298.1  301.36  5372.9  303.24  5396.1  302.66  5401.5  303.22  5455.6  303.15
#Mann= 6 ,-1 , 0
  4745.3     .05       0  4824.5     .07       0  5015.1     .05       0
  5019.4     .07       0  5129.2     .12       0  5270.1     .07       0
Bank Sta=5015.1,5019.4
XS Rating Curve= 0 ,0
Exp/Cntr=0.3,0.1

Type RM Length L Ch R = 1 ,18259   ,481,481,481
BEGIN DESCRIPTION:
ANDERSON CREEK 34.0
END DESCRIPTION:
XS GIS Cut Line= 3
      2457224.99       13579125.        2457425.       13579125.
      2457774.98     13578925.01
#Sta/Elev= 30
  4800.3  302.46  4850.3  300.42    4885  298.36  4920.3  296.93  4990.3  288.92
  4995.8  286.91  4997.8  286.18  5003.2  286.18    5006  283.29  5006.3  282.79
  5010.2  282.79  5010.5  283.29  5023.3  286.48  5029.8  289.69  5035.6  289.93
  5045.7  291.72  5051.4  292.06  5057.9   295.5  5067.3  297.25  5088.9  295.72
  5110.5   295.8    5132  297.27  5147.9  295.97  5161.6  295.68  5184.6  296.57
  5196.8  297.84  5228.5   297.4  5314.9  298.69  5395.5  301.48  5403.4  302.17
#Mann= 5 ,-1 , 0
  4800.3     .07       0    4885     .05       0  4995.8     .07       0
    5006     .05       0  5010.5     .07       0
Bank Sta=5006,5010.5
XS Rating Curve= 0 ,0
Exp/Cntr=0.3,0.1

Type RM Length L Ch R = 1 ,17778   ,450,450,450
BEGIN DESCRIPTION:
ANDERSON CREEK 33.0
END DESCRIPTION:
XS GIS Cut Line= 3
      2457275.04     13579425.02        2457525.       13579575.
        2457725.       13579575.
#Sta/Elev= 30
  4708.5  297.43  4743.4  297.17    4759  296.56  4811.5  297.12  4817.3  296.64
  4860.4  296.47  4891.2  295.57    4897  295.76  4906.7  294.33  4918.4  293.53
  4928.1  292.21  4933.9  292.39  4941.7   290.5  4949.5  289.26  4955.3  288.95
  4976.7  285.66  4986.4   282.8  4989.9  280.47  4990.2  279.97  4994.2  279.97
  4994.5  280.47  5002.5  280.57    5010  284.06    5020  287.64    5050  290.47
    5070  294.45    5120  294.82    5150  295.56    5170  296.99    5200   298.1
#Mann= 4 ,-1 , 0
  4708.5     .07       0  4860.4     .12       0  4989.9     .05       0
  4994.5     .12       0
Bank Sta=4989.9,4994.5
XS Rating Curve= 0 ,0
Exp/Cntr=0.3,0.1

Type RM Length L Ch R = 1 ,17328   ,442,442,442
BEGIN DESCRIPTION:
ANDERSON CREEK 32.0
END DESCRIPTION:
XS GIS Cut Line= 3
      2457075.02       13579975.        2457475.       13579975.
      2457675.02       13579975.
#Sta/Elev= 30
  4604.8  301.95  4644.8  300.29  4654.8   299.4  4674.8  299.25  4754.8   295.6
  4774.8  294.09  4834.8  292.08  4890.5  286.46  4904.8  285.61  4914.8  286.05
  4934.8  286.13  4964.8  285.51  4974.8  284.94  5007.3  284.96  5024.8  280.15
  5032.4  279.12  5032.7  278.62  5036.8  278.62  5037.2  279.12  5044.8  282.44
  5054.8  285.35  5064.8  289.63  5074.8  291.88  5084.8  292.92  5114.8  293.65
  5134.8  294.96  5144.8  295.23  5174.8  298.17  5184.8  299.81  5204.8  301.38
#Mann= 4 ,-1 , 0
  4604.8     .07       0  4890.5     .12       0  5032.4     .05       0
  5037.2     .12       0
Bank Sta=5032.4,5037.2
XS Rating Curve= 0 ,0
Exp/Cntr=0.3,0.1

Type RM Length L Ch R = 1 ,16886   ,451,451,451
BEGIN DESCRIPTION:
ANDERSON CREEK 31.0
END DESCRIPTION:
XS GIS Cut Line= 3
      2457174.98     13580525.01        2457575.       13580275.
      2457774.97     13580175.01
#Sta/Elev= 30
    4528  299.42  4651.3  294.98  4687.8  292.75    4709  292.63  4766.8  288.89
  4782.2  287.05  4797.5  286.98  4803.4  288.11  4818.7   287.1  4839.9  288.21
  4846.4  287.42  4855.3  288.44  4876.5   288.1  4882.4  286.26  4915.3  282.99
  4940.8  282.19  4949.6  280.64  4955.5   277.5  4961.9  276.26  4962.3  275.76
  4966.7  276.26  4970.8  276.56  4986.2  281.92  4996.8  286.78  5002.5  286.78
  5008.1  290.14  5031.5   292.3  5043.7  293.15  5143.1   297.8  5223.3  301.69
#Mann= 7 ,-1 , 0
    4528     .07       0  4915.3     .12       0  4961.9     .05       0
  4966.7     .12       0  5031.5      .1       0  5043.7     .12       0
  5143.1     .07       0
Bank Sta=4961.9,4966.7
XS Rating Curve= 0 ,0
Exp/Cntr=0.3,0.1

Type RM Length L Ch R = 1 ,16435   ,411,411,411
BEGIN DESCRIPTION:
ANDERSON CREEK 30.0
END DESCRIPTION:
XS GIS Cut Line= 3
      2457325.05     13580724.99        2457725.       13580675.
      2458075.02     13580474.99
#Sta/Elev= 30
  4601.7  296.93  4682.3  294.05  4732.7  291.38  4762.9  291.06  4793.1  290.17
  4843.5  287.72  4873.8  286.85  4881.3  286.27  4886.4  284.97  4893.9  285.06
    4904  283.83  4924.1  282.58  4934.2  281.22  4954.4  279.61  4959.5   273.6
  4959.9   273.1    4964   273.1  4964.4   273.6  4969.3  275.72  4974.5  277.65
  4984.6  279.82  5007.6  280.88  5018.4  282.35  5034.3   285.6  5047.6  287.03
  5062.4  289.13  5152.3  291.75  5211.4  294.88  5309.2  300.76  5407.9  306.57
#Mann= 6 ,-1 , 0
  4601.7     .07       0  4959.5     .05       0  4964.4     .07       0
  4969.3     .12       0  5047.6      .1       0  5309.2     .07       0
Bank Sta=4959.5,4964.4
XS Rating Curve= 0 ,0
Exp/Cntr=0.3,0.1

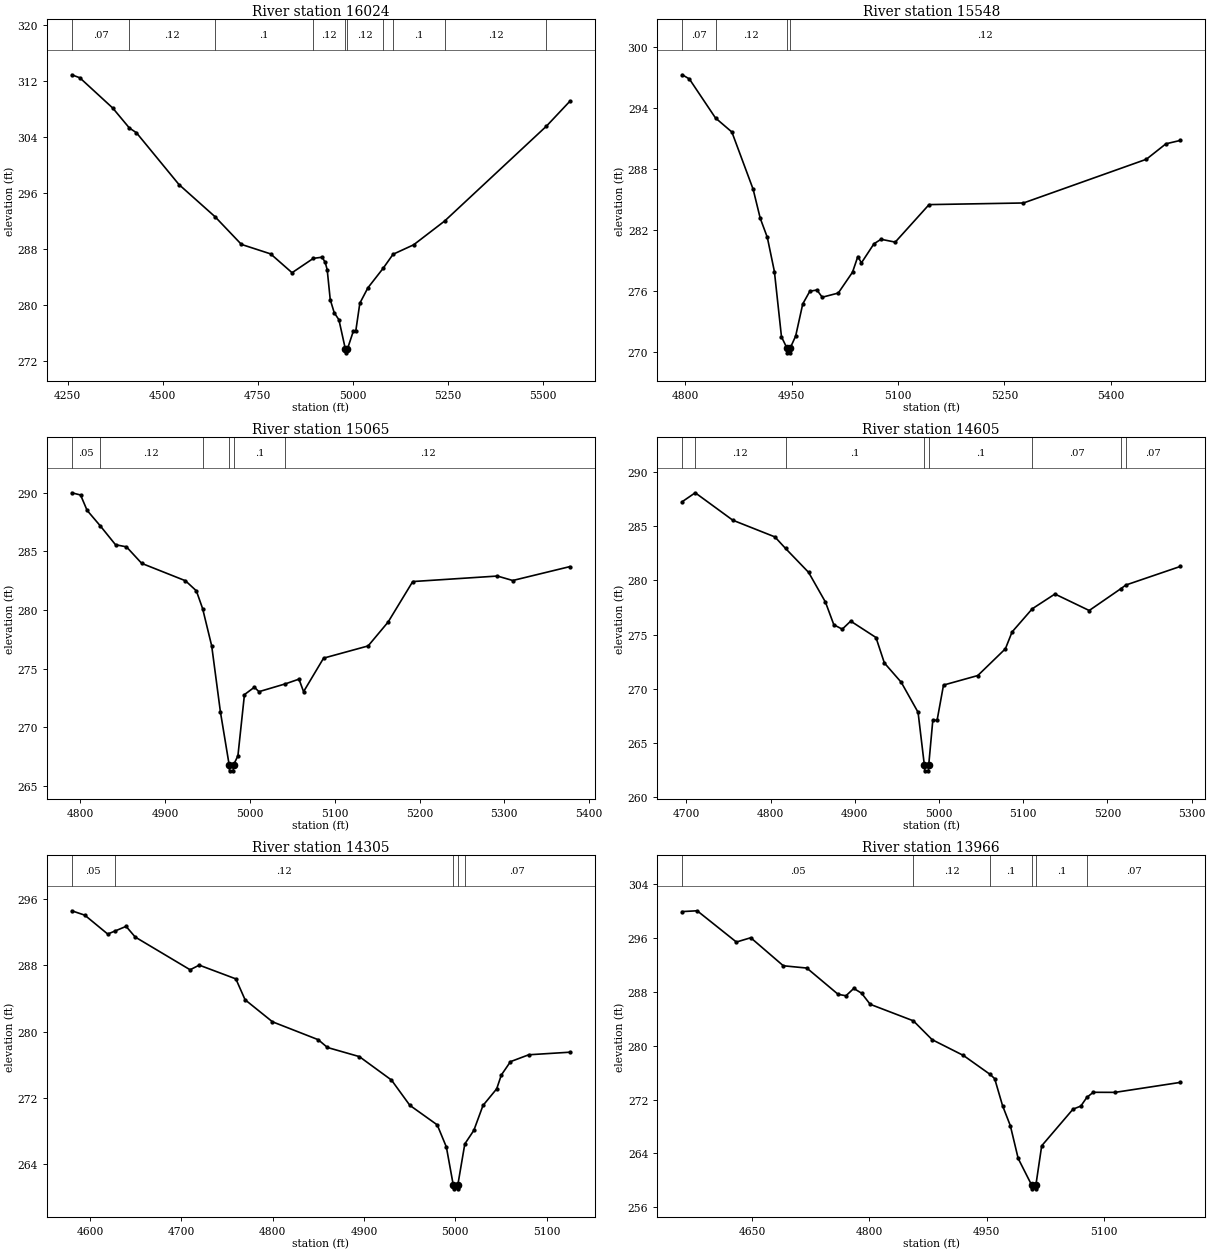
Type RM Length L Ch R = 1 ,16024   ,476,476,476
BEGIN DESCRIPTION:
ANDERSON CREEK 29.0
END DESCRIPTION:
XS GIS Cut Line= 3
      2457125.02     13581274.99        2457825.       13581025.
      2458225.03     13580624.97
#Sta/Elev= 30
  4260.8  312.93    4282   312.5  4368.6  308.17  4412.4  305.31  4430.7  304.65
  4542.7  297.23  4637.5  292.63  4706.8  288.67  4783.7  287.31    4840  284.62
  4895.9  286.67  4919.1  286.84  4927.1   286.1  4932.4  285.05  4940.4  280.76
    4951  278.88  4963.2  277.89  4980.3  273.66  4980.7  273.16  4985.3  273.66
  5001.4  276.31  5007.6  276.31  5018.2  280.26  5039.4  282.46  5079.3  285.24
  5105.6  287.26  5159.6  288.61  5241.1  292.01  5508.9  305.59  5569.8  309.11
#Mann= 10 ,-1 , 0
  4260.8     .07       0  4412.4     .12       0  4637.5      .1       0
  4895.9     .12       0  4980.3     .05       0  4985.3     .12       0
  5079.3     .07       0  5105.6      .1       0  5241.1     .12       0
  5508.9     .07       0
Bank Sta=4980.3,4985.3
XS Rating Curve= 0 ,0
Exp/Cntr=0.3,0.1

Type RM Length L Ch R = 1 ,15548   ,483,483,483
BEGIN DESCRIPTION:
ANDERSON CREEK 28.0
END DESCRIPTION:
XS GIS Cut Line= 3
      2457424.99       13581425.        2457625.       13581425.
        2458125.       13581375.
#Sta/Elev= 30
  4795.5  297.25  4805.5  296.84  4842.4     293  4865.5  291.62  4895.5  285.99
  4905.5  283.14  4915.5  281.26  4925.5   277.9  4935.5  271.47    4943   270.4
  4943.4   269.9  4947.6   269.9    4948   270.4  4955.5  271.55  4965.5  274.71
  4975.5  275.96  4985.5  276.08    4993  275.37  5015.6  275.78  5035.7  277.83
  5043.2  279.37  5048.3  278.75  5065.9  280.62  5075.9  281.07    5096  280.79
  5143.7  284.48  5276.9  284.64  5450.3  288.94  5477.9  290.46    5498  290.79
#Mann= 4 ,-1 , 0
  4795.5     .07       0  4842.4     .12       0    4943     .05       0
    4948     .12       0
Bank Sta=4943,4948
XS Rating Curve= 0 ,0
Exp/Cntr=0.3,0.1

Type RM Length L Ch R = 1 ,15065   ,460,460,460
BEGIN DESCRIPTION:
ANDERSON CREEK 27.0
END DESCRIPTION:
XS GIS Cut Line= 3
      2457424.96     13581824.99        2457625.       13581875.
      2457975.01     13581724.99
#Sta/Elev= 30
    4790     290  4800.4  289.81  4808.1   288.5  4823.5  287.19  4841.6  285.57
  4854.5  285.39  4872.5  283.98    4924   282.5  4936.9  281.64  4944.3  280.12
    4955  276.94  4965.3   271.3  4975.6  266.79    4976  266.29  4980.3  266.29
  4980.7  266.79  4985.9  267.57  4993.6  272.79  5005.3  273.42  5010.7  273.04
    5042  273.71  5057.9  274.11  5063.3  273.04  5086.9   275.9  5139.4  276.94
    5163  278.98    5192  282.43  5291.8   282.9  5309.9  282.52    5377   283.7
#Mann= 6 ,-1 , 0
    4790     .05       0  4823.5     .12       0  4944.3      .1       0
  4975.6     .05       0  4980.7      .1       0    5042     .12       0
Bank Sta=4975.6,4980.7
XS Rating Curve= 0 ,0
Exp/Cntr=0.3,0.1

Type RM Length L Ch R = 1 ,14605   ,300,300,300
BEGIN DESCRIPTION:
ANDERSON CREEK 26.0
END DESCRIPTION:
XS GIS Cut Line= 3
      2457324.95       13582275.        2457625.       13582275.
      2457911.09     13582220.95
#Sta/Elev= 30
  4695.2  287.27  4710.6  288.09  4755.2  285.56  4805.2  284.02  4817.9  282.95
  4845.2  280.75  4865.2  278.01  4875.2  275.91  4885.2  275.51  4895.2  276.25
  4925.2  274.74  4935.2  272.39  4955.2  270.61  4975.2  267.84  4982.7  262.94
  4983.1  262.44  4987.4  262.44  4987.8  262.94  4992.7  267.11  4997.8  267.11
  5005.4  270.35  5046.1  271.23  5078.9   273.7  5086.8  275.25  5110.8  277.39
  5137.7  278.75  5178.4  277.23  5216.3  279.26  5221.9  279.58  5286.4  281.29
#Mann= 8 ,-1 , 0
  4695.2     .05       0  4710.6     .12       0  4817.9      .1       0
  4982.7     .05       0  4987.8      .1       0  5110.8     .07       0
  5216.3     .12       0  5221.9     .07       0
Bank Sta=4982.7,4987.8
XS Rating Curve= 0 ,0
Exp/Cntr=0.3,0.1

Type RM Length L Ch R = 1 ,14305   ,339,339,339
BEGIN DESCRIPTION:
X18048
END DESCRIPTION:
XS GIS Cut Line= 2
      2457255.67     13582529.06      2457799.66     13582565.32
#Sta/Elev= 30
    4580  294.59  4594.3  294.06  4619.4  291.78    4627  292.13  4639.5  292.71
  4649.5  291.42  4709.6  287.47  4719.6  288.03  4759.7  286.37  4769.8  283.85
  4799.8  281.19  4849.9  279.03    4860  278.09  4894.9  276.99  4930.1  274.16
  4950.2  271.11  4980.2  268.75  4990.2  266.08  4997.7  261.53  4998.1  261.03
  5002.4  261.03  5002.8  261.53  5010.4  266.45  5020.3  268.09  5030.3  271.09
  5045.3   273.1  5050.4  274.77  5060.4  276.38  5080.4  277.21  5125.2  277.52
#Mann= 5 ,-1 , 0
    4580     .05       0    4627     .12       0  4997.7     .05       0
  5002.8     .12       0  5010.4     .07       0
Bank Sta=4997.7,5002.8
XS Rating Curve= 0 ,0
Exp/Cntr=0.3,0.1

Type RM Length L Ch R = 1 ,13966   ,305,305,305
BEGIN DESCRIPTION:
X18049
END DESCRIPTION:
XS GIS Cut Line= 3
       2457135.9     13582833.73      2457661.87       13582870.
      2457738.01     13582790.23
#Sta/Elev= 30
  4560.3  299.96  4579.4  300.08  4629.6  295.43    4648  296.07  4689.7   291.9
  4719.8  291.56  4759.9  287.65  4769.9  287.44  4779.9  288.53  4789.9  287.82
  4800.9  286.17  4856.2  283.71  4880.2  280.91  4920.3  278.56  4954.6  275.73
  4960.3  275.11  4970.4  271.09  4980.4   268.1  4990.4  263.24  5007.9  259.22
  5008.3  258.72  5012.7  258.72    5013  259.22  5020.5  265.12  5060.6  270.57
  5070.6  271.03  5078.3  272.32  5086.5  273.08  5114.5  273.07  5197.8  274.55
#Mann= 6 ,-1 , 0
  4560.3     .05       0  4856.2     .12       0  4954.6      .1       0
  5007.9     .05       0    5013      .1       0  5078.3     .07       0
Bank Sta=5007.9,5013
XS Rating Curve= 0 ,0
Exp/Cntr=0.3,0.1

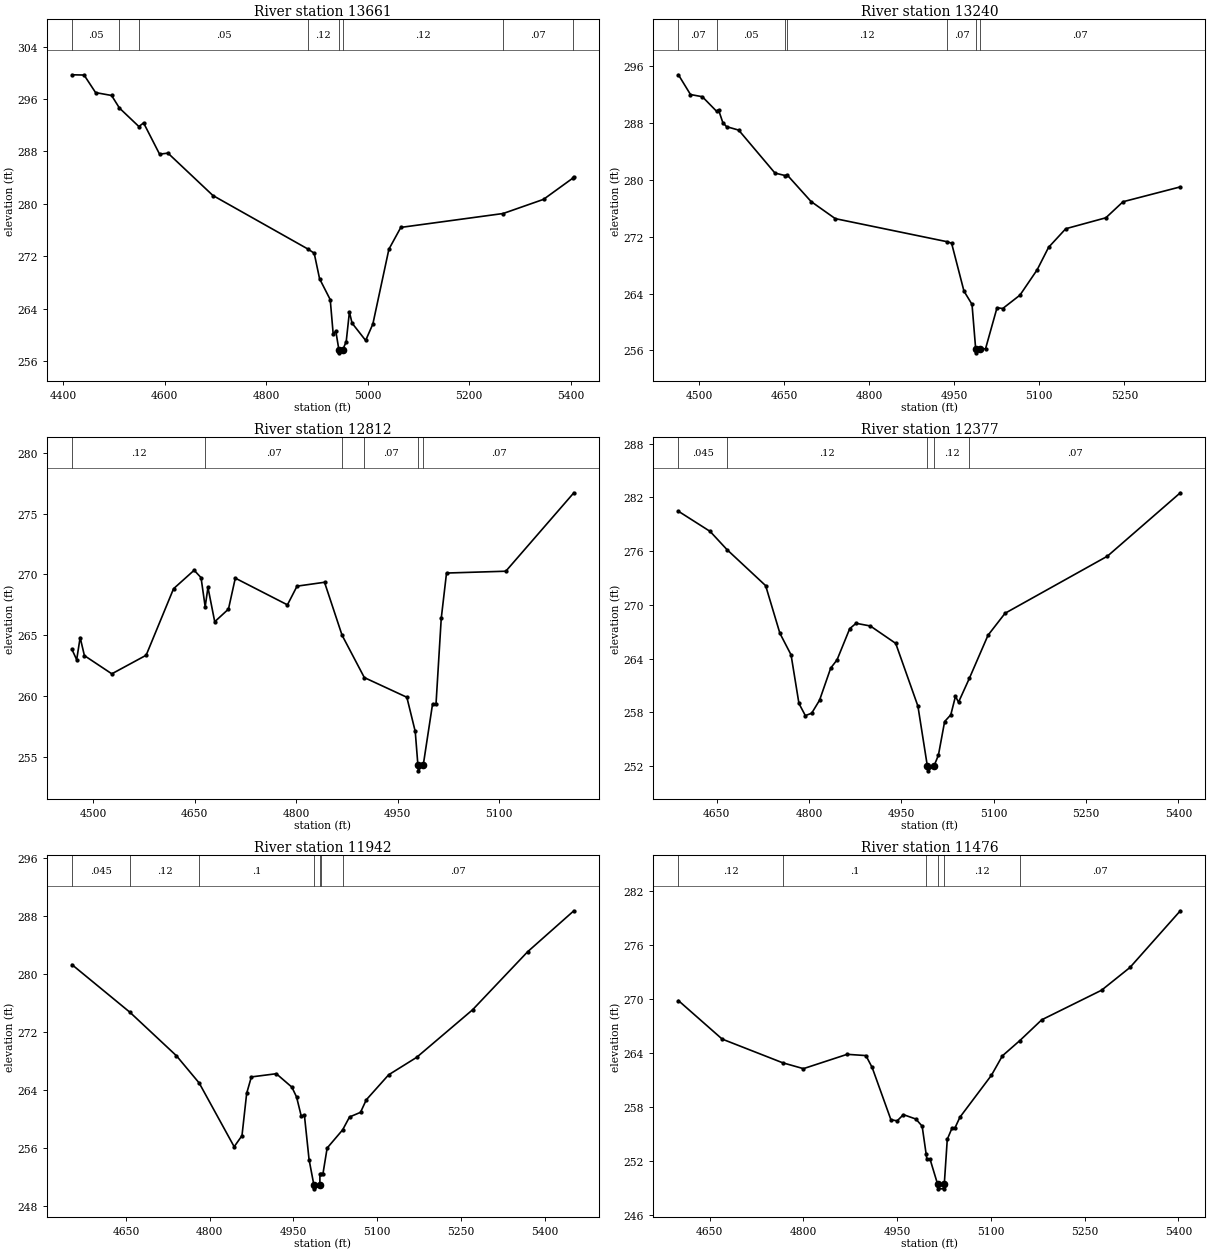
Type RM Length L Ch R = 1 ,13661   ,421,421,421
BEGIN DESCRIPTION:
X18050
END DESCRIPTION:
XS GIS Cut Line= 2
      2457070.68     13582971.58      2458011.88     13583275.66
#Sta/Elev= 30
  4417.2  299.71  4441.1  299.67  4463.8  296.99  4495.3  296.55  4510.8  294.63
  4549.1  291.81  4558.4  292.36  4589.9  287.59  4606.4  287.75    4695  281.28
  4882.4   273.1  4894.6  272.47  4905.2  268.57  4926.2  265.38    4932  260.15
  4937.2  260.57  4943.2  257.76  4943.7  257.26  4951.1  257.76  4957.7  258.99
    4964   263.5  4969.2   261.8    4996  259.15  5010.2  261.66  5041.8  273.08
  5065.3  276.41  5266.9  278.53  5346.5  280.69  5404.8  283.96  5406.3  284.14
#Mann= 8 ,-1 , 0
  4417.2     .05       0  4510.8     .07       0  4549.1     .05       0
  4882.4     .12       0  4943.2     .05       0  4951.1     .12       0
  5266.9     .07       0  5404.8     .12       0
Bank Sta=4943.2,4951.1
XS Rating Curve= 0 ,0
Exp/Cntr=0.3,0.1

Type RM Length L Ch R = 1 ,13240   ,428,428,428
BEGIN DESCRIPTION:
ANDERSON CREEK 25.0
END DESCRIPTION:
XS GIS Cut Line= 3
      2457075.02     13583175.01        2457475.       13583525.
      2457824.96     13583475.01
#Sta/Elev= 30
  4463.6   294.8  4484.9  292.02  4505.8  291.71  4530.8  289.67  4534.3  289.87
  4541.9  288.07  4548.5   287.5  4569.9  287.01  4633.9  280.96  4651.7  280.62
  4655.8  280.66  4697.5  276.96  4740.2  274.55  4937.5   271.3  4945.3  271.09
  4967.1  264.35  4981.3  262.48  4987.8  256.16  4988.3  255.66  4995.8  256.16
  5005.2  256.25  5025.4  262.01  5035.5   261.9  5065.8  263.78  5096.1  267.34
  5116.3  270.51  5146.6  273.13  5217.3  274.67  5247.6  276.93  5348.6  279.02
#Mann= 7 ,-1 , 0
  4463.6     .07       0  4530.8     .05       0  4651.7     .07       0
  4655.8     .12       0  4937.5     .07       0  4987.8     .05       0
  4995.8     .07       0
Bank Sta=4987.8,4995.8
XS Rating Curve= 0 ,0
Exp/Cntr=0.3,0.1

Type RM Length L Ch R = 1 ,12812   ,435,435,435
BEGIN DESCRIPTION:
ANDERSON CREEK 24.0
END DESCRIPTION:
XS GIS Cut Line= 3
      2457146.85     13583961.77        2457675.       13583875.
      2457875.01       13583825.
#Sta/Elev= 30
  4468.7  263.82  4475.7  262.97  4480.8   264.8  4487.1  263.31  4527.6  261.81
  4578.3  263.34  4618.8  268.82  4649.2  270.34  4659.4  269.73  4665.5  267.33
  4669.6  268.93  4679.6   266.1  4699.9  267.14    4710  269.69    4787  267.49
  4801.2  269.03  4841.8  269.35  4867.7  264.99  4900.6   261.5  4963.4  259.88
  4975.8  257.06  4979.7  254.32  4980.2  253.82  4987.7  254.32  5001.4  259.33
  5006.5  259.33  5014.2  266.37    5022  270.11  5109.6  270.26  5210.1  276.72
#Mann= 6 ,-1 , 0
  4468.7     .12       0  4665.5     .07       0  4867.7     .12       0
  4900.6     .07       0  4979.7     .05       0  4987.7     .07       0
Bank Sta=4979.7,4987.7
XS Rating Curve= 0 ,0
Exp/Cntr=0.3,0.1

Type RM Length L Ch R = 1 ,12377   ,435,435,435
BEGIN DESCRIPTION:
ANDERSON CREEK 23.0
END DESCRIPTION:
XS GIS Cut Line= 3
        2457275.       13584375.        2457675.       13584275.
      2458074.98       13584325.
#Sta/Elev= 30
  4587.7  280.45  4639.2   278.2  4666.6  276.17  4729.4  272.15  4752.6  266.83
  4770.7  264.43  4783.5  259.01  4793.9  257.65  4804.2  257.92    4817  259.37
  4835.1  262.95  4845.4  263.87    4866  267.35  4876.3  267.95  4899.5  267.65
  4940.7  265.71  4976.8  258.71  4992.2  251.99  4992.7  251.49  5002.7  251.99
  5010.1  253.24  5020.2  256.99  5030.2  257.74  5037.8   259.8  5042.8  259.15
  5060.3   261.8  5090.7  266.62  5118.4  269.07  5284.7  275.44  5403.1  282.51
#Mann= 5 ,-1 , 0
  4587.7    .045       0  4666.6     .12       0  4992.2     .05       0
  5002.7     .12       0  5060.3     .07       0
Bank Sta=4992.2,5002.7
XS Rating Curve= 0 ,0
Exp/Cntr=0.3,0.1

Type RM Length L Ch R = 1 ,11942   ,466,466,466
BEGIN DESCRIPTION:
ANDERSON CREEK 22.0
END DESCRIPTION:
XS GIS Cut Line= 3
      2457274.98     13584474.99        2457675.       13584675.
      2458126.14     13584705.33
#Sta/Elev= 30
  4553.2   281.3  4656.9  274.75  4740.5  268.74  4781.2  264.99  4843.9  256.21
  4857.9  257.74  4866.3  263.57  4874.7  265.83  4919.4  266.27  4947.3  264.42
  4955.7  263.07  4964.1  260.43  4969.7  260.59  4978.1  254.45  4986.8  250.91
  4987.3  250.41  4997.4  250.91  4997.6  252.44  4999.6  252.44  5002.9  252.44
  5010.5  256.03  5038.3  258.54  5050.6  260.31  5070.3  260.95  5080.6  262.67
  5120.7  266.12  5170.8  268.52    5271  275.07  5369.7  283.07  5452.6  288.72
#Mann= 7 ,-1 , 0
  4553.2    .045       0  4656.9     .12       0  4781.2      .1       0
  4986.8     .05       0  4997.4      .1       0  4999.6     .12       0
  5038.3     .07       0
Bank Sta=4986.8,4997.4
XS Rating Curve= 0 ,0
Exp/Cntr=0.3,0.1

Type RM Length L Ch R = 1 ,11476   ,442,442,442
BEGIN DESCRIPTION:
ANDERSON CREEK 21.0
END DESCRIPTION:
XS GIS Cut Line= 3
      2457225.02       13585125.        2457625.       13585125.
      2458025.01       13585075.
#Sta/Elev= 30
  4600.1  269.82  4670.1  265.55    4767  262.92  4800.1  262.27  4870.1  263.86
  4900.1  263.72  4910.1   262.4  4940.1  256.61  4950.1  256.48  4960.1  257.17
  4980.1  256.68  4990.1  255.89  4996.4  252.84  4997.6  252.26  5002.6  252.26
  5014.9  249.44  5015.4  248.94    5025  248.94  5025.5  249.44  5030.3  254.43
  5037.9  255.68  5042.9  255.74  5050.5  256.88  5100.9  261.53  5118.5  263.69
  5146.5  265.39  5181.5  267.69  5277.2  270.97  5322.6  273.49  5403.2  279.78
#Mann= 6 ,-1 , 0
  4600.1     .12       0    4767      .1       0  4996.4     .12       0
  5014.9     .05       0  5025.5     .12       0  5146.5     .07       0
Bank Sta=5014.9,5025.5
XS Rating Curve= 0 ,0
Exp/Cntr=0.3,0.1