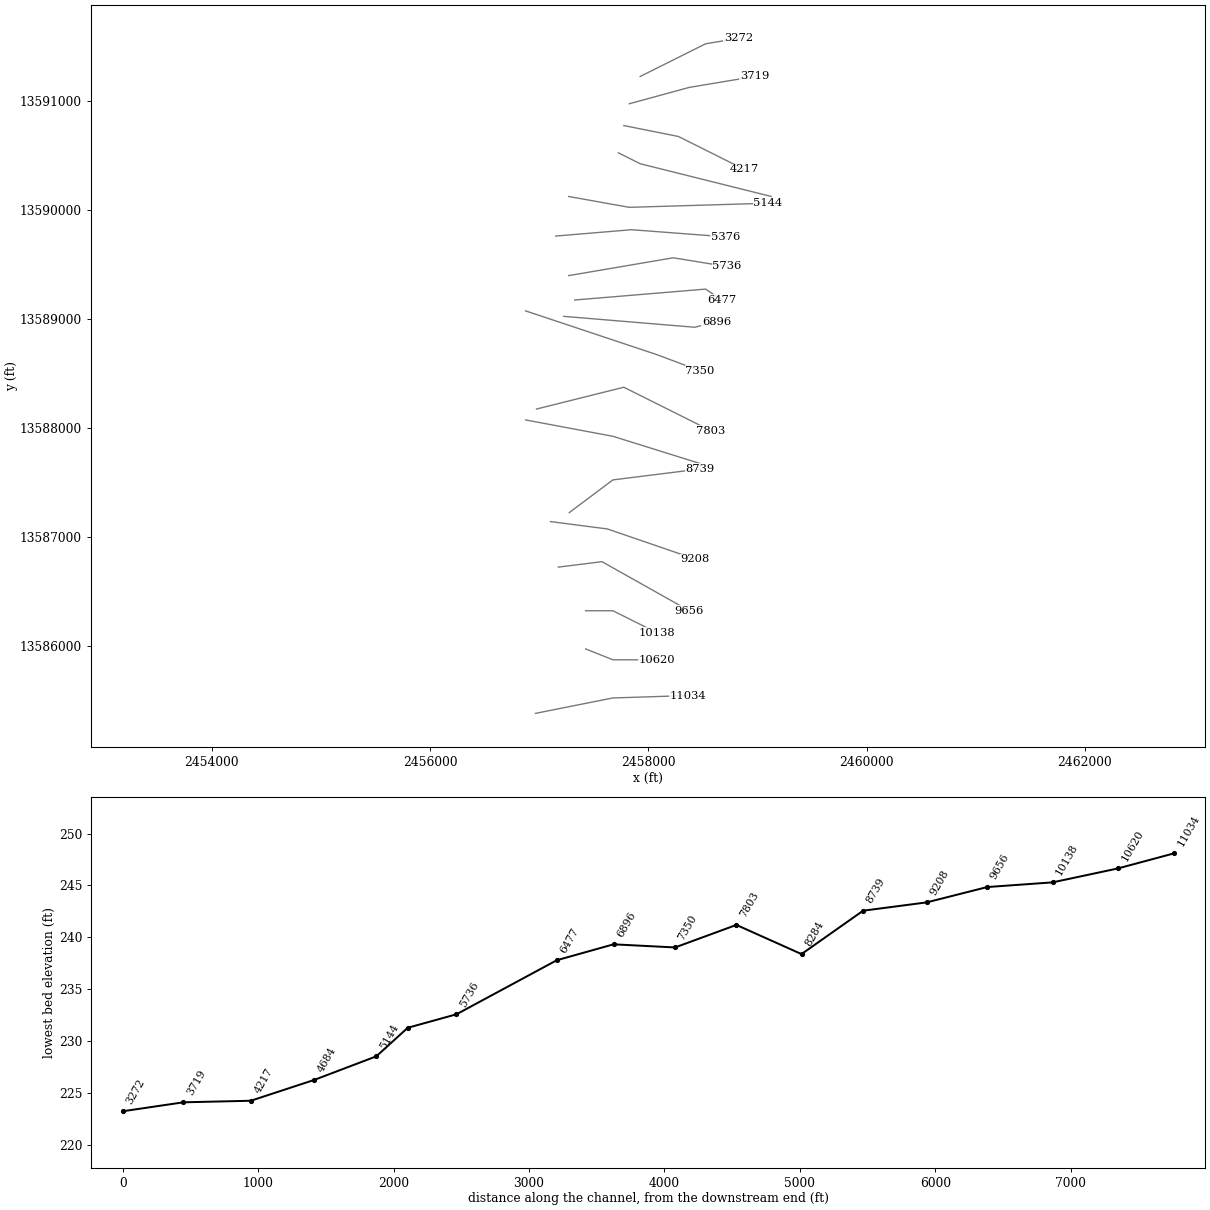
HEC-RAS study ANDERSON CREEK.prj: ANDERSON CREEK Base Level Engineering

--- ANDERSON CREEK.g01 (geometry) --- (continued)

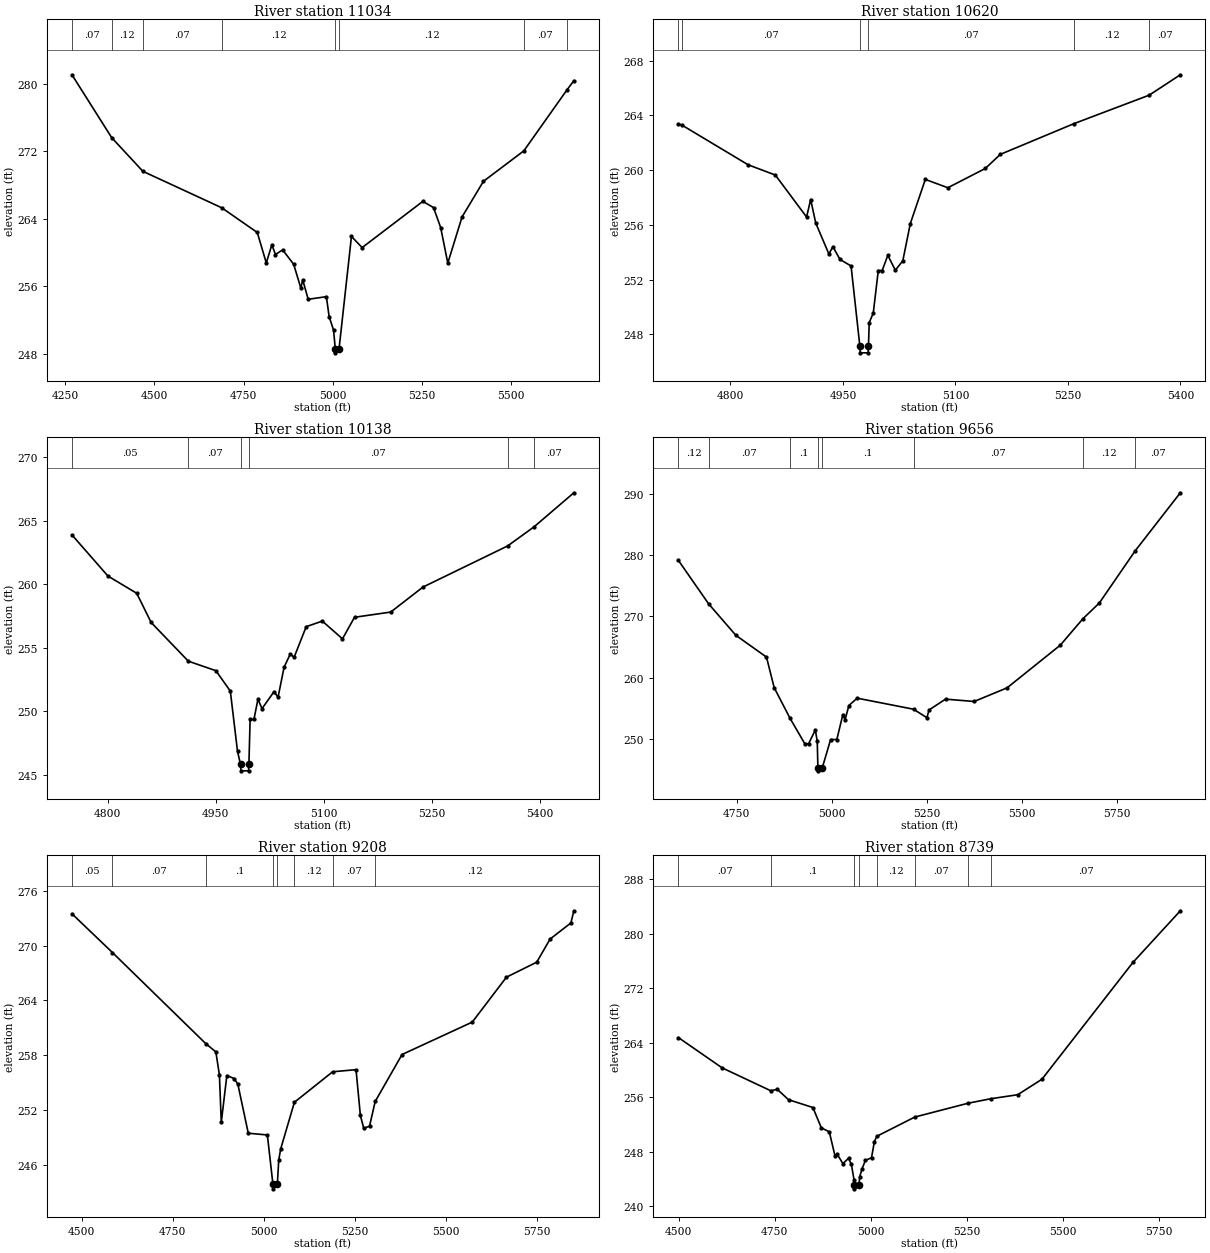
Type RM Length L Ch R = 1 ,11034   ,414,414,414
BEGIN DESCRIPTION:
ANDERSON CREEK 20.0
END DESCRIPTION:
XS GIS Cut Line= 3
      2456965.43      13585383.6        2457675.       13585525.
      2458358.23     13585546.83
#Sta/Elev= 30
  4268.6  281.06  4380.1   273.6  4467.6  269.61  4688.6  265.29  4788.2  262.36
  4813.4  258.75    4829   260.9  4839.2  259.75  4859.3   260.3  4890.2  258.59
  4910.4  255.75  4915.5  256.76  4930.9  254.44  4981.9  254.75  4989.6  252.39
  5002.1  250.77  5006.8  248.59  5007.3  248.09  5017.5  248.59  5052.2  261.89
  5082.2  260.57  5252.3  266.05  5282.3  265.31  5302.3  262.95  5322.3  258.73
  5362.3  264.21  5422.3  268.43  5535.5  272.04  5655.4  279.21  5675.7  280.36
#Mann= 8 ,-1 , 0
  4268.6     .07       0  4380.1     .12       0  4467.6     .07       0
  4688.6     .12       0  5006.8     .05       0  5017.5     .12       0
  5535.5     .07       0  5655.4     .12       0
Bank Sta=5006.8,5017.5
XS Rating Curve= 0 ,0
Exp/Cntr=0.3,0.1

Type RM Length L Ch R = 1 ,10620   ,482,482,482
BEGIN DESCRIPTION:
ANDERSON CREEK 19.0
END DESCRIPTION:
XS GIS Cut Line= 3
      2457425.03     13585974.99        2457675.       13585875.
      2458074.97       13585875.
#Sta/Elev= 30
  4730.7  263.38  4735.7  263.28  4823.6  260.39  4859.9  259.64  4901.6  256.57
    4907  257.85  4913.8  256.13  4931.3  253.87  4936.7   254.4  4946.1  253.47
  4960.9  252.99  4972.6  247.14  4973.1  246.64  4983.6  246.64  4984.1  247.14
  4985.1  248.85  4990.5  249.55  4997.2  252.66  5002.4  252.66  5009.9  253.77
  5019.9  252.68  5029.9  253.37  5039.9  256.09  5059.9  259.32  5089.9  258.71
  5139.9  260.12  5159.9  261.15  5258.2   263.4  5358.4  265.48  5399.9  266.97
#Mann= 6 ,-1 , 0
  4730.7     .05       0  4735.7     .07       0  4972.6     .05       0
  4984.1     .07       0  5258.2     .12       0  5358.4     .07       0
Bank Sta=4972.6,4984.1
XS Rating Curve= 0 ,0
Exp/Cntr=0.3,0.1

Type RM Length L Ch R = 1 ,10138   ,482,482,482
BEGIN DESCRIPTION:
ANDERSON CREEK 18.0
END DESCRIPTION:
XS GIS Cut Line= 3
      2457425.02       13586325.        2457675.       13586325.
      2458075.01       13586125.
#Sta/Elev= 30
  4750.1  263.89  4800.1  260.65  4840.1  259.29  4860.1  256.99  4911.8  253.94
  4950.1  253.19  4970.1  251.58  4980.1  246.83  4984.3   245.8  4984.8   245.3
  4995.4   245.3  4995.9   245.8  4997.6  249.35  5002.9  249.35  5008.5  250.95
  5014.1   250.2  5030.8  251.54  5036.4   251.1  5044.8  253.47  5053.2  254.48
  5058.8  254.26  5075.5  256.66  5097.9   257.1  5125.9   255.7  5142.6   257.4
  5192.9  257.81  5237.7  259.78  5355.3  263.02  5392.1  264.53  5447.3  267.21
#Mann= 6 ,-1 , 0
  4750.1     .05       0  4911.8     .07       0  4984.3     .05       0
  4995.9     .07       0  5355.3     .12       0  5392.1     .07       0
Bank Sta=4984.3,4995.9
XS Rating Curve= 0 ,0
Exp/Cntr=0.3,0.1

Type RM Length L Ch R = 1 ,9656    ,448,448,448
BEGIN DESCRIPTION:
ANDERSON CREEK 17.0
END DESCRIPTION:
XS GIS Cut Line= 3
      2457174.97       13586725.        2457575.       13586775.
      2458374.98     13586325.01
#Sta/Elev= 30
  4596.8  279.13  4676.5  272.04    4748  266.93  4828.6  263.38  4848.8  258.41
  4890.5  253.42  4929.4  249.27  4939.5  249.27  4957.1   251.5  4962.2  249.68
  4963.9  245.35  4964.4  244.85  4975.5  245.35  4997.4  249.95  5013.7  249.95
  5029.6  254.01  5035.3  253.15  5045.5  255.49  5067.2  256.69  5215.6  254.89
  5250.8  253.51  5256.5  254.77  5299.8  256.53  5375.1  256.15  5461.8  258.37
    5602  265.33  5661.6  269.64  5704.6  272.19  5799.2  280.71  5917.8  290.15
#Mann= 8 ,-1 , 0
  4596.8     .12       0  4676.5     .07       0  4890.5      .1       0
  4963.9     .05       0  4975.5      .1       0  5215.6     .07       0
  5661.6     .12       0  5799.2     .07       0
Bank Sta=4963.9,4975.5
XS Rating Curve= 0 ,0
Exp/Cntr=0.3,0.1

Type RM Length L Ch R = 1 ,9208    ,469,469,469
BEGIN DESCRIPTION:
ANDERSON CREEK 16.0
END DESCRIPTION:
XS GIS Cut Line= 3
      2457103.32     13587142.76        2457625.       13587075.
      2458430.44     13586798.32
#Sta/Elev= 30
  4473.4  273.49  4584.5  269.25  4840.8  259.27  4868.4  258.37  4878.2  255.84
  4883.3  250.65  4898.6  255.78  4918.8  255.45  4928.9  254.81  4957.4  249.46
  5009.8  249.27  5025.1  243.87  5025.6  243.37  5037.2  243.87    5041  246.51
  5046.3  247.73    5084  252.85    5189  256.19  5253.2  256.42  5265.1  251.41
  5274.4     250  5290.2  250.23  5305.8  252.94  5379.5  258.08  5572.3  261.63
  5666.1  266.55  5749.2  268.19  5785.8  270.72    5843  272.49  5851.1  273.82
#Mann= 8 ,-1 , 0
  4473.4     .05       0  4584.5     .07       0  4840.8      .1       0
  5025.1     .05       0  5037.2      .1       0    5084     .12       0
    5189     .07       0  5305.8     .12       0
Bank Sta=5025.1,5037.2
XS Rating Curve= 0 ,0
Exp/Cntr=0.3,0.1

Type RM Length L Ch R = 1 ,8739    ,455,455,455
BEGIN DESCRIPTION:
ANDERSON CREEK 15.0
END DESCRIPTION:
XS GIS Cut Line= 3
      2457274.99     13587224.99        2457675.       13587525.
      2458474.96     13587624.99
#Sta/Elev= 30
  4499.6  264.78  4613.2  260.34    4740  256.97  4756.9  257.18  4786.1  255.66
  4849.6  254.51  4871.5  251.53  4892.3  250.94  4906.9  247.45  4913.2  247.62
  4927.7  246.27  4942.3  247.05  4949.6  246.18  4956.9  243.83  4957.1  243.07
  4957.6  242.57  4969.3  243.07  4971.5  244.38  4977.7  245.53  4986.1  246.74
  5002.1  247.14  5009.7  249.52    5016  250.29  5114.7  253.11  5253.4  255.14
  5312.3   255.8  5382.6  256.39  5445.6  258.66  5682.4  275.81  5805.8   283.4
#Mann= 8 ,-1 , 0
  4499.6     .07       0    4740      .1       0  4957.1     .05       0
  4969.3      .1       0    5016     .12       0  5114.7     .07       0
  5253.4      .1       0  5312.3     .07       0
Bank Sta=4957.1,4969.3
XS Rating Curve= 0 ,0
Exp/Cntr=0.3,0.1

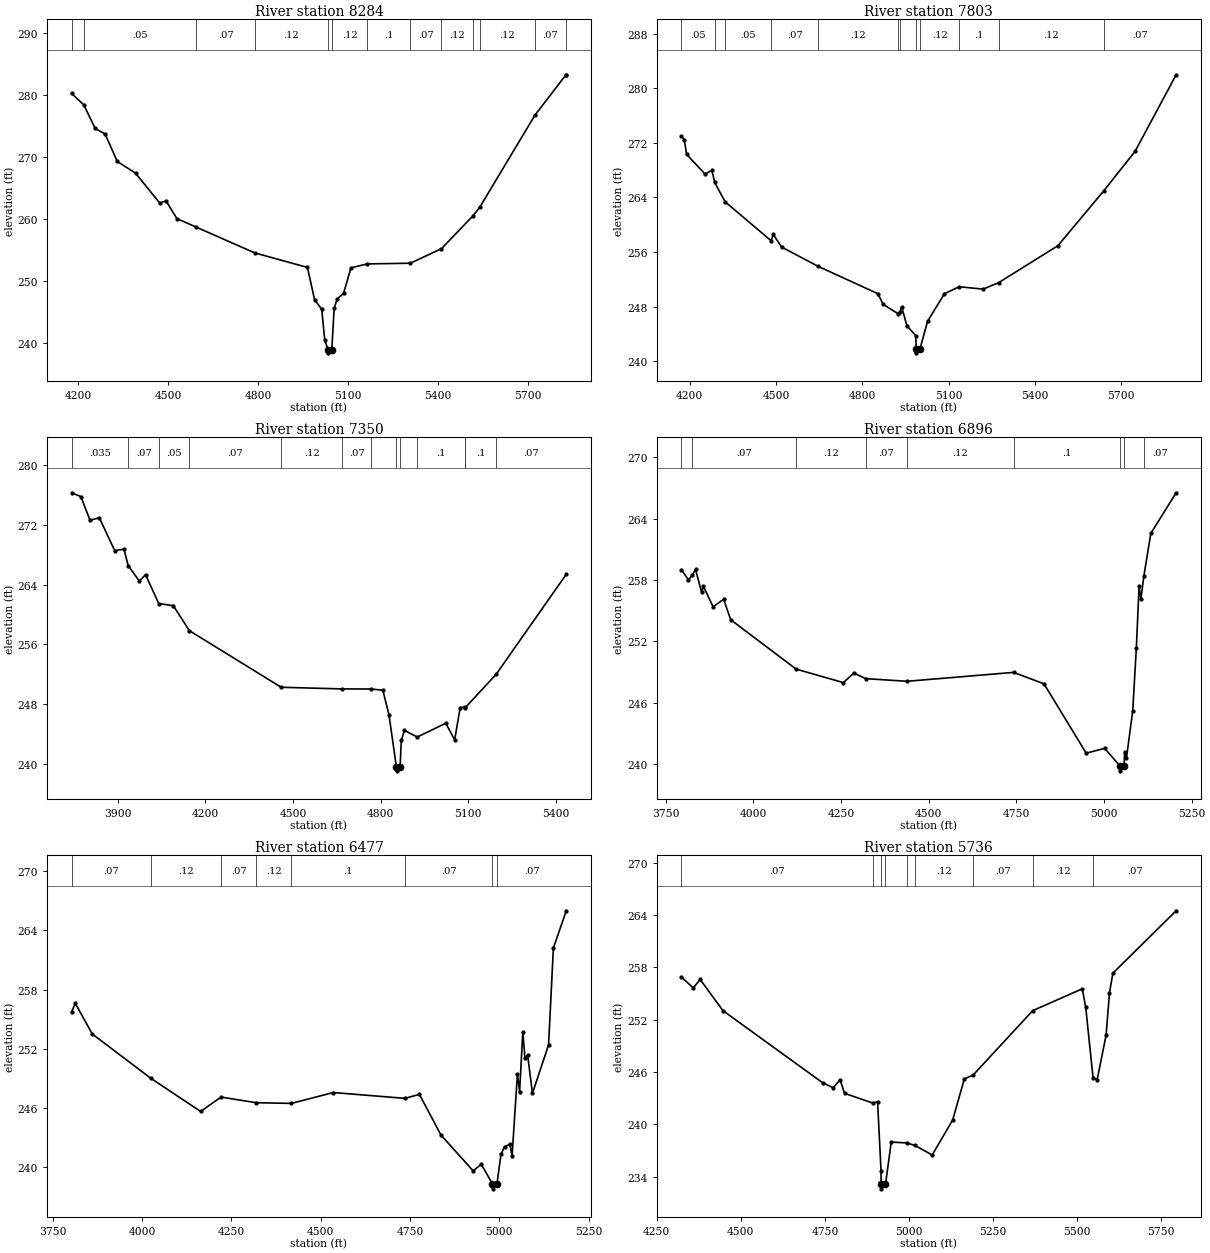
Type RM Length L Ch R = 1 ,8284    ,481,481,481
BEGIN DESCRIPTION:
ANDERSON CREEK 14.0
END DESCRIPTION:
XS GIS Cut Line= 3
      2456875.04     13588074.99        2457675.       13587925.
      2458474.95     13587675.01
#Sta/Elev= 30
  4177.5  280.25  4218.2   278.4  4256.3   274.6  4289.4   273.7  4330.1  269.27
  4391.1  267.38  4471.7  262.57  4492.9   262.9  4529.3  260.05  4593.9  258.67
    4789  254.52  4965.1  252.17  4988.9  246.96  5012.9  245.41  5022.8  240.47
  5033.9  238.89  5034.4  238.39  5046.4  238.89  5054.3   245.6  5064.7  247.12
  5085.7  247.97  5110.3   252.1  5164.6  252.74  5308.5  252.85  5412.5  255.19
  5516.5  260.43  5540.1  261.85  5724.4  276.71  5828.4  283.26  5829.5  283.26
#Mann= 13 ,-1 , 0
  4177.5    .035       0  4218.2     .05       0  4593.9     .07       0
    4789     .12       0  5033.9     .05       0  5046.4     .12       0
  5164.6      .1       0  5308.5     .07       0  5412.5     .12       0
  5516.5     .07       0  5540.1     .12       0  5724.4     .07       0
  5828.4     .12       0
Bank Sta=5033.9,5046.4
XS Rating Curve= 0 ,0
Exp/Cntr=0.3,0.1

Type RM Length L Ch R = 1 ,7803    ,453,453,453
BEGIN DESCRIPTION:
ANDERSON CREEK 13.0
END DESCRIPTION:
XS GIS Cut Line= 3
      2456974.99       13588175.        2457775.       13588375.
      2458575.04     13587974.98
#Sta/Elev= 30
  4171.2  273.01  4181.5  272.42  4189.2  270.33  4253.7  267.42  4276.9  268.01
  4286.8  266.21    4323  263.37  4482.6  257.66  4490.7  258.57  4519.1  256.73
    4647  253.88  4854.1  249.88  4872.1  248.32    4923  246.97    4931  247.26
  4936.6  247.96  4954.6  245.19  4985.5  243.71    4987   241.7  4987.5   241.2
  4999.6   241.7  5026.6  245.84  5085.3  249.88  5136.6   250.9  5219.4  250.55
  5273.9  251.51  5479.4  256.92  5639.5  265.01  5747.7  270.78  5890.3  282.01
#Mann= 12 ,-1 , 0
  4171.2     .05       0  4286.8    .035       0    4323     .05       0
  4482.6     .07       0    4647     .12       0    4923     .07       0
    4931     .12       0    4987     .05       0  4999.6     .12       0
  5136.6      .1       0  5273.9     .12       0  5639.5     .07       0
Bank Sta=4987,4999.6
XS Rating Curve= 0 ,0
Exp/Cntr=0.3,0.1

Type RM Length L Ch R = 1 ,7350    ,454,454,454
BEGIN DESCRIPTION:
ANDERSON CREEK 12.0
END DESCRIPTION:
XS GIS Cut Line= 3
      2456875.03     13589074.99        2458075.       13588675.
      2458475.02     13588524.99
#Sta/Elev= 30
  3742.9   276.3  3774.5  275.79  3806.1  272.61  3837.7  272.96  3890.4  268.54
  3922.1  268.74  3936.4  266.54  3974.8  264.45  3995.8  265.33  4041.1  261.45
  4090.7  261.17  4145.8  257.82  4459.8  250.23  4669.2  250.01  4766.2     250
  4807.5  249.84  4828.6  246.52  4853.9  239.53  4854.4  239.03  4866.5  239.53
  4870.7  243.11  4881.3  244.45  4925.1  243.56  5022.9  245.41  5053.2  243.18
  5071.9  247.47  5088.1   247.6  5089.1  247.49  5195.3  251.98    5435  265.38
#Mann= 13 ,-1 , 0
  3742.9    .035       0  3936.4     .07       0  4041.1     .05       0
  4145.8     .07       0  4459.8     .12       0  4669.2     .07       0
  4766.2     .12       0  4853.9     .05       0  4866.5     .12       0
  4925.1      .1       0  5088.1     .12       0  5089.1      .1       0
  5195.3     .07       0
Bank Sta=4853.9,4866.5
XS Rating Curve= 0 ,0
Exp/Cntr=0.3,0.1

Type RM Length L Ch R = 1 ,6896    ,419,419,419
BEGIN DESCRIPTION:
ANDERSON CREEK 11.0
END DESCRIPTION:
XS GIS Cut Line= 3
      2457224.99       13589025.        2458425.       13588925.
      2458624.97     13588974.99
#Sta/Elev= 30
  3795.3  259.02  3815.4     258  3825.5  258.44  3835.5  259.03    3853  256.78
    3858  257.37  3885.6  255.38  3915.7  256.11  3935.8  254.11  4122.3  249.28
  4256.9  247.96    4287   248.9  4320.2  248.35  4438.4  248.09  4742.2  248.96
  4828.9  247.84  4949.3  241.06    5002  241.53  5044.7  239.83  5045.2  239.33
  5057.3  239.83  5058.7  241.22  5063.9  240.56  5081.9  245.22  5092.2  251.36
    5100  257.41  5105.1  256.13  5113.7  258.41  5133.5  262.56  5205.6  266.53
#Mann= 9 ,-1 , 0
  3795.3     .05       0  3825.5     .07       0  4122.3     .12       0
  4320.2     .07       0  4438.4     .12       0  4742.2      .1       0
  5044.7     .05       0  5057.3      .1       0  5113.7     .07       0
Bank Sta=5044.7,5057.3
XS Rating Curve= 0 ,0
Exp/Cntr=0.3,0.1

Type RM Length L Ch R = 1 ,6477    ,741,741,741
BEGIN DESCRIPTION:
ANDERSON CREEK 10.0
END DESCRIPTION:
XS GIS Cut Line= 3
      2457324.96       13589175.        2458525.       13589275.
      2458675.02     13589174.99
#Sta/Elev= 30
    3803  255.69  3813.1  256.62  3860.7   253.5  4024.1  249.02  4164.3  245.64
  4221.1   247.1  4319.6  246.53    4418  246.46  4535.6  247.56  4735.6  246.97
  4776.4  247.37  4836.6  243.26  4926.9  239.62  4949.5   240.3  4980.8   238.3
  4981.3   237.8  4993.5   238.3  5004.7   241.3  5014.7  242.09  5029.7  242.31
  5035.7  241.13  5050.8  249.46  5056.8  247.65  5065.8   253.7  5071.8  251.03
  5079.3  251.34  5092.8  247.49  5137.9  252.39  5151.4  262.22  5187.5  265.98
#Mann= 8 ,-1 , 0
    3803     .07       0  4024.1     .12       0  4221.1     .07       0
  4319.6     .12       0    4418      .1       0  4735.6     .07       0
  4980.8     .05       0  4993.5     .07       0
Bank Sta=4980.8,4993.5
XS Rating Curve= 0 ,0
Exp/Cntr=0.3,0.1

Type RM Length L Ch R = 1 ,5736    ,360,360,360
BEGIN DESCRIPTION:
X18051
END DESCRIPTION:
XS GIS Cut Line= 3
      2457270.16     13589398.85       2458227.7     13589562.07
      2458720.54     13589482.34
#Sta/Elev= 30
  4323.3  256.89  4358.6  255.65  4378.9  256.62    4447  253.03  4742.9  244.77
  4774.6  244.18  4794.8  245.12  4808.2  243.55  4893.1  242.42  4906.4   242.6
  4916.6  234.68    4917  233.09  4917.5  232.59  4929.9  233.09    4947  237.96
  4992.4  237.86  5017.7  237.57  5068.7  236.47  5129.6  240.49  5164.2  245.19
    5191  245.67  5367.6  253.04  5514.8  255.54  5524.9  253.51    5547  245.32
  5559.2  245.13  5585.7  250.22  5595.8  255.09  5605.9  257.34  5793.9   264.5
#Mann= 9 ,-1 , 0
  4323.3     .07       0  4893.1     .12       0    4917     .05       0
  4929.9     .12       0  4992.4      .1       0  5017.7     .12       0
    5191     .07       0  5367.6     .12       0    5547     .07       0
Bank Sta=4917,4929.9
XS Rating Curve= 0 ,0
Exp/Cntr=0.3,0.1

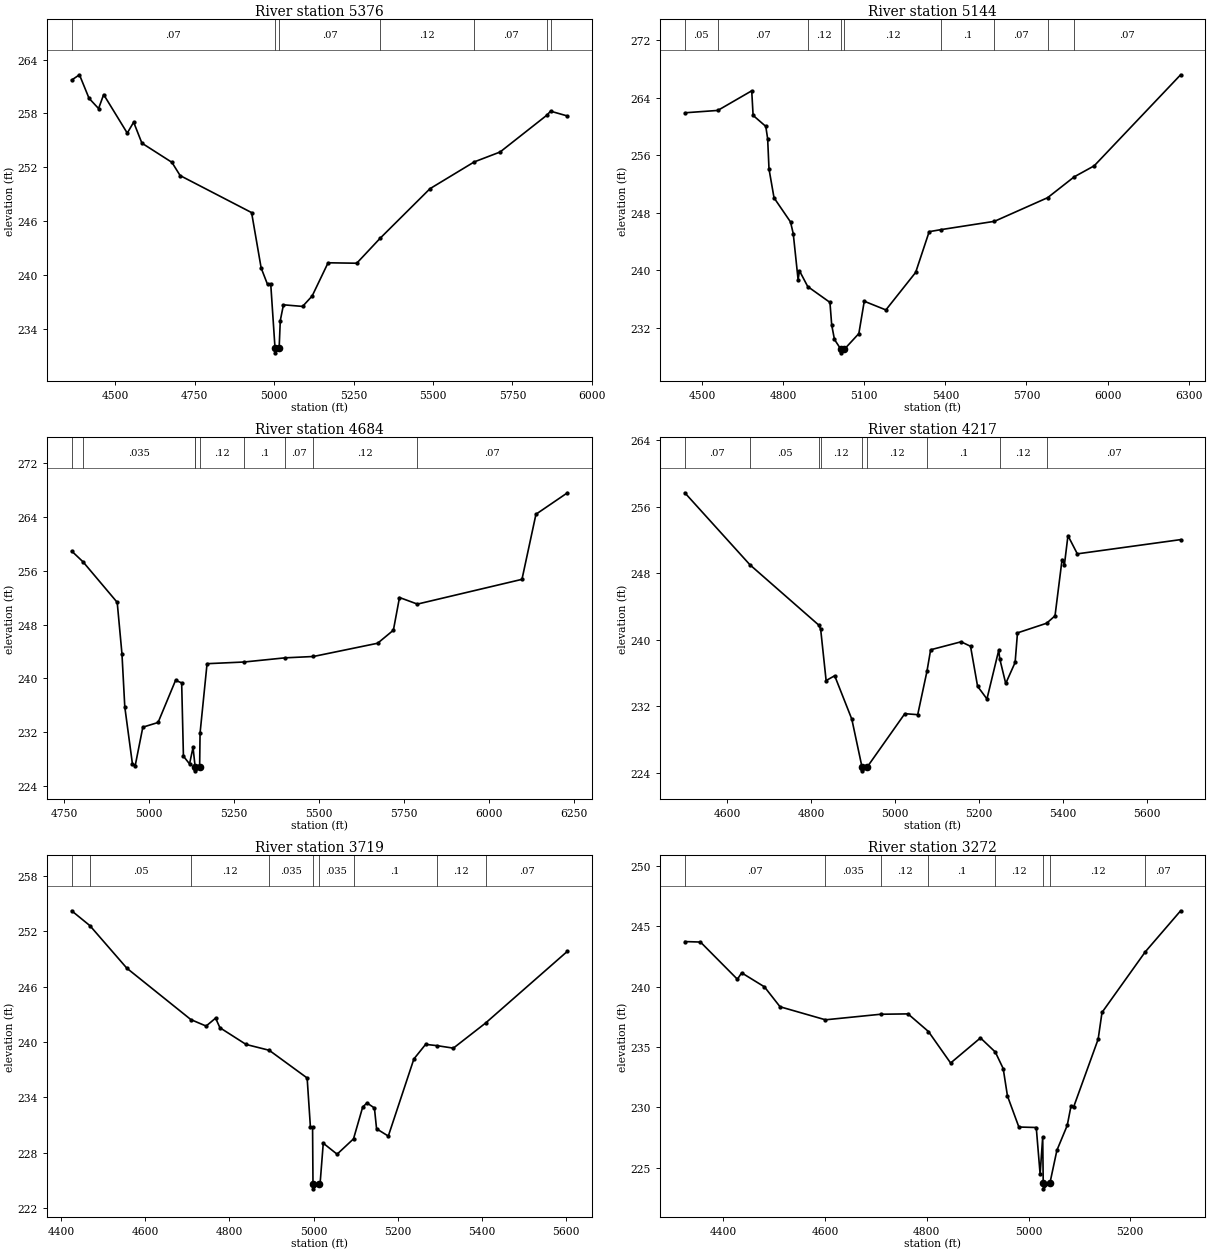
Type RM Length L Ch R = 1 ,5376    ,232,232,232
BEGIN DESCRIPTION:
X18052
END DESCRIPTION:
XS GIS Cut Line= 3
      2457150.46     13589761.56      2457846.85     13589819.59
      2458706.47     13589754.31
#Sta/Elev= 30
  4362.2  261.73  4386.8  262.32  4416.9   259.7    4447  258.55    4463  260.11
  4537.3  255.81  4557.4  257.03  4583.4  254.69  4677.8  252.55  4703.8  251.07
  4928.7  246.94  4958.8  240.76  4978.9  238.92  4988.9  239.01  5002.5  231.79
    5003  231.29  5015.4  231.79    5019  234.89    5029  236.65  5089.2  236.47
  5119.3  237.63  5169.5  241.34  5259.7  241.29  5333.2  244.07  5490.4  249.61
  5629.8   252.6  5710.9   253.7  5859.3  257.84  5869.7  258.26  5923.1  257.72
#Mann= 7 ,-1 , 0
  4362.2     .07       0  5002.5     .05       0  5015.4     .07       0
  5333.2     .12       0  5629.8     .07       0  5859.3     .12       0
  5869.7     .07       0
Bank Sta=5002.5,5015.4
XS Rating Curve= 0 ,0
Exp/Cntr=0.3,0.1

Type RM Length L Ch R = 1 ,5144    ,460,460,460
BEGIN DESCRIPTION:
ANDERSON CREEK 9.0
END DESCRIPTION:
XS GIS Cut Line= 3
      2457270.16     13590124.27        2457825.       13590025.
      2459094.59     13590062.61
#Sta/Elev= 30
  4436.4  261.94  4558.4  262.27  4683.9     265    4689  261.58  4735.9  260.05
  4742.8  258.33  4747.8  254.13  4766.4  250.11  4827.4  246.75  4837.5  245.12
  4855.4  238.73  4860.5  239.95  4891.1  237.76  4973.2  235.56  4979.7  232.42
  4989.9   230.4  5013.6  229.04  5014.1  228.54  5026.5  229.04  5080.1  231.22
  5100.1  235.72  5180.1  234.51  5290.2  239.73  5340.2   245.4  5385.1  245.69
  5581.7  246.84  5778.4  250.13  5876.7  253.03  5950.5  254.56  6270.2  267.23
#Mann= 9 ,-1 , 0
  4436.4     .05       0  4558.4     .07       0  4891.1     .12       0
  5013.6     .05       0  5026.5     .12       0  5385.1      .1       0
  5581.7     .07       0  5778.4     .12       0  5876.7     .07       0
Bank Sta=5013.6,5026.5
XS Rating Curve= 0 ,0
Exp/Cntr=0.3,0.1

Type RM Length L Ch R = 1 ,4684    ,467,467,467
BEGIN DESCRIPTION:
ANDERSON CREEK 8.0
END DESCRIPTION:
XS GIS Cut Line= 3
      2457724.97     13590525.02        2457925.       13590425.
      2459125.02     13590124.99
#Sta/Elev= 30
  4771.1  258.94  4804.7  257.33  4905.3  251.31  4919.3  243.67  4927.7  235.74
    4950  227.35  4958.4  227.05  4980.8  232.75  5025.7  233.45  5077.2  239.71
  5095.2  239.34  5100.4  228.44  5118.4  227.29  5128.7  229.74  5134.9  226.85
  5135.1  226.76  5135.6  226.26  5148.1  226.76  5149.4  231.87    5170  242.19
    5279  242.44  5399.7  243.06  5483.2  243.26  5672.5  245.23  5718.9  247.17
  5736.9  252.03  5789.6  251.05  6097.7  254.73  6138.9  264.41  6231.7   267.6
#Mann= 9 ,-1 , 0
  4771.1     .05       0  4804.7    .035       0  5134.9     .12       0
  5135.1    .035       0  5148.1     .12       0    5279      .1       0
  5399.7     .07       0  5483.2     .12       0  5789.6     .07       0
Bank Sta=5135.1,5148.1
XS Rating Curve= 0 ,0
Exp/Cntr=0.3,0.1

Type RM Length L Ch R = 1 ,4217    ,498,498,498
BEGIN DESCRIPTION:
ANDERSON CREEK 7.0
END DESCRIPTION:
XS GIS Cut Line= 3
      2457775.01       13590775.        2458275.       13590675.
      2458874.99       13590375.
#Sta/Elev= 30
  4499.4  257.68  4654.6  249.02  4818.8  241.76  4822.9  241.29  4835.9  235.11
  4856.3  235.69  4897.1  230.47  4921.2  224.76  4921.7  224.26  4934.3  224.76
  5023.3  231.13    5054  231.01    5076  236.21  5084.8  238.81  5157.4  239.77
  5179.8  239.23  5196.6  234.42  5218.9   232.9  5246.9  238.74  5249.4  237.73
  5263.6  234.76    5286  237.29  5291.6  240.84    5361     242    5381  242.89
  5397.8  249.66  5403.4  249.04  5411.8  252.53  5434.1  250.34  5680.1  252.05
#Mann= 9 ,-1 , 0
  4499.4     .07       0  4654.6     .05       0  4818.8    .035       0
  4822.9     .12       0  4921.2     .05       0  4934.3     .12       0
    5076      .1       0  5249.4     .12       0    5361     .07       0
Bank Sta=4921.2,4934.3
XS Rating Curve= 0 ,0
Exp/Cntr=0.3,0.1

Type RM Length L Ch R = 1 ,3719    ,447,447,447
BEGIN DESCRIPTION:
ANDERSON CREEK 6.0
END DESCRIPTION:
XS GIS Cut Line= 3
        2457825.       13590975.        2458375.       13591125.
      2458975.03     13591225.01
#Sta/Elev= 30
  4424.9  254.21  4468.3   252.6  4556.2  247.99  4708.3  242.43  4744.5  241.73
    4767  242.59  4777.3  241.55  4839.5  239.74  4894.4  239.11  4984.6  236.11
  4992.4  230.79  4997.5  230.79  4998.5  224.61    4999  224.11  5011.7  224.61
  5015.3  224.63  5022.9  229.05  5055.8  227.86  5094.8  229.52  5116.6  232.96
  5126.8  233.41  5144.5  232.86  5149.6  230.61  5177.5  229.82  5238.3  238.17
  5266.2  239.75  5293.3  239.61  5332.1  239.34  5408.5  242.05  5603.3  249.83
#Mann= 9 ,-1 , 0
  4424.9     .07       0  4468.3     .05       0  4708.3     .12       0
  4894.4    .035       0  4998.5    .035       0  5011.7    .035       0
  5094.8      .1       0  5293.3     .12       0  5408.5     .07       0
Bank Sta=4998.5,5011.7
XS Rating Curve= 0 ,0
Exp/Cntr=0.3,0.1

Type RM Length L Ch R = 1 ,3272    ,481,481,481
BEGIN DESCRIPTION:
ANDERSON CREEK 5.0
END DESCRIPTION:
XS GIS Cut Line= 3
      2457924.97     13591224.99        2458525.       13591525.
      2458825.01       13591575.
#Sta/Elev= 30
    4324  243.73  4354.8  243.69  4427.4  240.61  4435.8  241.14  4480.6  239.98
  4511.3  238.33  4600.6  237.25  4709.1  237.71  4762.9  237.74  4803.1  236.28
  4846.7  233.67  4905.4  235.75  4934.6  234.58  4950.1  233.21  4958.5  230.94
  4980.9  228.37  5015.1  228.33  5022.7  224.47  5027.8  227.55  5028.8  223.75
  5029.3  223.25  5042.1  223.75  5055.7  226.44    5076   228.5  5083.6  230.14
  5088.6  230.03  5136.8  235.64  5144.4  237.86  5229.5  242.88    5299  246.28
#Mann= 8 ,-1 , 0
    4324     .07       0  4600.6    .035       0  4709.1     .12       0
  4803.1      .1       0  4934.6     .12       0  5028.8     .05       0
  5042.1     .12       0  5229.5     .07       0
Bank Sta=5028.8,5042.1
XS Rating Curve= 0 ,0
Exp/Cntr=0.3,0.1