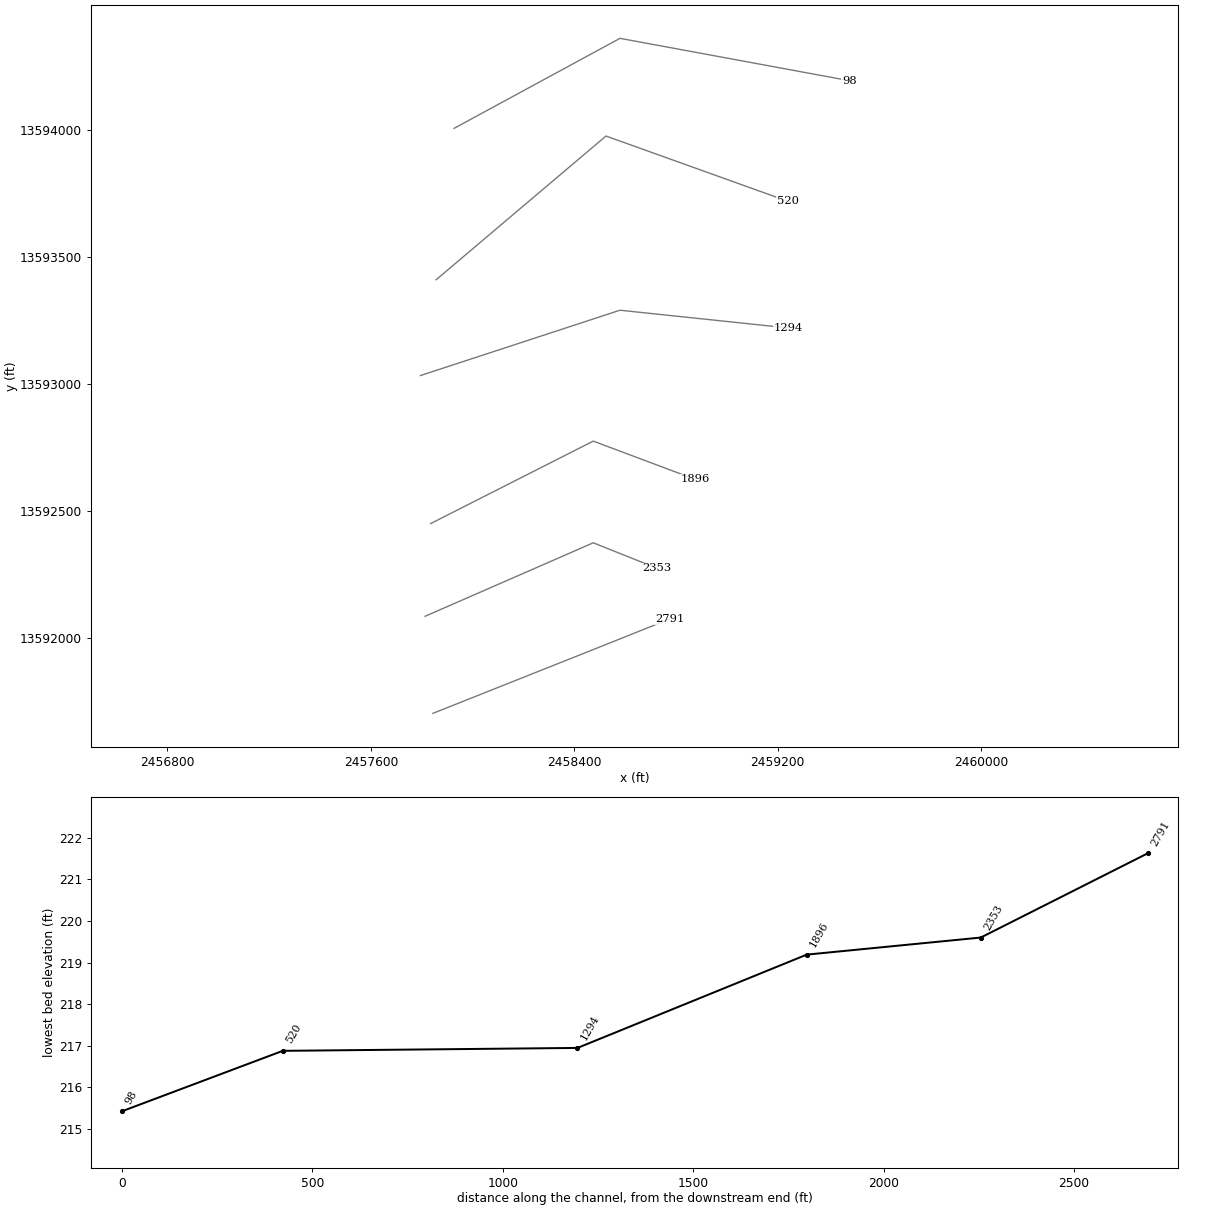
HEC-RAS study ANDERSON CREEK.prj: ANDERSON CREEK Base Level Engineering

--- ANDERSON CREEK.g01 (geometry) --- (continued)

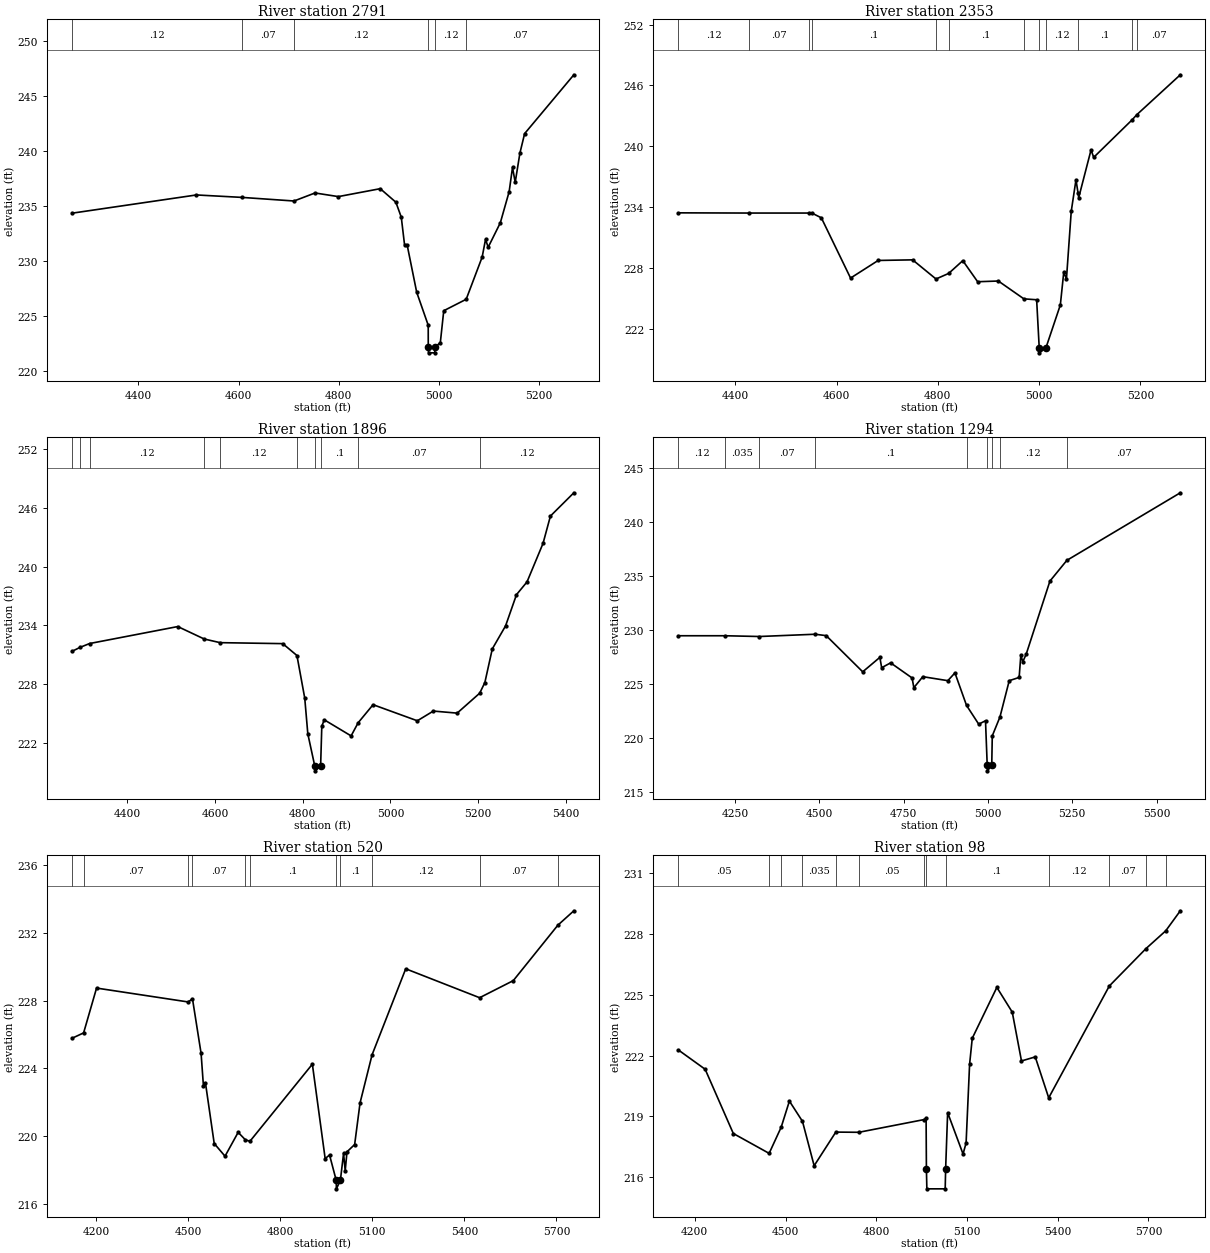
Type RM Length L Ch R = 1 ,2791    ,438,438,438
BEGIN DESCRIPTION:
ANDERSON CREEK 4.0
END DESCRIPTION:
XS GIS Cut Line= 3
      2457843.97     13591704.07        2458525.       13591975.
        2458775.       13592075.
#Sta/Elev= 30
  4267.4  234.32    4516  235.98  4606.1  235.76  4710.8  235.43  4752.8  236.16
  4799.3  235.83    4883  236.55  4914.2  235.32    4925  233.96  4931.5  231.46
  4936.9  231.39  4955.8  227.13  4978.8  224.13  4978.9  222.12  4979.4  221.62
  4991.7  221.62  4992.2  222.12    5003  222.56  5009.8  225.45  5054.6  226.49
  5086.5  230.33  5093.2  231.93  5098.6  231.23  5122.8  233.45  5140.4  236.28
  5147.1  238.48  5152.5  237.13  5161.9  239.79  5171.3  241.56  5269.6  246.91
#Mann= 6 ,-1 , 0
  4267.4     .12       0  4606.1     .07       0  4710.8     .12       0
  4978.9     .05       0  4992.2     .12       0  5054.6     .07       0
Bank Sta=4978.9,4992.2
XS Rating Curve= 0 ,0
Exp/Cntr=0.3,0.1

Type RM Length L Ch R = 1 ,2353    ,457,457,457
BEGIN DESCRIPTION:
ANDERSON CREEK 3.0
END DESCRIPTION:
XS GIS Cut Line= 3
      2457813.62     13592086.03        2458475.       13592375.
      2458724.99     13592275.01
#Sta/Elev= 30
  4287.8  233.42  4428.1   233.4  4545.8   233.4  4551.2   233.4    4570  232.93
  4627.7  226.98  4682.2  228.72  4750.2  228.78  4796.4  226.89  4821.4  227.44
  4849.3   228.7  4878.6  226.62  4919.5  226.69  4969.9  224.93  4995.1  224.84
  5000.2   220.1  5000.7   219.6  5013.5   220.1  5041.9  224.33  5048.6  227.54
    5054  226.91  5063.4  233.56  5072.8  236.69  5076.7  235.42  5078.2  234.93
  5102.5  239.63  5107.8   238.9  5183.8  242.61  5192.9  243.11  5278.8  247.05
#Mann= 12 ,-1 , 0
  4287.8     .12       0  4428.1     .07       0  4545.8     .12       0
  4551.2      .1       0  4796.4     .12       0  4821.4      .1       0
  4969.9     .12       0  5000.2     .05       0  5013.5     .12       0
  5076.7      .1       0  5183.8     .12       0  5192.9     .07       0
Bank Sta=5000.2,5013.5
XS Rating Curve= 0 ,0
Exp/Cntr=0.3,0.1

Type RM Length L Ch R = 1 ,1896    ,602,602,602
BEGIN DESCRIPTION:
ANDERSON CREEK 2.0
END DESCRIPTION:
XS GIS Cut Line= 3
      2457835.31     13592450.61        2458475.       13592775.
      2458874.96     13592625.01
#Sta/Elev= 30
  4273.9  231.36  4291.9  231.76  4314.1  232.16  4515.2  233.89  4575.6  232.62
  4611.7  232.25  4754.5  232.15  4786.9  230.94  4804.7   226.6  4811.7  222.96
  4827.5  219.69    4828  219.19  4840.9  219.69  4843.6  223.74  4849.2  224.39
  4910.4  222.75  4926.5  224.09  4960.5  225.93  5061.4  224.29  5097.9  225.28
  5152.2  225.07  5203.6   227.1  5215.4  228.19  5232.3  231.61  5262.6  233.96
  5287.5  237.14  5311.5  238.44    5348  242.36  5364.9  245.15  5418.3  247.52
#Mann= 10 ,-1 , 0
  4273.9     .12       0  4291.9     .07       0  4314.1     .12       0
  4575.6     .07       0  4611.7     .12       0  4786.9      .1       0
  4827.5     .05       0  4840.9      .1       0  4926.5     .07       0
  5203.6     .12       0
Bank Sta=4827.5,4840.9
XS Rating Curve= 0 ,0
Exp/Cntr=0.3,0.1

Type RM Length L Ch R = 1 ,1294    ,774,774,774
BEGIN DESCRIPTION:
X18054
END DESCRIPTION:
XS GIS Cut Line= 3
      2457795.36     13593032.89      2458580.07     13593289.83
      2459239.82     13593220.38
#Sta/Elev= 30
  4081.5  229.46  4219.4  229.46  4321.9  229.39  4487.1   229.6    4520  229.47
  4628.3  226.12  4679.2  227.46  4684.5   226.5  4711.1  226.95  4774.8  225.55
    4780  224.65  4806.6  225.67  4880.8   225.3  4901.9  226.02  4936.3  223.01
  4972.5  221.27  4992.6  221.59  4997.7  217.45  4998.2  216.95  5011.1  217.45
  5012.7  220.19  5035.5  221.94    5063   225.3  5092.4   225.6  5097.4  227.66
  5103.2  227.05  5113.3  227.75  5183.7  234.52  5233.9  236.44  5570.6   242.7
#Mann= 9 ,-1 , 0
  4081.5     .12       0  4219.4    .035       0  4321.9     .07       0
  4487.1      .1       0  4936.3    .035       0  4997.7    .035       0
  5011.1    .035       0  5035.5     .12       0  5233.9     .07       0
Bank Sta=4997.7,5011.1
XS Rating Curve= 0 ,0
Exp/Cntr=0.3,0.1

Type RM Length L Ch R = 1 ,520     ,422,422,422
BEGIN DESCRIPTION:
ANDERSON CREEK 1.0
END DESCRIPTION:
XS GIS Cut Line= 3
      2457856.96     13593409.78        2458525.       13593975.
      2459240.76     13593718.23
#Sta/Elev= 30
  4121.1  225.78  4159.1   226.1  4201.3  228.75  4499.5  227.93  4513.9  228.11
  4541.9  224.89  4549.6  222.95  4556.1  223.15  4584.7  219.56  4619.9  218.81
  4662.7  220.22  4686.2  219.78    4701  219.69  4904.5  224.25  4946.2  218.67
  4960.5  218.88  4982.3  217.38  4982.8  216.88  4995.8  217.38  5006.2  218.98
  5011.5  217.95  5017.4  219.07  5042.3   219.5  5059.9  221.96    5099   224.8
  5208.7  229.89  5449.5  228.18  5559.2  229.19  5704.6  232.47  5756.6  233.32
#Mann= 11 ,-1 , 0
  4121.1    .035       0  4159.1     .07       0  4499.5     .05       0
  4513.9     .07       0  4686.2    .035       0    4701      .1       0
  4982.3     .05       0  4995.8      .1       0    5099     .12       0
  5449.5     .07       0  5704.6     .12       0
Bank Sta=4982.3,4995.8
XS Rating Curve= 0 ,0
Exp/Cntr=0.3,0.1

Type RM Length L Ch R = 1 ,98      ,0,0,0
BEGIN DESCRIPTION:
X18053
END DESCRIPTION:
XS GIS Cut Line= 3
      2457927.31     13594005.12      2458580.07     13594359.28
       2459481.4     13594192.88
#Sta/Elev= 30
    4146  222.28  4234.4  221.33  4327.5  218.16  4445.9  217.18  4485.7  218.47
  4512.9  219.76  4556.1  218.76  4594.7  216.57  4666.3  218.23  4742.5  218.22
  4959.1  218.85  4964.8  218.93  4965.8  216.43  4967.3  215.43  5027.9  215.43
  5029.4  216.43    5036  219.19  5086.9  217.15    5097  217.69  5108.6  221.58
  5117.4  222.86  5198.7  225.37  5249.6  224.15  5280.1  221.74  5325.6  221.94
  5370.1  219.92  5570.5  225.44  5691.4  227.28  5756.9  228.16  5805.2  229.15
#Mann= 13 ,-1 , 0
    4146     .05       0  4445.9    .035       0  4485.7     .05       0
  4556.1    .035       0  4666.3      .1       0  4742.5     .05       0
  4959.1      .1       0  4965.8     .05       0  5029.4      .1       0
  5370.1     .12       0  5570.5     .07       0  5691.4    .035       0
  5756.9     .12       0
Bank Sta=4965.8,5029.4
XS Rating Curve= 0 ,0
Exp/Cntr=0.3,0.1

Chan Stop Cuts=-1
Use User Specified Reach Order=0
Composite Channel Slope=5