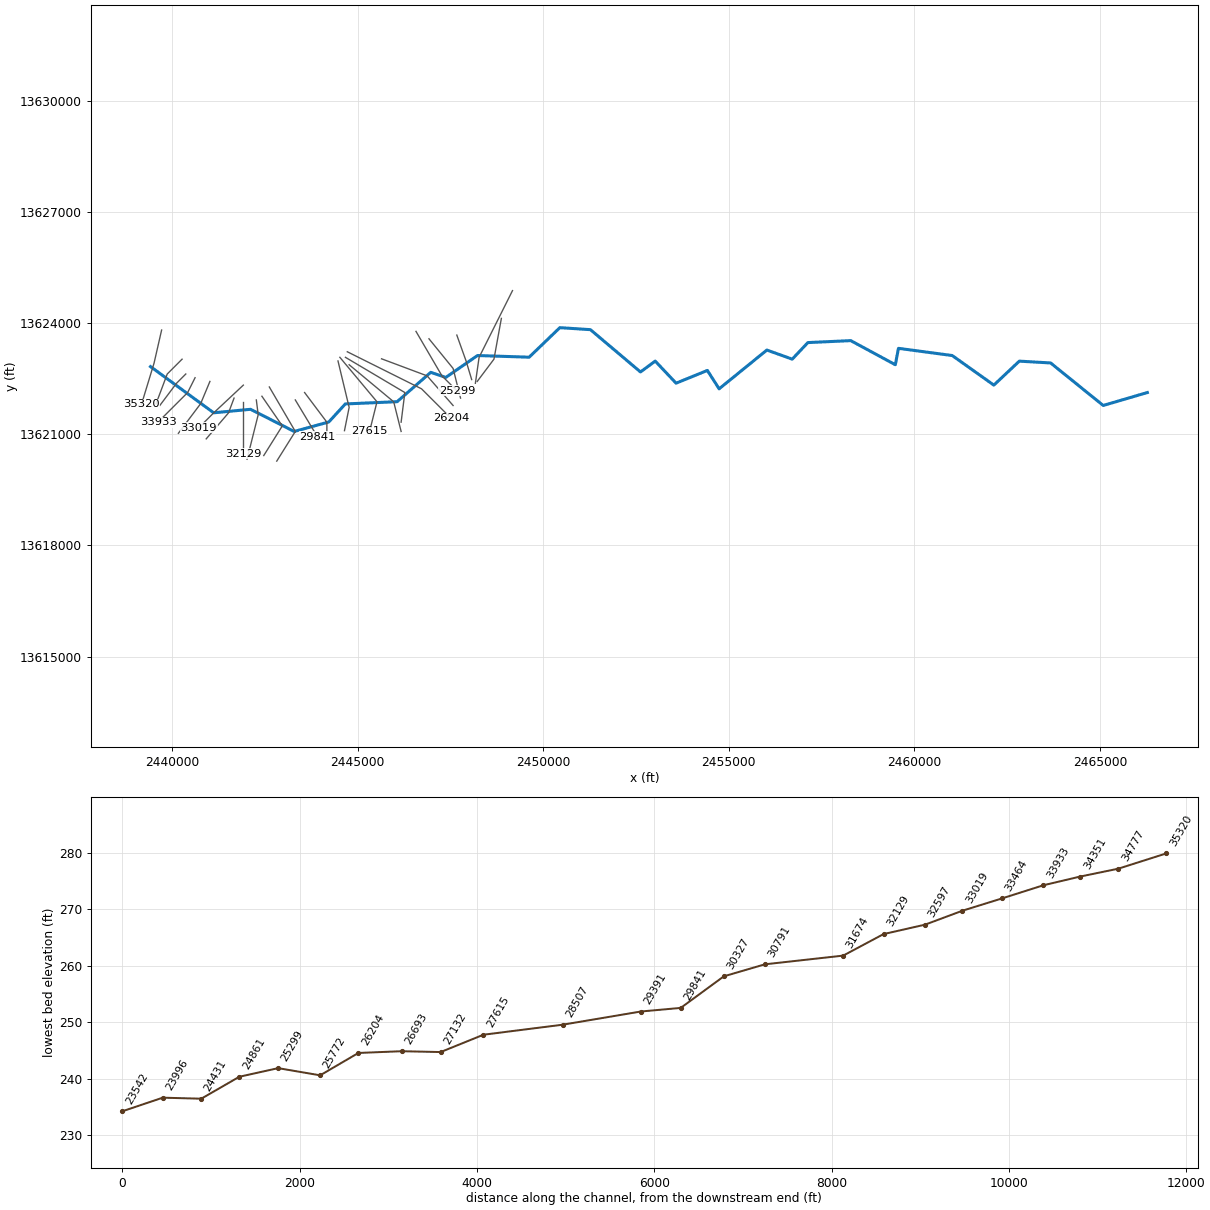
--- BIRDS CREEK.prj (project) ---

Proj Title=BIRDS CREEK Base Level Engineering
Current Plan=p01
Default Exp/Contr=0.3,0.1
English Units
Geom File=g01
Flow File=f01
Plan File=p01
Y Axis Title=Elevation
X Axis Title(PF)=Main Channel Distance
X Axis Title(XS)=Station
BEGIN DESCRIPTION:
BIRDS CREEK
END DESCRIPTION:
DSS Export Rating Curves= 0
DSS Export Rating Curve Sorted= 0
DSS Export Volume Flow Curves= 0
DXF OffsetX= 0
DXF OffsetY= 0
DXF ScaleX= 1
DXF ScaleY= 10

--- BIRDS CREEK.p01 (plan) ---

Plan Title=Multiple Run
Program Version=4.10
Short Identifier=Multiple
Geom File=g01
Flow File=f01
Subcritical Flow
K Sum by GR= 0
Std Step Tol= 0.01
Critical Tol= 0.01
Num of Std Step Trials= 20
Max Error Tol= 0.3
Flow Tol Ratio= 0.001
Split Flow NTrial= 30
Split Flow Tol= 0.02
Split Flow Ratio= 0.02
Log Output Level= 0
Friction Slope Method= 1
Unsteady Friction Slope Method= 2
Unsteady Bridges Friction Slope Method= 1
Parabolic Critical Depth
Global Vel Dist= 1 , 1 , 1
Global Log Level= 0
CheckData=True
Encroach Param=-1 ,0,0, 0
BEGIN DESCRIPTION:
Multiple Run
END DESCRIPTION:
Computation Interval=1HOUR
Output Interval=1HOUR
Run HTab= 0
Run UNet= 0
Run PostProcess= 0
Run WQNet= 0
UNET Theta= 1
UNET Theta Warmup= 1
UNET ZTol= 0.02
UNET ZSATol= 0.05
UNET MxIter= 20
UNET MaxInSteps= 0
UNET DtIC= 0
UNET DtMin= 0
UNET MaxCRTS= 20
UNET WFStab= 2
UNET SFStab= 1
UNET WFX= 1
UNET SFX= 1
UNET DSS MLevel= 4
UNET DZMax Abort= 100
UNET Convert EG Bridges= 0
UNET Use Existing IB Tables=-1
UNET Froude Reduction=False
UNET Froude Limit= 1
UNET Froude Power= 10
UNET Time Slicing=0,0, 5
UNET Junction Losses=0
Instantaneous Interval=1HOUR
Write IC File= 0
Write IC File at Sim End=0
Echo Input=False
Echo Parameters=False
Echo Output=False
Write Detailed= 0
WQ AD Non Conservative
WQ ULTIMATE=-1
WQ Max Comp Step=1HOUR
WQ Output Interval=15MIN
WQ Output Selected Increments= 0
WQ Output face flow=0
WQ Output face velocity=0
WQ Output face area=0
WQ Output face dispersion=0
WQ Output cell volume=0
WQ Output cell surface area=0
WQ Output cell continuity=0
WQ Output cumulative cell continuity=0
WQ Output face conc=0
WQ Output face dconc_dx=0
WQ Output face courant=0
WQ Output face peclet=0
WQ Output face adv mass=0
WQ Output face disp mass=0
WQ Output cell mass=0
WQ Output cell source sink temp=0
WQ Output cell source sink nsm=0
WQ Output MaxMinRange=-1
WQ Daily Max Min Mean=-1
WQ Daily Range=0
WQ Daily Time=0
WQ Create Restart=0
WQ Fixed Restart=0
WQ System Summary=0
WQ Use Fixed Temperature=0
Sorting and Armoring Iterations= 10
XS Update Threshold= 0.02
Hydraulics Update Threshold= 0.02
Energy Slope Method= 1
Volume Change Method= 0
XS Weighting Method= 0
Number of US Weighted Cross Sections= 1
Number of DS Weighted Cross Sections= 1
Upstream XS Weight=0.25
Main XS Weight=0.5
Downstream XS Weight=0.25
Number of DS XS's Weighted with US Boundary= 1
Upstream Boundary Weight= 1
Weight of XSs Associated with US Boundary= 0
Number of US XS's Weighted with DS Boundary= 1
Downstream Boundary Weight= 0.5
Weight of XSs Associated with DS Boundary= 0.5
Sediment Output Level= 4
Mass or Volume Output= 0
Output Increment Type= 1
Profile and TS Output Increment= 10
XS Output Flag= 0
XS Output Increment= 10
Disregard all LS=0
Disregard all Conn=0
Disregard all Breaches=0
Disregard all Pumps=0

--- BIRDS CREEK.f01 (steady flow) ---

Flow Title=Multiple
Number of Profiles=7
Profile Names=10-year,25-year,50-year,1pct_min,100-year,1pct_plu,500-year
River Rch & RM= BIRDS CREEK,Reach-1,35320
     868    1426    1939    1277    2547    5082    4353
River Rch & RM= BIRDS CREEK,Reach-1,32129
    1280    2146    2958    1971    3933    7848    6893
River Rch & RM= BIRDS CREEK,Reach-1,30791
    1293    2166    2983    1986    3962    7905    6926
River Rch & RM= BIRDS CREEK,Reach-1,27615
    1789    3040    4227    2837    5660   11294   10066
River Rch & RM= BIRDS CREEK,Reach-1,25299
    2039    3480    4855    3267    6518   13005   11653
River Rch & RM= BIRDS CREEK,Reach-1,23996
    2176    3710    5169    3473    6929   13826   12348
River Rch & RM= BIRDS CREEK,Reach-1,18560
    2162    3682    5127    3442    6868   13703   12222
River Rch & RM= BIRDS CREEK,Reach-1,17691
    2704    4633    6475    4360    8700   17359   15575
River Rch & RM= BIRDS CREEK,Reach-1,13568
    2837    4860    6792    4572    9122   18201   16317
River Rch & RM= BIRDS CREEK,Reach-1,10111
    2997    5139    7187    4840    9656   19267   17289
River Rch & RM= BIRDS CREEK,Reach-1,2059
    2958    5060    7065    4750    9477   18909   16911
Boundary for River Rch & Prof#=BIRDS CREEK,Reach-1,1
Up Type=0
Dn Type=3
Dn Slope=0.005
Boundary for River Rch & Prof#=BIRDS CREEK,Reach-1,2
Up Type=0
Dn Type=3
Dn Slope=0.005
Boundary for River Rch & Prof#=BIRDS CREEK,Reach-1,3
Up Type=0
Dn Type=3
Dn Slope=0.005
Boundary for River Rch & Prof#=BIRDS CREEK,Reach-1,4
Up Type=0
Dn Type=3
Dn Slope=0.005
Boundary for River Rch & Prof#=BIRDS CREEK,Reach-1,5
Up Type=0
Dn Type=3
Dn Slope=0.005
Boundary for River Rch & Prof#=BIRDS CREEK,Reach-1,6
Up Type=0
Dn Type=3
Dn Slope=0.005
Boundary for River Rch & Prof#=BIRDS CREEK,Reach-1,7
Up Type=0
Dn Type=3
Dn Slope=0.005

--- BIRDS CREEK.g01 (geometry) ---

Geom Title=Existing Conditions
Program Version=4.10

River Reach=BIRDS CREEK     ,Reach-1
Reach XY= 30
        2439425.       13622825.      2441126.47     13621578.55
      2442119.14     13621672.94      2443295.03     13621074.56
       2444227.3     13621330.83      2444671.77     13621817.16
      2446066.72     13621878.06      2446972.69     13622669.92
      2447378.43     13622532.79      2448231.51      13623123.4
      2449623.55     13623078.53      2450449.92      13623875.2
      2451273.42     13623821.33      2452622.46     13622679.96
      2453019.12     13622973.04      2453580.85     13622377.06
      2454423.55     13622721.47      2454740.41     13622224.86
      2456026.46     13623271.48      2456709.73     13623025.38
      2457130.93     13623472.76      2458285.19     13623525.45
      2459485.81     13622875.72       2459571.3     13623317.33
      2461019.16     13623122.95      2462140.28     13622325.38
      2462826.64     13622971.86      2463669.14     13622922.94
       2465085.5     13621776.19        2466275.       13622125.

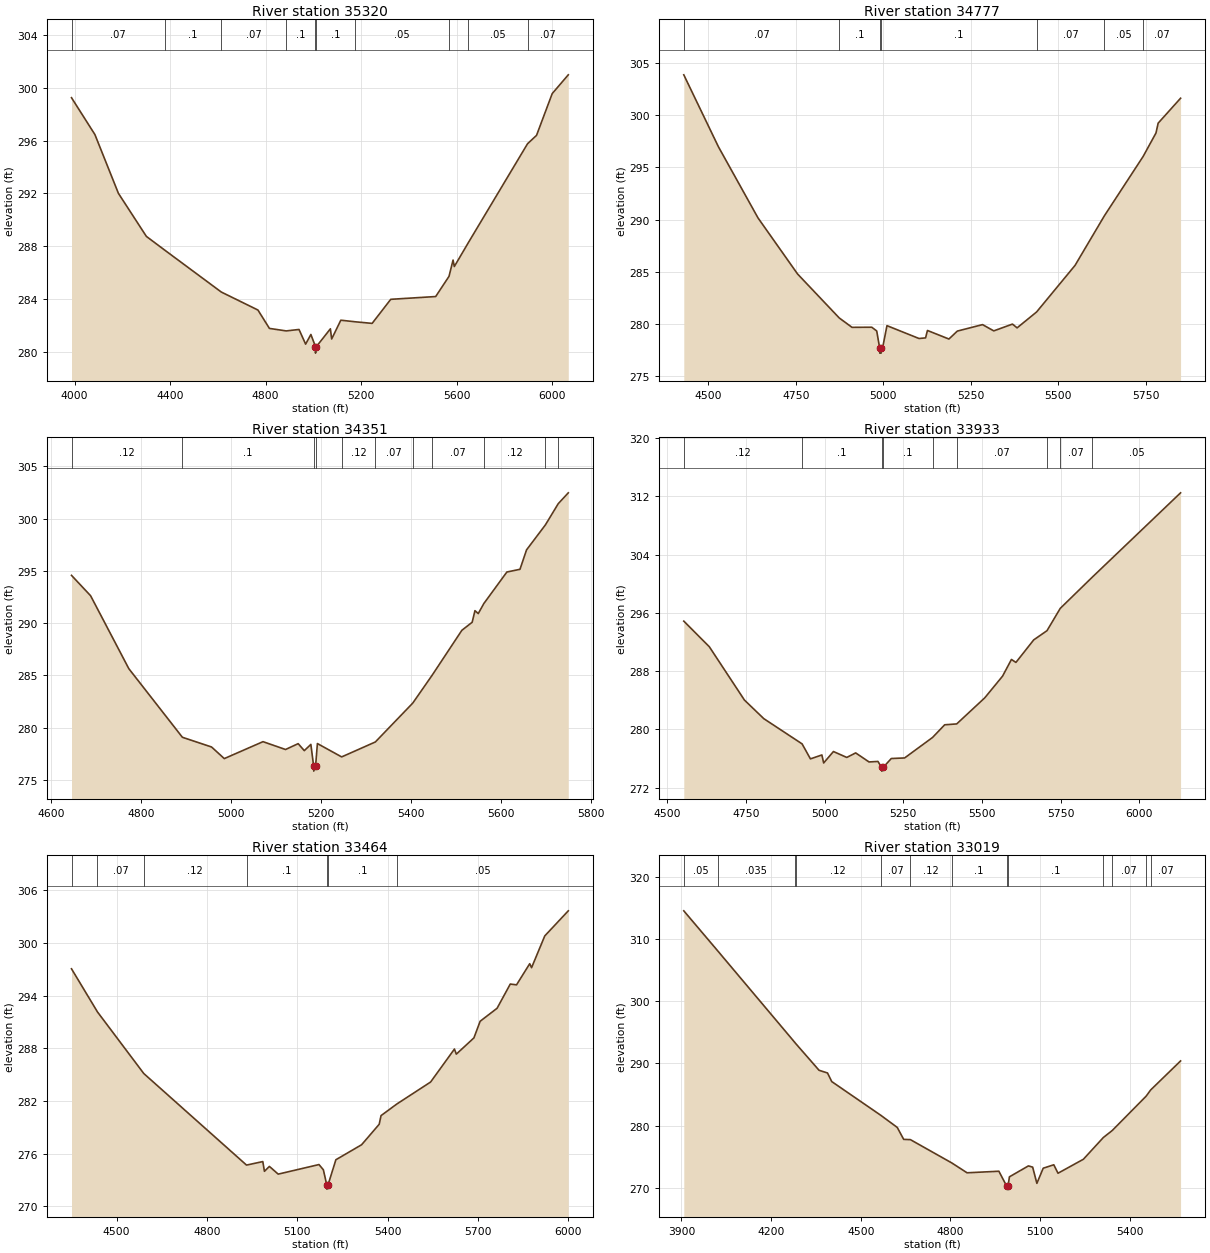
Type RM Length L Ch R = 1 ,35320   ,543,543,543
BEGIN DESCRIPTION:
BIRDS CREEK 55.0
END DESCRIPTION:
XS GIS Cut Line= 3
      2439723.86     13623810.63      2439520.26     13622918.67
      2439180.94     13621803.77
#Sta/Elev= 30
  3987.2  299.24  4085.3  296.45  4183.5  292.01  4300.7  288.75  4378.4   287.7
  4614.5  284.54  4767.9  283.18    4816  281.79  4886.1   281.6  4939.9  281.71
  4967.6   280.6  4989.6  281.33  5008.7  280.42    5009  279.92    5013  280.42
  5071.3  281.76  5076.6  280.99    5115  282.41  5175.4  282.29  5246.1  282.17
  5324.1  283.99  5512.2   284.2  5568.1  285.73    5585  286.96  5590.3  286.47
  5648.8  288.27    5897  295.76  5934.5  296.39  6000.2  299.55  6067.5  300.97
#Mann= 10 ,-1 , 0
  3987.2     .07       0  4378.4      .1       0  4614.5     .07       0
  4886.1      .1       0  5008.7     .05       0    5013      .1       0
  5175.4     .05       0  5568.1     .07       0  5648.8     .05       0
    5897     .07       0
Bank Sta=5008.7,5013
XS Rating Curve= 0 ,0
Exp/Cntr=0.3,0.1

Type RM Length L Ch R = 1 ,34777   ,426,426,426
BEGIN DESCRIPTION:
BIRDS CREEK 54.0
END DESCRIPTION:
XS GIS Cut Line= 3
      2440274.98     13623024.98        2439875.       13622625.
      2439574.99     13621824.96
#Sta/Elev= 30
  4429.6  303.86  4528.6  296.97  4641.7  290.16  4754.8  284.79  4873.9  280.58
  4910.4  279.68    4967  279.69  4981.1  279.33  4989.5  277.71  4989.8  277.21
  4993.6  277.21  4993.9  277.71  4997.9  277.71  5010.4  279.84  5102.1  278.61
  5120.8  278.67  5126.1  279.38  5187.5  278.56  5211.5  279.32  5283.6  279.94
  5315.7  279.34  5369.1  279.99  5382.4  279.63  5438.1  281.15    5548  285.61
  5631.9  290.36  5742.6  296.04  5779.4  298.29  5785.6  299.23  5849.7  301.62
#Mann= 7 ,-1 , 0
  4429.6     .07       0  4873.9      .1       0  4989.5     .05       0
  4993.9      .1       0  5438.1     .07       0  5631.9     .05       0
  5742.6     .07       0
Bank Sta=4989.5,4993.9
XS Rating Curve= 0 ,0
Exp/Cntr=0.3,0.1

Type RM Length L Ch R = 1 ,34351   ,418,418,418
BEGIN DESCRIPTION:
BIRDS CREEK 53.0
END DESCRIPTION:
XS GIS Cut Line= 3
      2440374.99     13622624.99        2440125.       13622375.
      2439675.02     13621775.03
#Sta/Elev= 30
    4646  294.57  4688.4  292.62  4773.3  285.64  4892.3  279.07  4957.1  278.14
  4985.4  277.03  5071.4  278.65  5121.4   277.9  5149.5  278.46  5163.1  277.79
  5177.7  278.39  5183.8  276.33  5184.1  275.83  5188.2  276.33  5192.2  278.47
  5246.1  277.19  5320.9  278.62    5404  282.34  5446.8  284.99  5513.1  289.31
    5536  290.08  5542.2  291.19  5549.5  290.91  5561.9  291.87  5613.1  294.89
  5642.2  295.15  5656.8  297.01  5698.5  299.39  5727.2  301.43  5749.5  302.47
#Mann= 11 ,-1 , 0
    4646     .12       0  4892.3      .1       0  5183.8     .05       0
  5188.2      .1       0  5246.1     .12       0  5320.9     .07       0
    5404     .12       0  5446.8     .07       0  5561.9     .12       0
  5698.5     .07       0  5727.2     .12       0
Bank Sta=5183.8,5188.2
XS Rating Curve= 0 ,0
Exp/Cntr=0.3,0.1

Type RM Length L Ch R = 1 ,33933   ,469,469,469
BEGIN DESCRIPTION:
BIRDS CREEK 52.0
END DESCRIPTION:
XS GIS Cut Line= 3
      2440624.98     13622524.96        2440425.       13622125.
      2439625.03     13621325.03
#Sta/Elev= 30
  4552.6  294.87  4633.6  291.36  4745.4  284.03  4806.9  281.48  4928.5  278.02
    4955  275.96  4991.4   276.5    4997   275.4  5028.1  276.97  5070.5  276.16
  5098.8  276.78  5141.2  275.54  5169.5  275.61  5181.4  274.78  5181.7  274.28
  5185.9  274.78  5211.9  276.01  5254.3  276.09    5343   278.9  5381.6  280.64
  5419.8  280.76  5508.9  284.34  5565.5  287.32  5593.7  289.61  5607.9   289.2
  5664.4  292.29  5706.7  293.56  5748.8  296.62  5850.2  300.89  6131.1  312.48
#Mann= 9 ,-1 , 0
  4552.6     .12       0  4928.5      .1       0  5181.4     .05       0
  5185.9      .1       0    5343     .12       0  5419.8     .07       0
  5706.7     .12       0  5748.8     .07       0  5850.2     .05       0
Bank Sta=5181.4,5185.9
XS Rating Curve= 0 ,0
Exp/Cntr=0.3,0.1

Type RM Length L Ch R = 1 ,33464   ,445,445,445
BEGIN DESCRIPTION:
BIRDS CREEK 51.0
END DESCRIPTION:
XS GIS Cut Line= 3
        2441025.       13622425.        2440775.       13621825.
        2440175.       13621025.
#Sta/Elev= 30
    4350  297.06  4436.3  292.14  4590.1  285.12  4931.3  274.68  4985.4  275.08
  4990.8  273.97  5007.3  274.53  5036.5  273.65  5171.9  274.74  5186.5  274.15
  5197.7  272.44    5198  271.94  5202.2  272.44  5228.1  275.29  5313.5     277
  5371.9  279.33  5378.1  280.32  5430.3  281.64  5542.7  284.15  5621.9  287.91
  5628.1  287.33  5686.5  289.18  5707.3  291.08  5763.5  292.56  5807.3  295.32
  5828.1  295.23  5871.9  297.64  5878.1  297.19  5921.9  300.81    6000  303.67
#Mann= 7 ,-1 , 0
    4350     .05       0  4436.3     .07       0  4590.1     .12       0
  4931.3      .1       0  5197.7     .05       0  5202.2      .1       0
  5430.3     .05       0
Bank Sta=5197.7,5202.2
XS Rating Curve= 0 ,0
Exp/Cntr=0.3,0.1

Type RM Length L Ch R = 1 ,33019   ,422,422,422
BEGIN DESCRIPTION:
BIRDS CREEK 50.0
END DESCRIPTION:
XS GIS Cut Line= 3
      2441924.97     13622324.97        2441125.       13621575.
      2440725.02     13621175.02
#Sta/Elev= 30
  3907.8  314.58  4020.7  308.17    4281  293.29  4282.5   293.2  4360.3  288.91
  4388.7  288.47  4402.8  287.09  4566.9  281.66  4622.1   279.7  4643.6  277.78
    4666  277.74  4804.4  273.99  4855.6   272.4  4962.1  272.65    4988  270.27
  4988.4  269.77  4992.8  270.27  4997.3  271.75  5060.9  273.51  5075.1  273.31
  5089.2   270.7  5110.4  273.14  5145.8  273.69  5159.9  272.33  5244.8  274.58
  5311.6  278.08  5341.4  279.21    5455  284.75  5469.8  285.73    5570  290.41
#Mann= 13 ,-1 , 0
  3907.8     .05       0  4020.7    .035       0    4281     .05       0
  4282.5     .12       0  4566.9     .07       0    4666     .12       0
  4804.4      .1       0    4988     .05       0  4992.8      .1       0
  5311.6     .05       0  5341.4     .07       0    5455     .05       0
  5469.8     .07       0
Bank Sta=4988,4992.8
XS Rating Curve= 0 ,0
Exp/Cntr=0.3,0.1

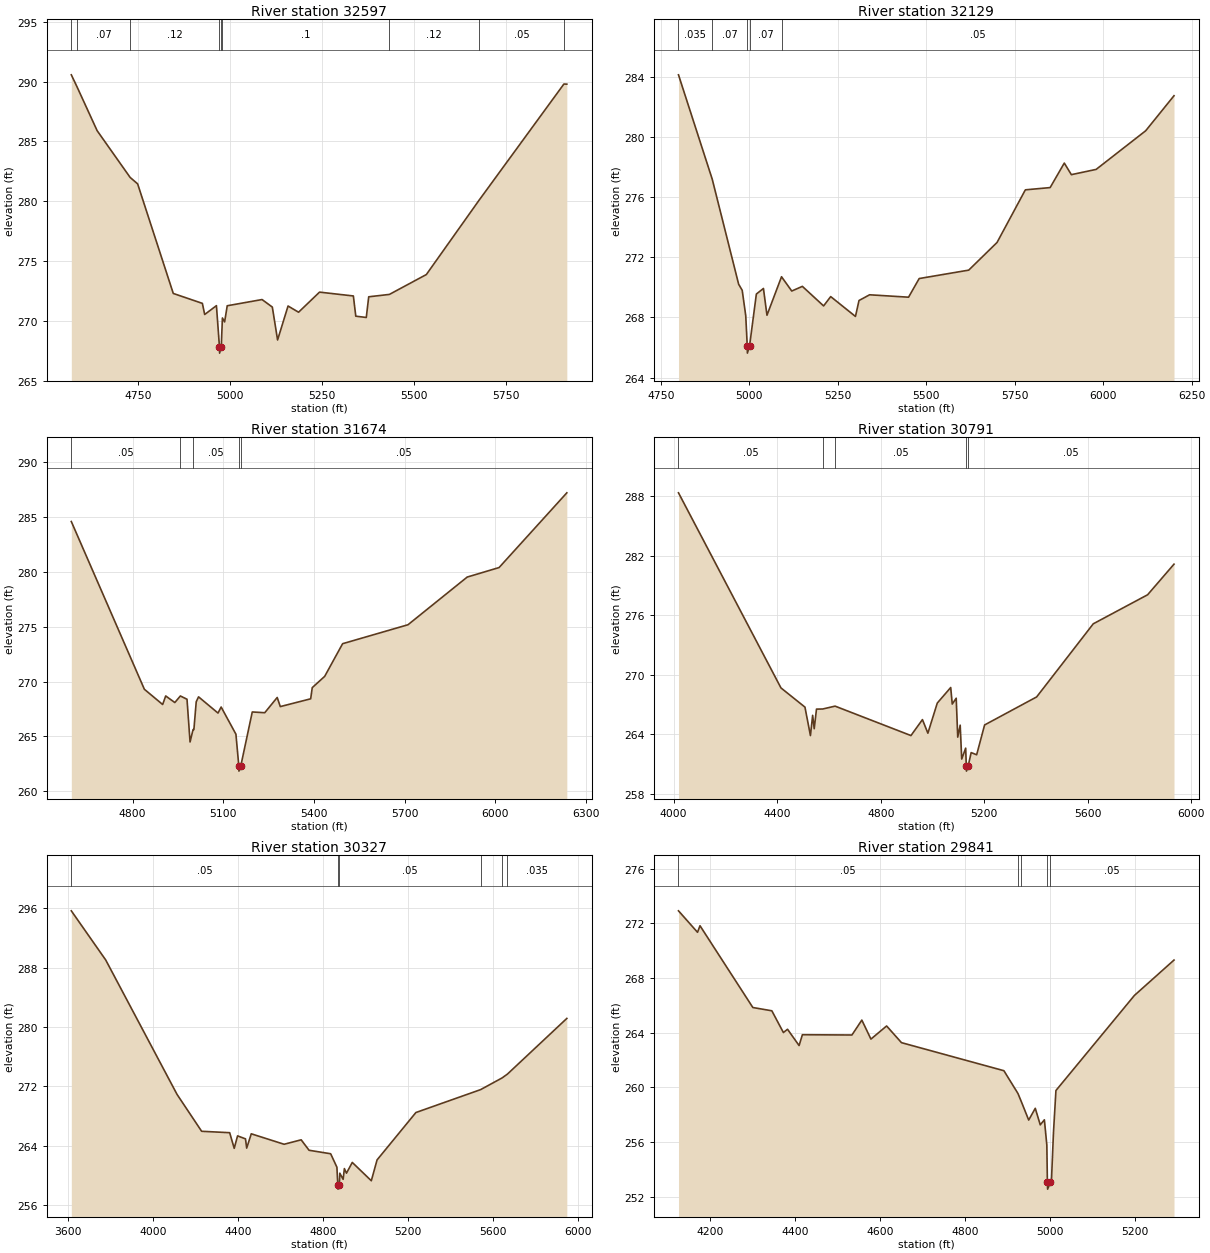
Type RM Length L Ch R = 1 ,32597   ,468,468,468
BEGIN DESCRIPTION:
BIRDS CREEK 49.0
END DESCRIPTION:
XS GIS Cut Line= 3
      2441674.98     13621974.96        2441525.       13621575.
        2440925.     13620875.01
#Sta/Elev= 30
  4567.8  290.57  4583.3  289.57  4638.1   285.9    4728  281.99  4748.4  281.45
  4845.4  272.29  4924.6  271.46  4930.9  270.53  4962.9  271.27  4971.2   267.8
  4971.5   267.3    4976   267.8  4979.2  270.24  4985.2  269.91  4992.3  271.26
  5087.1  271.78  5115.1  271.15  5129.4   268.4  5157.9  271.24  5186.5  270.72
  5243.6   272.4  5335.7  272.08  5342.3  270.39  5370.9  270.28  5377.5  272.01
  5433.9  272.21  5534.4  273.87  5678.1  280.09  5908.9   289.8  5916.9  289.79
#Mann= 9 ,-1 , 0
  4567.8    .035       0  4583.3     .07       0    4728     .12       0
  4971.2     .05       0    4976     .12       0  4979.2      .1       0
  5433.9     .12       0  5678.1     .05       0  5908.9     .07       0
Bank Sta=4971.2,4976
XS Rating Curve= 0 ,0
Exp/Cntr=0.3,0.1

Type RM Length L Ch R = 1 ,32129   ,455,455,455
BEGIN DESCRIPTION:
BIRDS CREEK 48.0
END DESCRIPTION:
XS GIS Cut Line= 3
        2441925.     13621875.03        2441925.       13621675.
        2441925.     13620475.03
#Sta/Elev= 30
    4800  284.14  4895.3   277.2    4970  270.21    4980  269.81    4990  268.12
  4994.2  266.13  4994.7  265.63  5000.9  266.13    5020  269.56    5040  269.93
    5050  268.15  5091.1  270.71    5120  269.76    5150  270.07    5210  268.77
    5230  269.39    5300  268.07    5310  269.13    5340  269.51    5450  269.35
    5480  270.59    5620  271.15    5700  272.99    5780  276.49    5850  276.64
    5890  278.27    5910   277.5    5980  277.85    6120  280.42    6200  282.75
#Mann= 5 ,-1 , 0
    4800    .035       0  4895.3     .07       0  4994.2     .05       0
  5000.9     .07       0  5091.1     .05       0
Bank Sta=4994.2,5000.9
XS Rating Curve= 0 ,0
Exp/Cntr=0.3,0.1

Type RM Length L Ch R = 1 ,31674   ,883,883,883
BEGIN DESCRIPTION:
BIRDS CREEK 47.0
END DESCRIPTION:
XS GIS Cut Line= 3
        2442275.     13621924.97        2442325.       13621525.
        2442025.     13620325.02
#Sta/Elev= 30
  4596.9   284.6  4838.7  269.29  4899.2   267.9  4909.3  268.68  4939.5  268.08
  4957.8  268.68  4979.8  268.38  4989.9  264.48  4999.8  265.61  5002.6  265.61
  5010.3  268.15    5018   268.6  5082.4  267.12  5092.8  267.67  5141.7  265.19
  5151.2  262.32  5151.7  261.82    5158  262.32  5195.8  267.22  5237.1  267.15
  5278.3  268.54  5288.6  267.71  5389.1  268.42  5394.3  269.44  5435.5  270.47
  5494.8  273.45  5711.2  275.18  5907.1  279.53  6012.7   280.4  6236.9  287.22
#Mann= 5 ,-1 , 0
  4596.9     .05       0  4957.8     .07       0  4999.8     .05       0
  5151.2     .05       0    5158     .05       0
Bank Sta=5151.2,5158
XS Rating Curve= 0 ,0
Exp/Cntr=0.3,0.1

Type RM Length L Ch R = 1 ,30791   ,464,464,464
BEGIN DESCRIPTION:
BIRDS CREEK 46.0
END DESCRIPTION:
XS GIS Cut Line= 3
        2442425.     13622025.01        2442975.       13621225.
      2442475.02     13620425.02
#Sta/Elev= 30
  4018.7  288.37  4414.5  268.68  4507.2  266.74  4528.4  263.87  4536.9  265.91
    4543  264.56  4551.8  266.54  4575.7  266.55  4623.6  266.84  4916.7  263.87
  4961.1  265.48  4982.1  264.11  5018.4  267.15  5070.3  268.72  5076.2  267.05
  5091.5  267.64  5097.4  263.71  5106.9  264.92  5112.8   261.5  5128.1   262.6
  5130.5  260.78    5131  260.28  5137.5  260.78  5149.3  262.15  5170.5  261.93
  5201.2  264.94  5402.3  267.77    5621  275.15  5830.9  278.08  5932.9  281.17
#Mann= 5 ,-1 , 0
  4018.7     .05       0  4575.7     .07       0  4623.6     .05       0
  5130.5     .05       0  5137.5     .05       0
Bank Sta=5130.5,5137.5
XS Rating Curve= 0 ,0
Exp/Cntr=0.3,0.1

Type RM Length L Ch R = 1 ,30327   ,486,486,486
BEGIN DESCRIPTION:
BIRDS CREEK 45.0
END DESCRIPTION:
XS GIS Cut Line= 3
      2442625.02     13622274.96        2443325.       13621075.
        2442825.       13620275.
#Sta/Elev= 30
  3614.6  295.68  3776.6  289.05  4112.4  270.92  4228.1  265.95    4360  265.76
  4381.5  263.65  4397.2  265.33  4434.5  264.93  4440.2  263.68  4461.7  265.61
  4616.4   264.2  4696.6   264.8  4733.8  263.39  4835.5  262.92  4864.9   261.1
  4869.2  258.65  4869.7  258.15  4876.2  258.65  4878.5   260.3  4894.2  259.47
    4900  260.92  4909.9   260.3  4937.2  261.75  5026.8  259.28  5053.9  262.09
  5236.7  268.48  5541.4  271.57  5642.1  273.14  5667.5  273.66  5947.2  281.17
#Mann= 6 ,-1 , 0
  3614.6     .05       0  4869.2     .05       0  4876.2     .05       0
  5541.4    .035       0  5642.1     .05       0  5667.5    .035       0
Bank Sta=4869.2,4876.2
XS Rating Curve= 0 ,0
Exp/Cntr=0.3,0.1

Type RM Length L Ch R = 1 ,29841   ,450,450,450
BEGIN DESCRIPTION:
BIRDS CREEK 44.0
END DESCRIPTION:
XS GIS Cut Line= 3
      2443324.98     13621925.04        2443775.       13621175.
      2443924.98     13620925.03
#Sta/Elev= 30
  4125.3  272.91  4170.1  271.34  4175.9  271.82  4300.3  265.84    4345   265.6
  4372.2  264.01  4381.9  264.25  4409.1  263.06  4416.9  263.85  4533.5  263.83
  4556.8  264.92  4578.2  263.53  4615.1  264.49  4650.1  263.27  4891.1  261.22
  4924.3  259.55  4932.5  258.93  4949.5  257.61    4965  258.47  4976.7  257.26
  4986.4  257.63  4992.2  255.78  4993.5  253.06    4994  252.56  5000.7  253.06
  5002.9  253.06  5007.8  256.69  5013.6  259.77  5198.2  266.72  5291.5  269.31
#Mann= 5 ,-1 , 0
  4125.3     .05       0  4924.3     .07       0  4932.5     .05       0
  4993.5     .05       0  5000.7     .05       0
Bank Sta=4993.5,5000.7
XS Rating Curve= 0 ,0
Exp/Cntr=0.3,0.1

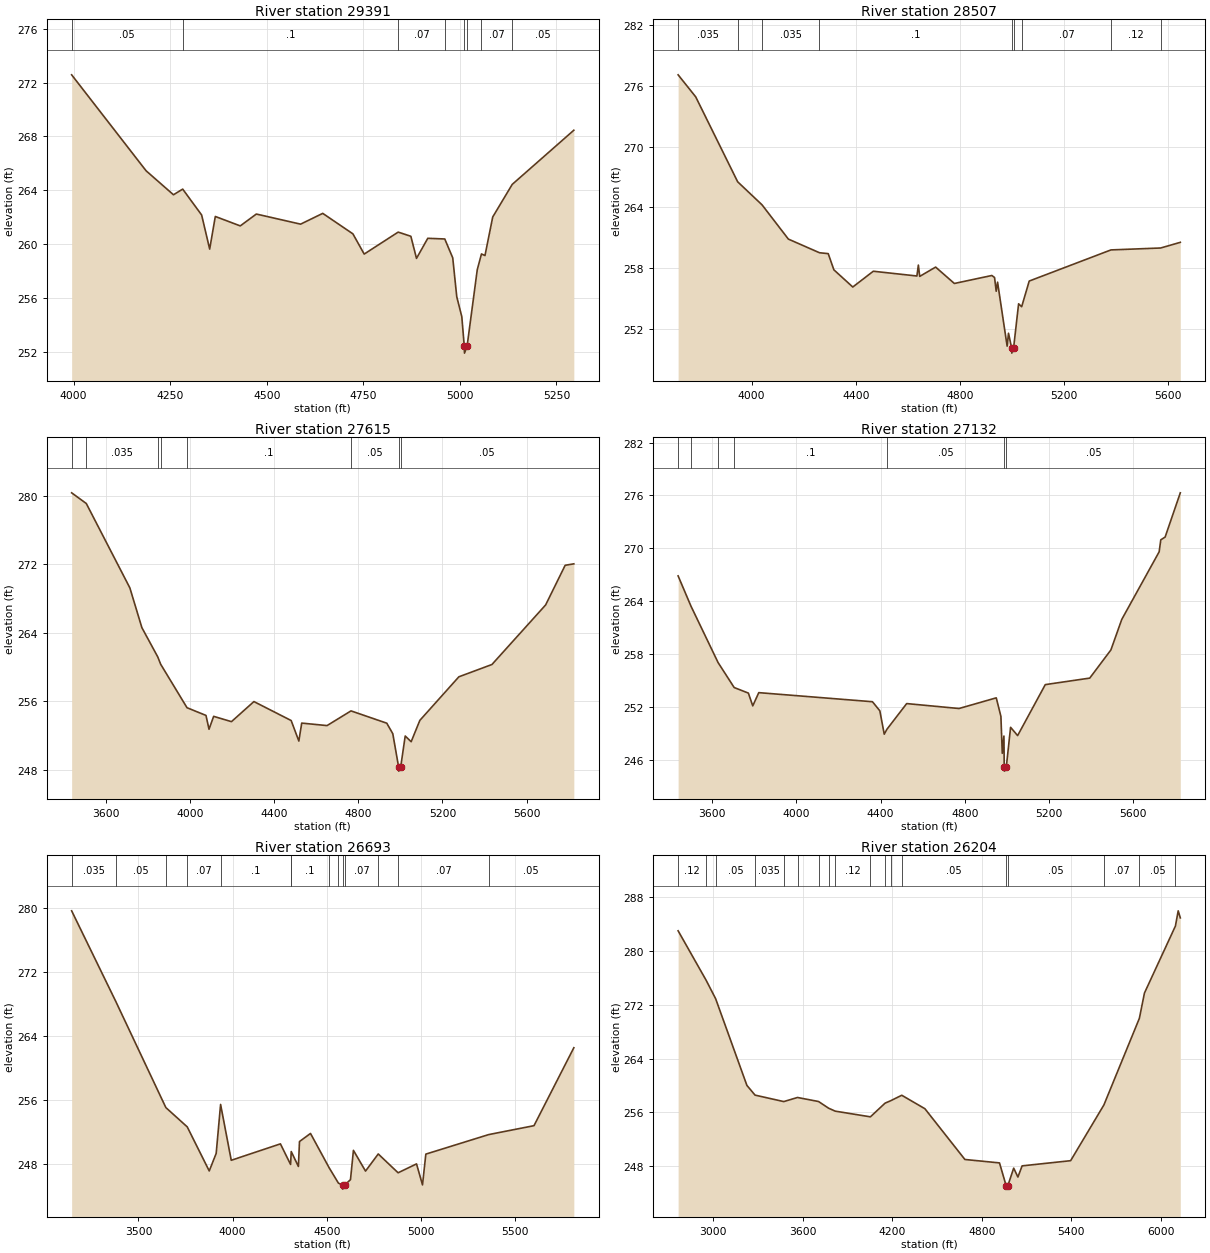
Type RM Length L Ch R = 1 ,29391   ,884,884,884
BEGIN DESCRIPTION:
BIRDS CREEK 43.0
END DESCRIPTION:
XS GIS Cut Line= 3
      2443574.99     13622125.02        2444175.       13621325.
        2444175.     13621025.02
#Sta/Elev= 30
  3994.9  272.57  4187.6  265.45  4258.5  263.67  4282.4  264.09  4331.4  262.17
  4352.2  259.64  4366.8  262.06  4431.4  261.36    4473  262.24  4587.6  261.49
  4644.9  262.29    4723  260.77  4752.2  259.27  4840.2   260.9    4873  260.59
  4887.6  258.95  4916.8  260.44  4960.8  260.39  4981.4  258.99  4991.8  256.11
  5004.9  254.62  5011.3  252.42  5011.8  251.92  5018.5  252.42  5044.9  258.11
  5055.8  259.28  5064.9  259.16  5084.9  262.02  5135.4  264.44  5294.9  268.46
#Mann= 8 ,-1 , 0
  3994.9     .05       0  4282.4      .1       0  4840.2     .07       0
  4960.8     .12       0  5011.3     .05       0  5018.5     .12       0
  5055.8     .07       0  5135.4     .05       0
Bank Sta=5011.3,5018.5
XS Rating Curve= 0 ,0
Exp/Cntr=0.3,0.1

Type RM Length L Ch R = 1 ,28507   ,892,892,892
BEGIN DESCRIPTION:
BIRDS CREEK 42.0
END DESCRIPTION:
XS GIS Cut Line= 3
      2444474.47     13622976.82        2444775.       13621725.
      2444648.98     13621095.99
#Sta/Elev= 30
  3717.6  277.11  3785.2  274.93  3946.3  266.53  4039.9  264.25  4141.1  260.86
  4260.6  259.51  4294.2  259.42  4315.9  257.82  4388.5  256.12  4467.3  257.68
  4634.8  257.21  4640.4  258.29  4645.5  257.17  4706.7  258.09  4778.7  256.47
  4922.7  257.26    4933  257.06  4939.4   255.7  4944.6   256.6  4981.4  250.27
  4986.6  251.55  4998.8  250.08  4999.3  249.58  5006.1  250.08  5025.4  254.46
  5037.2  254.17  5066.2  256.71  5380.2  259.79  5571.2  259.98  5646.5  260.54
#Mann= 9 ,-1 , 0
  3717.6    .035       0  3946.3     .07       0  4039.9    .035       0
  4260.6      .1       0  4998.8     .05       0  5006.1      .1       0
  5037.2     .07       0  5380.2     .12       0  5571.2     .05       0
Bank Sta=4998.8,5006.1
XS Rating Curve= 0 ,0
Exp/Cntr=0.3,0.1

Type RM Length L Ch R = 1 ,27615   ,483,483,483
BEGIN DESCRIPTION:
BIRDS CREEK 41.0
END DESCRIPTION:
XS GIS Cut Line= 3
      2444525.03     13623074.97        2445525.       13621875.
      2445325.01     13621075.03
#Sta/Elev= 30
  3437.6  280.38  3507.2  279.13  3714.2  269.26  3771.4   264.6  3846.6  261.19
  3860.7  260.32  3985.9  255.23    4076  254.33  4090.4  252.71  4112.5  254.22
  4197.1   253.6  4303.8  255.95  4480.9  253.73  4517.3  251.33    4531  253.43
  4651.4  253.14  4765.2  254.86  4935.2  253.42  4963.8  252.19  4991.4  248.31
  4991.9  247.81  5001.4  248.31  5022.8  251.92  5051.1  251.25  5092.4  253.75
  5277.9  258.85  5435.1  260.29  5690.2  267.26    5783   271.9  5824.2  272.07
#Mann= 8 ,-1 , 0
  3437.6     .12       0  3507.2    .035       0  3846.6     .05       0
  3860.7     .07       0  3985.9      .1       0  4765.2     .05       0
  4991.4     .05       0  5001.4     .05       0
Bank Sta=4991.4,5001.4
XS Rating Curve= 0 ,0
Exp/Cntr=0.3,0.1

Type RM Length L Ch R = 1 ,27132   ,439,439,439
BEGIN DESCRIPTION:
BIRDS CREEK 40.0
END DESCRIPTION:
XS GIS Cut Line= 3
      2444774.98     13622875.01        2445975.       13621875.
        2446175.     13621074.99
#Sta/Elev= 30
  3437.9  266.88  3498.8  263.46  3627.7  257.06  3704.3  254.22  3771.8  253.59
  3792.6  252.14  3821.3  253.64  4361.5  252.61  4396.6  251.58  4417.5  248.93
  4430.4  249.49  4524.2   252.4  4772.8  251.84  4949.9  253.05    4972  250.95
  4978.5  246.76  4986.3  248.72  4987.8  245.24  4988.3  244.74  4997.8  245.24
    5018  249.71  5051.5  248.77  5182.9  254.55  5394.2  255.29  5494.7  258.48
  5546.3  261.94  5724.1  269.61  5731.8  270.97  5752.4  271.28  5824.6   276.3
#Mann= 7 ,-1 , 0
  3437.9    .035       0  3498.8     .05       0  3627.7     .07       0
  3704.3      .1       0  4430.4     .05       0  4987.8     .05       0
  4997.8     .05       0
Bank Sta=4987.8,4997.8
XS Rating Curve= 0 ,0
Exp/Cntr=0.3,0.1

Type RM Length L Ch R = 1 ,26693   ,489,489,489
BEGIN DESCRIPTION:
BIRDS CREEK 39.0
END DESCRIPTION:
XS GIS Cut Line= 3
      2444674.97     13623075.02        2446275.       13622125.
        2446175.     13621325.04
#Sta/Elev= 30
  3145.2  279.63  3380.2  268.29  3645.5  255.07  3759.1  252.66  3875.9  247.16
  3912.8  249.35  3936.2  255.46  3992.8  248.49  4253.9  250.54  4307.9  247.97
  4311.4  249.58  4349.4  247.72  4355.2  250.83  4413.7  251.84  4513.1  247.54
    4562  245.64  4583.7  245.39  4584.2  244.89  4594.3  245.39    4626  246.07
  4641.7  249.73  4705.9  247.14  4773.5  249.28  4878.9  246.93  4976.8  248.04
  5008.5  245.42  5026.2  249.26  5360.3   251.7  5600.6  252.81  5812.2  262.54
#Mann= 14 ,-1 , 0
  3145.2    .035       0  3380.2     .05       0  3645.5    .035       0
  3759.1     .07       0  3936.2      .1       0  4307.9     .12       0
  4311.4      .1       0  4513.1     .05       0    4562     .07       0
  4583.7     .05       0  4594.3     .07       0  4773.5     .05       0
  4878.9     .07       0  5360.3     .05       0
Bank Sta=4583.7,4594.3
XS Rating Curve= 0 ,0
Exp/Cntr=0.3,0.1

Type RM Length L Ch R = 1 ,26204   ,432,432,432
BEGIN DESCRIPTION:
BIRDS CREEK 38.0
END DESCRIPTION:
XS GIS Cut Line= 3
        2444725.       13623225.        2446725.       13622225.
      2447524.97     13621425.03
#Sta/Elev= 30
  2763.9     283  2952.1  275.63  3015.5   272.9  3225.1  260.01  3279.9  258.56
  3472.3   257.6  3564.5  258.21  3705.4  257.61  3772.9  256.62    3817  256.18
  4053.2  255.33  4151.8  257.37  4189.6  257.73  4263.4  258.54  4418.6  256.54
  4686.9  248.99  4918.9  248.48  4963.7  245.08  4964.2  244.58  4974.7  245.08
  5014.1   247.7  5042.4  246.38  5070.7  248.04  5395.9  248.81    5619   257.1
  5856.8  269.98  5890.9  273.74  6098.6  283.71  6117.2  285.97  6131.3  284.92
#Mann= 18 ,-1 , 0
  2763.9     .12       0  2952.1    .035       0  3015.5     .05       0
  3279.9    .035       0  3472.3     .05       0  3564.5     .07       0
  3705.4     .12       0  3772.9     .07       0    3817     .12       0
  4053.2    .035       0  4151.8     .05       0  4189.6    .035       0
  4263.4     .05       0  4963.7     .05       0  4974.7     .05       0
    5619     .07       0  5856.8     .05       0  6098.6    .035       0
Bank Sta=4963.7,4974.7
XS Rating Curve= 0 ,0
Exp/Cntr=0.3,0.1

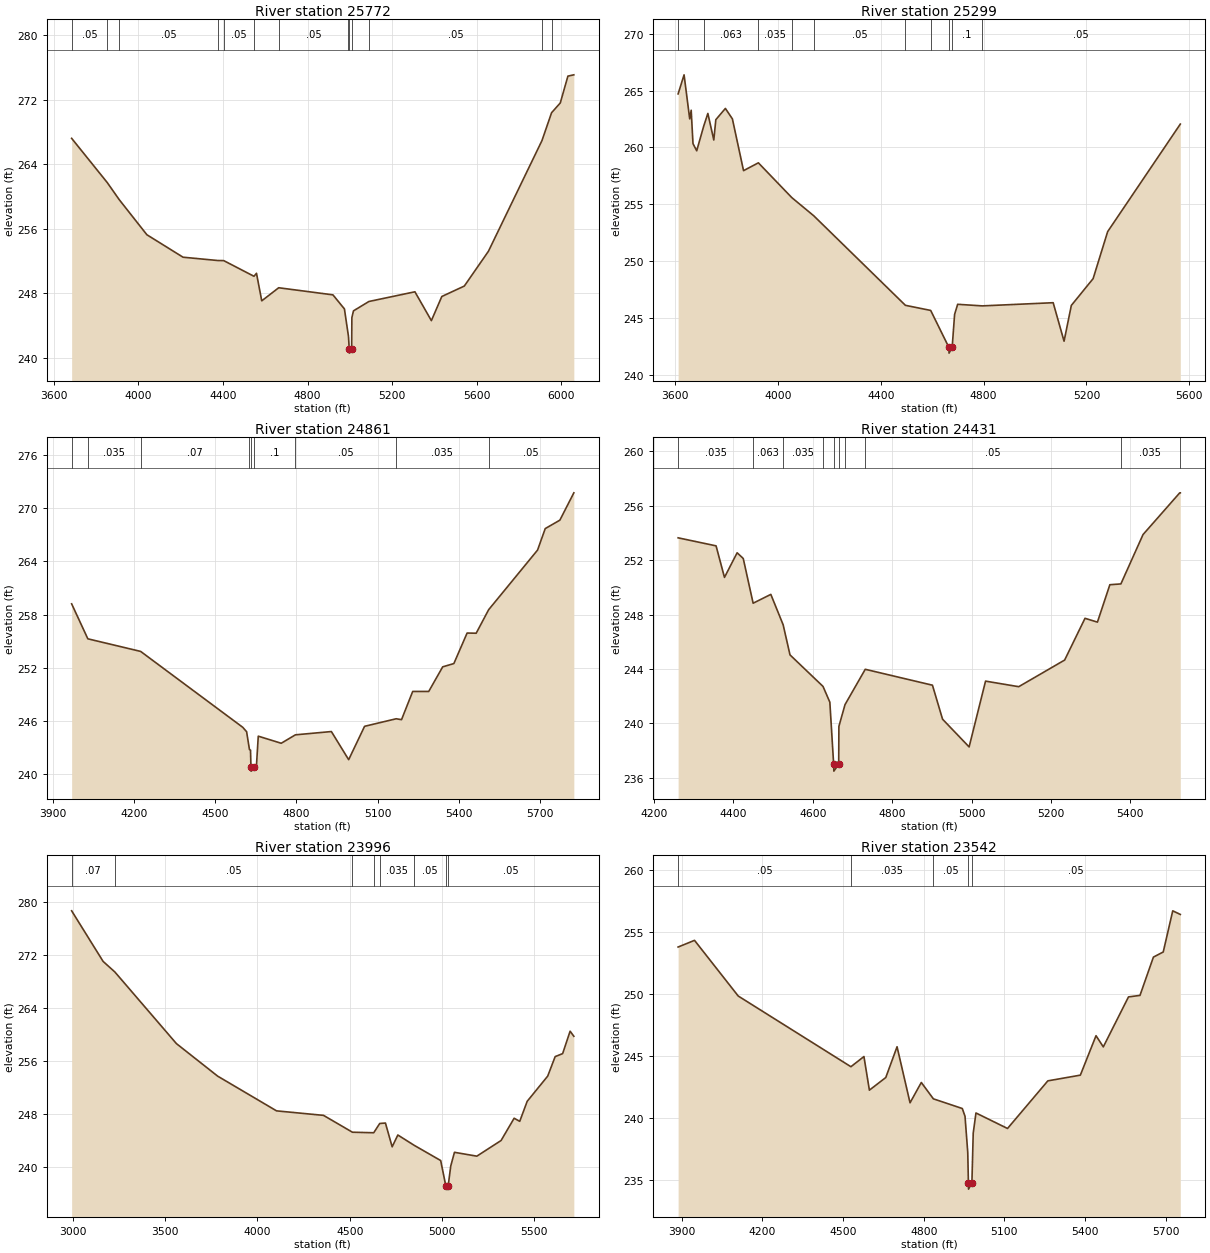
Type RM Length L Ch R = 1 ,25772   ,473,473,473
BEGIN DESCRIPTION:
BIRDS CREEK 37.0
END DESCRIPTION:
XS GIS Cut Line= 3
      2445647.58     13623035.01        2446875.       13622575.
        2447575.     13621775.01
#Sta/Elev= 30
  3684.8   267.2  3853.3  261.72  3909.5  259.62  4040.4  255.27  4211.3  252.49
  4375.6  252.08  4403.6  252.07  4546.7  250.13  4558.5   250.5  4583.4  247.09
  4663.5  248.71  4919.9  247.83  4974.2  246.09  4993.1  242.73  4997.2  241.12
  4997.7  240.62  5008.3  241.12  5009.4  245.01  5016.9  245.85    5090  247.01
  5307.4  248.21  5385.2  244.64  5434.6  247.63  5540.9  248.92  5654.8  253.22
  5907.9  266.92  5953.4  270.37  5994.5  271.58  6030.6   274.9  6058.6  275.06
#Mann= 13 ,-1 , 0
  3684.8     .05       0  3853.3    .035       0  3909.5     .05       0
  4375.6      .1       0  4403.6     .05       0  4546.7      .1       0
  4663.5     .05       0  4993.1      .1       0  4997.2     .05       0
  5008.3      .1       0    5090     .05       0  5907.9     .07       0
  5953.4     .05       0
Bank Sta=4997.2,5008.3
XS Rating Curve= 0 ,0
Exp/Cntr=0.3,0.1

Type RM Length L Ch R = 1 ,25299   ,438,438,438
BEGIN DESCRIPTION:
BIRDS CREEK 36.0
END DESCRIPTION:
XS GIS Cut Line= 3
        2446575.       13623775.        2447275.       13622575.
      2447674.98     13622175.02
#Sta/Elev= 30
  3610.7  264.72  3633.9   266.4  3655.8  262.52  3661.6  263.28  3668.6  260.34
  3683.1  259.71  3710.3  261.88  3726.5     263  3749.6  260.66  3757.5  262.45
  3794.7  263.44    3822  262.52  3865.4  257.96  3923.1  258.65  4053.1  255.59
  4138.5  253.99  4495.5   246.1  4593.9  245.65  4664.9  242.39  4665.4  241.89
  4677.5  242.39    4687   245.3  4698.9  246.19  4794.8  246.05  5070.7  246.33
  5113.1  242.94  5141.4  246.09  5226.2  248.45  5282.8  252.59  5565.6  262.06
#Mann= 10 ,-1 , 0
  3610.7    .035       0  3710.3    .063       0  3923.1    .035       0
  4053.1     .07       0  4138.5     .05       0  4495.5     .07       0
  4593.9      .1       0  4664.9     .05       0  4677.5      .1       0
  4794.8     .05       0
Bank Sta=4664.9,4677.5
XS Rating Curve= 0 ,0
Exp/Cntr=0.3,0.1

Type RM Length L Ch R = 1 ,24861   ,430,430,430
BEGIN DESCRIPTION:
BIRDS CREEK 35.0
END DESCRIPTION:
XS GIS Cut Line= 3
      2446925.03     13623574.97        2447575.       13622775.
      2447775.01     13621974.96
#Sta/Elev= 30
  3969.3  259.22  4029.1  255.28  4224.2  253.86  4601.4  245.31  4615.7  244.81
  4626.3  242.79  4630.1  242.74  4631.7  240.87  4632.2  240.37  4644.3  240.87
  4652.1  240.98  4658.8  244.31  4743.6  243.51    4796  244.46  4928.9  244.83
  4992.8  241.66  5051.6  245.42  5168.4  246.27  5188.1  246.17  5229.4  249.35
  5288.6  249.35  5340.2  252.12  5381.4  252.49  5430.4  255.93  5463.9  255.91
    5510  258.56  5690.7  265.28    5719   267.7  5773.1  268.65  5824.7  271.73
#Mann= 9 ,-1 , 0
  3969.3    .063       0  4029.1    .035       0  4224.2     .07       0
  4626.3      .1       0  4631.7     .05       0  4644.3      .1       0
    4796     .05       0  5168.4    .035       0    5510     .05       0
Bank Sta=4631.7,4644.3
XS Rating Curve= 0 ,0
Exp/Cntr=0.3,0.1

Type RM Length L Ch R = 1 ,24431   ,435,435,435
BEGIN DESCRIPTION:
BIRDS CREEK 34.0
END DESCRIPTION:
XS GIS Cut Line= 3
        2447675.     13623675.01        2447925.       13622975.
      2448074.99     13622475.03
#Sta/Elev= 30
  4260.8  253.64  4356.4  253.05  4377.6  250.73  4409.5  252.54  4424.9  252.12
  4449.8  248.83  4494.4  249.48  4525.5  247.24  4542.7  245.03  4625.9  242.71
  4643.1  241.55  4652.7  236.98  4653.2  236.48  4665.4  236.98  4665.9  239.77
  4681.3  241.37  4732.3  243.97  4901.6   242.8  4927.1   240.3    4994  238.26
  5035.4   243.1    5119  242.69  5234.7  244.65    5286  247.72  5317.3  247.44
  5348.6  250.19  5376.4  250.25  5432.2  253.88  5524.7  256.95  5526.1  256.95
#Mann= 10 ,-1 , 0
  4260.8    .035       0  4449.8    .063       0  4525.5    .035       0
  4625.9     .07       0  4652.7     .05       0  4665.4     .07       0
  4681.3      .1       0  4732.3     .05       0  5376.4    .035       0
  5524.7     .05       0
Bank Sta=4652.7,4665.4
XS Rating Curve= 0 ,0
Exp/Cntr=0.3,0.1

Type RM Length L Ch R = 1 ,23996   ,454,454,454
BEGIN DESCRIPTION:
BIRDS CREEK 33.0
END DESCRIPTION:
XS GIS Cut Line= 3
        2449175.     13624874.99        2448275.       13623075.
      2448174.99     13622374.96
#Sta/Elev= 30
  2993.9  278.62  3164.4  270.99  3227.6  269.41  3561.3   258.6  3784.9  253.69
  4103.5  248.46  4357.9  247.78  4514.5  245.24  4629.8  245.16  4662.4  246.56
  4693.3  246.62  4729.6  243.04  4760.4  244.82    4848  243.28  4992.4  240.97
  5020.1  237.16  5020.6  236.66  5033.1  237.16  5046.8  240.13    5067  242.21
  5188.2  241.63  5319.5  243.99  5390.2  247.35  5420.5  246.88  5460.9   249.9
    5572   253.7  5612.4  256.64  5652.8  257.09  5693.3  260.47  5713.5  259.71
#Mann= 8 ,-1 , 0
  2993.9     .07       0  3227.6     .05       0  4514.5    .035       0
  4629.8    .063       0  4662.4    .035       0    4848     .05       0
  5020.1     .05       0  5033.1     .05       0
Bank Sta=5020.1,5033.1
XS Rating Curve= 0 ,0
Exp/Cntr=0.3,0.1

Type RM Length L Ch R = 1 ,23542   ,427,427,427
BEGIN DESCRIPTION:
BIRDS CREEK 32.0
END DESCRIPTION:
XS GIS Cut Line= 3
        2448875.     13624125.01        2448675.       13623025.
      2448225.02     13622425.03
#Sta/Elev= 30
  3886.3  253.78  3947.3  254.32  4109.9  249.83  4529.1  244.13  4577.5  244.95
  4597.8  242.24  4658.8  243.26  4700.7  245.74    4749  241.22  4790.9  242.86
  4835.8  241.54  4943.4  240.76  4953.5  240.13  4963.7  237.22  4966.1  234.76
  4966.6  234.26  4979.1  234.76    4984  238.77  4994.2   240.4  5111.6  239.15
  5261.6  242.99  5382.5  243.45  5440.8  246.63  5467.9  245.73  5561.6  249.76
  5604.3  249.88  5654.3  252.97  5690.8  253.38  5726.2   256.7  5754.3  256.41
#Mann= 5 ,-1 , 0
  3886.3     .05       0  4529.1    .035       0  4835.8     .05       0
  4966.1     .05       0  4979.1     .05       0
Bank Sta=4966.1,4979.1
XS Rating Curve= 0 ,0
Exp/Cntr=0.3,0.1