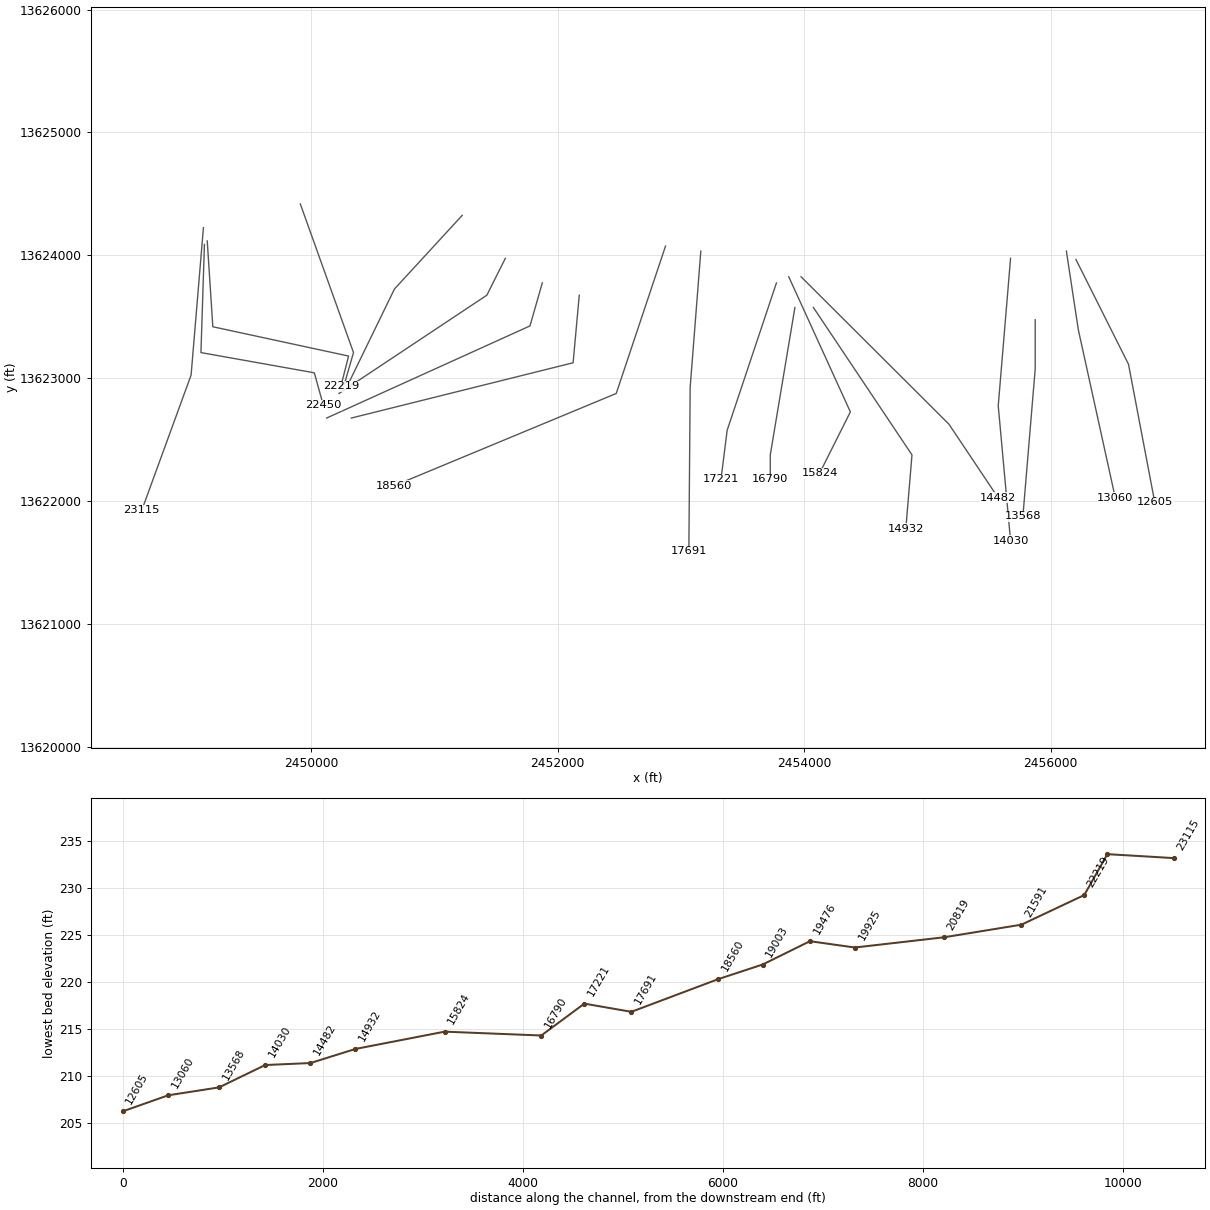
HEC-RAS study BIRDS CREEK.prj: BIRDS CREEK Base Level Engineering

--- BIRDS CREEK.g01 (geometry) --- (continued)

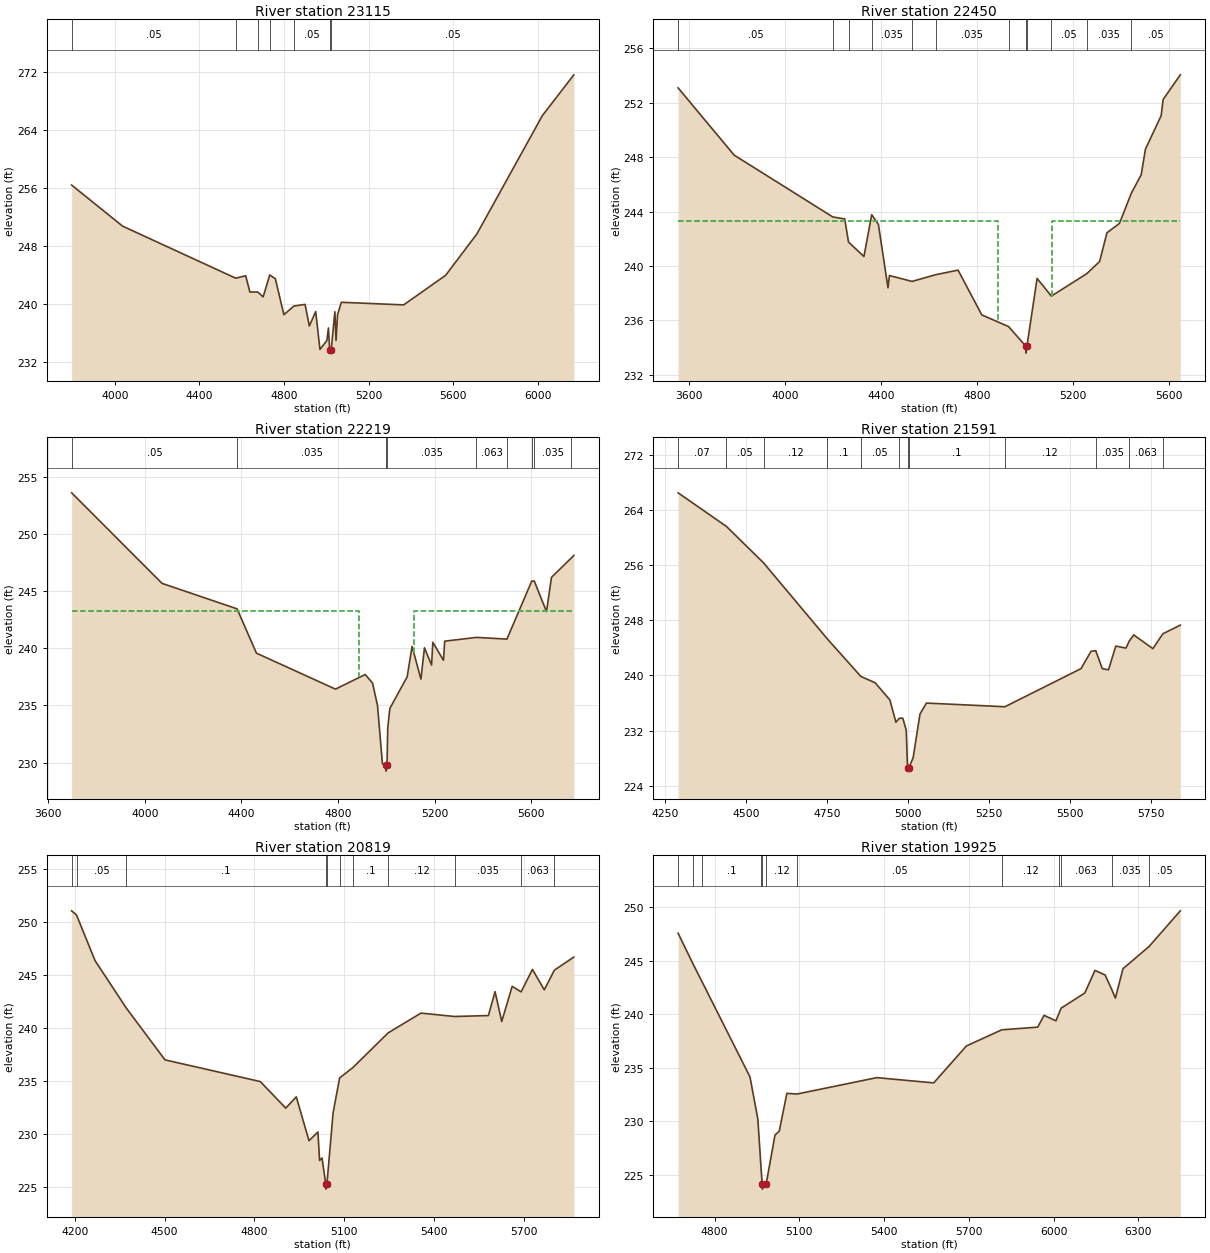
Type RM Length L Ch R = 1 ,23115   ,665,665,665
BEGIN DESCRIPTION:
BIRDS CREEK 31.0
END DESCRIPTION:
XS GIS Cut Line= 3
        2449125.     13624225.01        2449025.       13623025.
      2448625.01     13621925.04
#Sta/Elev= 30
  3796.2  256.35    4037  250.69    4572  243.51  4619.1  243.85  4639.1   241.6
  4675.9  241.61  4701.8  240.94  4732.9  243.96  4759.5  243.43  4799.7  238.48
  4847.1  239.67    4900   239.9  4920.1  236.92  4950.2  238.91  4970.3  233.69
    5003  234.91  5010.3  236.65  5015.7  233.91  5019.7  233.68  5019.9  233.18
  5023.7  233.68  5040.9  238.89  5046.3  234.93  5053.6   238.5  5071.5  240.19
  5366.1  239.83  5564.3   243.9  5712.6  249.62  6021.9  265.92  6170.8  271.55
#Mann= 7 ,-1 , 0
  3796.2     .05       0    4572    .035       0  4675.9    .063       0
  4732.9    .035       0  4847.1     .05       0  5019.7     .05       0
  5023.7     .05       0
Bank Sta=5019.7,5023.7
XS Rating Curve= 0 ,0
Exp/Cntr=0.3,0.1

Type RM Length L Ch R = 1 ,22450   ,231,231,231
BEGIN DESCRIPTION:
F21660
END DESCRIPTION:
XS GIS Cut Line= 4
      2449133.19     13624088.22      2449104.79     13623207.92
      2450024.89     13623043.21      2450098.21     13622778.15
#Sta/Elev= 30
  3555.8  253.09  3789.1  248.15  4199.4  243.61  4249.4  243.46  4265.1  241.76
  4329.4   240.7  4361.7  243.77  4389.5  243.06  4429.5   238.4  4435.5   239.3
  4529.6  238.87  4627.5  239.36  4721.2   239.7  4819.9  236.41  4931.4  235.55
  5003.7   234.1  5003.9   233.6  5007.7   234.1  5050.2  239.09  5109.5  237.79
  5256.4  239.43  5310.4  240.33  5340.9  242.44  5392.9  243.13  5442.4  245.35
  5483.6  246.71    5501  248.58  5566.6  251.05  5574.9  252.24  5646.3  254.05
#Mann= 12 ,-1 , 0
  3555.8     .05       0  4199.4    .035       0  4265.1    .063       0
  4361.7    .035       0  4529.6    .063       0  4627.5    .035       0
  4931.4    .063       0  5003.7    .063       0  5007.7    .063       0
  5109.5     .05       0  5256.4    .035       0  5442.4     .05       0
#XS Ineff= 2 , 0
       0  4886.7   243.3  5113.3       0   243.3
Permanent Ineff=
       F       F
Bank Sta=5003.7,5007.7
XS Rating Curve= 0 ,0
Exp/Cntr=0.3,0.1

Type RM Length L Ch R = 1 ,22219   ,628,628,628
BEGIN DESCRIPTION:
F21659
END DESCRIPTION:
XS GIS Cut Line= 4
      2449155.91     13624116.68      2449201.34     13623418.06
      2450303.19     13623179.52      2450240.71     13622935.25
#Sta/Elev= 30
  3696.7  253.62  4071.1  245.69  4381.8  243.46  4461.9  239.58  4789.3  236.43
  4912.4  237.71  4942.8  236.96  4963.3  234.99  4983.7   229.9  4998.6  229.75
  4998.8  229.25  5002.6  229.75  5005.7  233.03  5014.4  234.74  5086.1  237.51
  5106.5  240.17  5143.1  237.31  5157.7  240.05  5187.2  238.54  5192.3  240.53
  5236.4  238.96  5241.5  240.63  5373.1  240.96  5499.2  240.81    5602  245.89
  5612.3   245.9  5663.1  243.22  5683.7  246.22  5764.6  247.89  5776.3  248.14
#Mann= 9 ,-1 , 0
  3696.7     .05       0  4381.8    .035       0  4998.6    .035       0
  5002.6    .035       0  5373.1    .063       0  5499.2    .035       0
    5602    .063       0  5612.3    .035       0  5764.6     .05       0
#XS Ineff= 2 , 0
       0  4885.7   243.3  5114.3       0   243.3
Permanent Ineff=
       F       F
Bank Sta=4998.6,5002.6
XS Rating Curve= 0 ,0
Exp/Cntr=0.3,0.1

Type RM Length L Ch R = 1 ,21591   ,772,772,772
BEGIN DESCRIPTION:
F21658
END DESCRIPTION:
XS GIS Cut Line= 3
       2449911.3     13624417.67      2450342.95     13623207.92
      2450269.56     13622953.87
#Sta/Elev= 30
  4291.1  266.55  4440.3  261.66  4554.6  256.37    4751  245.34  4854.5  239.87
  4899.1  238.93  4944.4  236.44  4962.8  233.21  4973.6  233.79  4984.1  233.79
  4994.7  232.05  4998.7   226.6  4998.9   226.1  5002.7   226.6  5015.9  228.03
  5037.2  234.41    5057  235.99  5299.2  235.46  5533.9     241  5564.8  243.53
  5579.3   243.6  5599.4  240.99  5618.6  240.83    5641  244.28  5672.3  243.98
  5682.7  245.01  5696.3   245.9  5755.5   243.9  5786.1  246.06    5840  247.32
#Mann= 12 ,-1 , 0
  4291.1     .07       0  4440.3     .05       0  4554.6     .12       0
    4751      .1       0  4854.5     .05       0  4973.6      .1       0
  4998.7     .05       0  5002.7      .1       0  5299.2     .12       0
  5579.3    .035       0  5682.7    .063       0  5786.1    .035       0
Bank Sta=4998.7,5002.7
XS Rating Curve= 0 ,0
Exp/Cntr=0.3,0.1

Type RM Length L Ch R = 1 ,20819   ,894,894,894
BEGIN DESCRIPTION:
BIRDS CREEK 27.0
END DESCRIPTION:
XS GIS Cut Line= 3
      2451225.03     13624325.03        2450675.       13623725.
      2450298.32     13622948.31
#Sta/Elev= 30
  4189.8  251.07  4206.2  250.67  4267.8  246.37    4372  241.89  4501.5  236.98
  4819.7  234.93  4904.8  232.42    4940  233.48  4982.5  229.34  5012.3  230.16
  5017.9  227.47    5026   227.7  5038.4  225.26  5038.7  224.76  5042.4  225.26
    5063  231.98  5084.8  235.28  5127.9  236.22  5246.8  239.53  5356.4   241.4
  5468.9  241.08  5581.7  241.17  5603.9  243.43  5626.2  240.61    5661  243.93
  5690.9  243.41  5728.7  245.53  5768.3   243.6    5802  245.46    5867   246.7
#Mann= 11 ,-1 , 0
  4189.8     .07       0  4206.2     .05       0    4372      .1       0
  5038.4     .05       0  5042.4      .1       0  5084.8     .05       0
  5127.9      .1       0  5246.8     .12       0  5468.9    .035       0
  5690.9    .063       0    5802    .035       0
Bank Sta=5038.4,5042.4
XS Rating Curve= 0 ,0
Exp/Cntr=0.3,0.1

Type RM Length L Ch R = 1 ,19925   ,449,449,449
BEGIN DESCRIPTION:
BIRDS CREEK 26.0
END DESCRIPTION:
XS GIS Cut Line= 3
      2451575.01     13623975.02        2451425.       13623675.
      2450224.96     13622874.98
#Sta/Elev= 30
  4670.7  247.59  4722.7  244.76  4754.9  243.08  4925.1  234.16    4953  230.21
    4963  226.14  4968.2  224.17  4968.7  223.67  4982.5  224.17  5013.6  228.72
  5028.7  229.09  5055.7  232.62  5092.1  232.56  5374.2  234.09  5575.5   233.6
  5691.2  237.05  5816.5  238.56  5943.6  238.81  5966.1  239.91  6008.2   239.4
  6019.9  240.16  6026.4  240.58  6110.3     242  6146.4  244.11  6182.4  243.68
  6205.5  242.34  6218.5  241.52  6245.5  244.27    6338  246.35  6448.4  249.68
#Mann= 12 ,-1 , 0
  4670.7     .07       0  4722.7     .12       0  4754.9      .1       0
    4963     .12       0  4968.2     .05       0  4982.5     .12       0
  5092.1     .05       0  5816.5     .12       0  6019.9    .035       0
  6026.4    .063       0  6205.5    .035       0    6338     .05       0
Bank Sta=4968.2,4982.5
XS Rating Curve= 0 ,0
Exp/Cntr=0.3,0.1

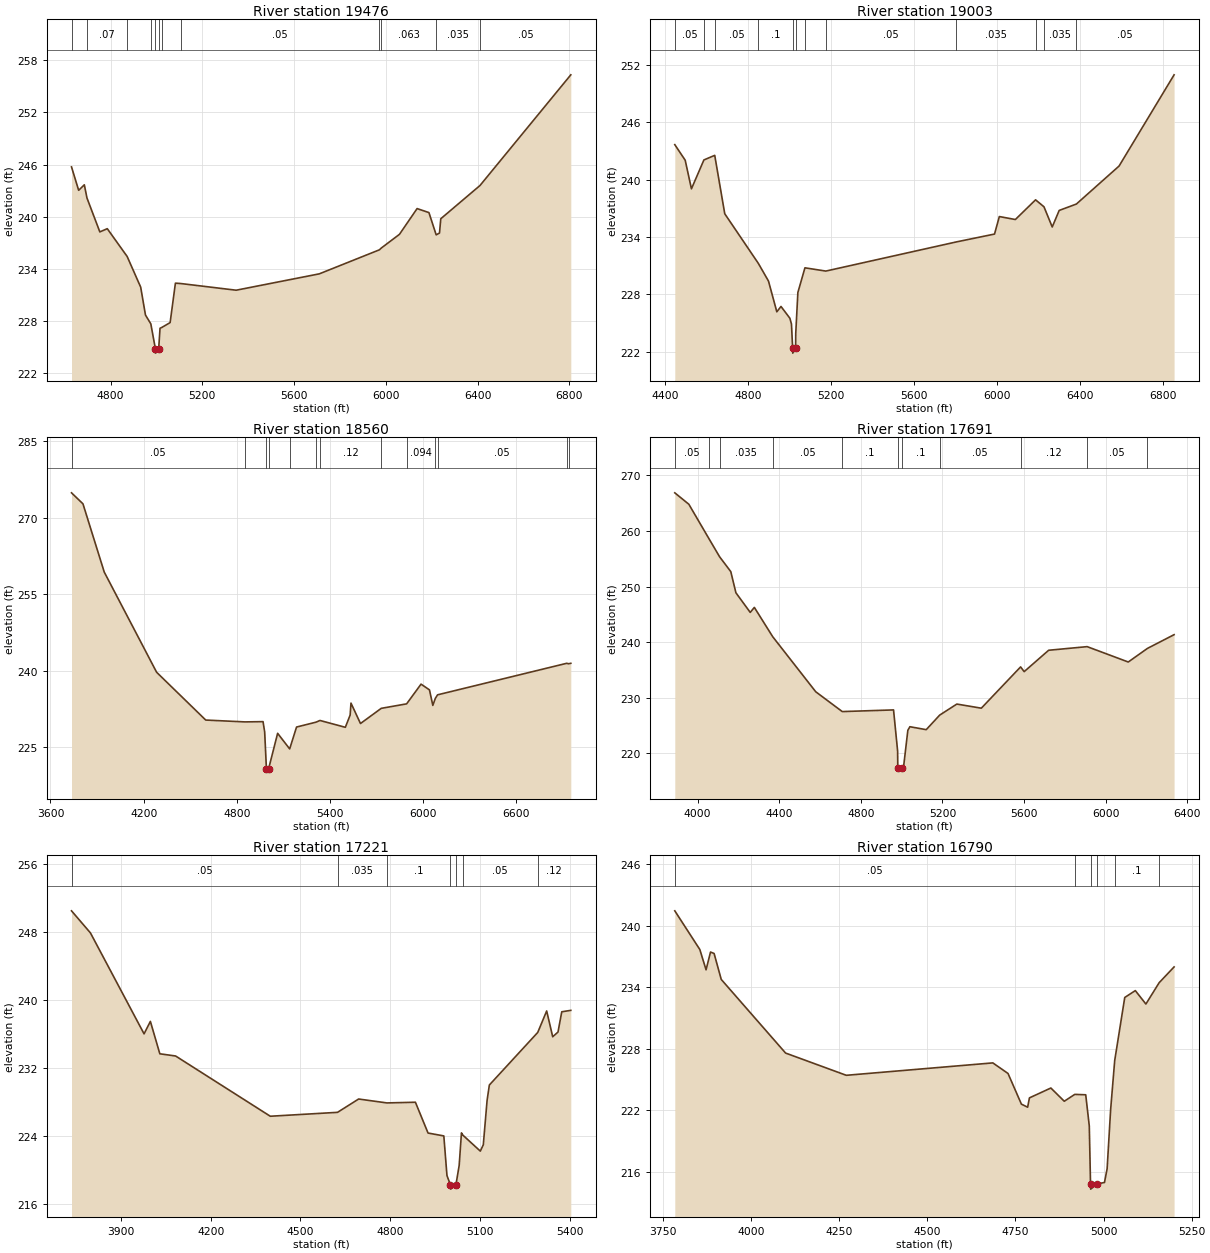
Type RM Length L Ch R = 1 ,19476   ,473,473,473
BEGIN DESCRIPTION:
BIRDS CREEK 25.0
END DESCRIPTION:
XS GIS Cut Line= 3
      2451874.99     13623774.96        2451775.       13623425.
      2450125.02     13622675.01
#Sta/Elev= 30
    4630  245.74  4661.2  243.05  4685.9  243.68  4697.4  242.17  4753.5  238.27
    4786  238.64  4872.5  235.45  4931.6  231.92  4952.4  228.72  4975.8   227.7
  4995.6  224.84  4996.1  224.34    5010  224.84  5015.9   227.2  5023.6  227.29
  5059.9  227.85  5082.9  232.38  5105.1  232.34  5347.7  231.57  5710.2  233.45
    5972  236.21  5980.6  236.42  6059.5  237.99  6136.4  240.95    6188  240.49
  6219.6  237.93  6234.1  238.14  6239.6  239.78  6410.5   243.6  6806.4  256.32
#Mann= 12 ,-1 , 0
    4630     .05       0  4697.4     .07       0  4872.5     .12       0
  4975.8      .1       0  4995.6     .05       0    5010      .1       0
  5023.6     .12       0  5105.1     .05       0    5972    .035       0
  5980.6    .063       0  6219.6    .035       0  6410.5     .05       0
Bank Sta=4995.6,5010
XS Rating Curve= 0 ,0
Exp/Cntr=0.3,0.1

Type RM Length L Ch R = 1 ,19003   ,443,443,443
BEGIN DESCRIPTION:
BIRDS CREEK 24.0
END DESCRIPTION:
XS GIS Cut Line= 3
        2452175.     13623675.01        2452125.       13623125.
      2450324.98     13622674.99
#Sta/Elev= 30
  4447.7  243.66  4497.9  242.03    4528  239.04  4588.1  242.06  4640.3  242.54
  4688.7  236.43  4850.4  231.25  4899.6  229.39  4939.7  226.18  4959.8  226.74
  5002.6  225.51  5010.3   224.9    5016  222.36  5016.5  221.86  5030.4  222.36
  5030.9   223.9  5041.2   228.2  5075.3  230.78    5176  230.44  5805.8  233.49
  5989.5  234.31  6012.7  236.14    6090  235.83  6187.4  237.89    6228  237.16
  6267.8  235.05  6301.3  236.78  6384.3  237.45    6590  241.42  6855.4  250.96
#Mann= 12 ,-1 , 0
  4447.7     .05       0  4588.1     .07       0  4640.3     .05       0
  4850.4      .1       0    5016     .05       0  5030.4      .1       0
  5075.3     .12       0    5176     .05       0  5805.8    .035       0
  6187.4    .063       0    6228    .035       0  6384.3     .05       0
Bank Sta=5016,5030.4
XS Rating Curve= 0 ,0
Exp/Cntr=0.3,0.1

Type RM Length L Ch R = 1 ,18560   ,869,869,869
BEGIN DESCRIPTION:
BIRDS CREEK 23.0
END DESCRIPTION:
XS GIS Cut Line= 3
      2452874.99     13624074.97        2452475.       13622875.
      2450674.98     13622124.99
#Sta/Elev= 30
  3735.4  274.92  3809.2  272.76  3946.2  259.37  4283.5  239.71  4599.7  230.33
  4851.8  229.97  4968.7  230.02  4979.2     228  4990.4  220.81  4990.9  220.31
  5004.9  220.81  5062.6  227.73  5140.1  224.67  5184.4  228.96    5309  229.91
  5335.4  230.25  5498.6  228.91  5529.5  231.31  5534.9  233.66  5596.1  229.65
  5729.8  232.63  5893.1  233.51  5986.1  237.38  6040.3  236.25  6061.9  233.21
  6078.1  234.59  6092.3  235.28    6924  241.47    6936  241.38  6950.3  241.47
#Mann= 13 ,-1 , 0
  3735.4     .05       0  4851.8      .1       0  4990.4     .05       0
  5004.9      .1       0  5140.1     .12       0    5309     .05       0
  5335.4     .12       0  5729.8    .063       0  5893.1    .094       0
  6078.1    .063       0  6092.3     .05       0    6924     .07       0
    6936     .05       0
Bank Sta=4990.4,5004.9
XS Rating Curve= 0 ,0
Exp/Cntr=0.3,0.1

Type RM Length L Ch R = 1 ,17691   ,470,470,470
BEGIN DESCRIPTION:
BIRDS CREEK 22.0
END DESCRIPTION:
XS GIS Cut Line= 3
      2453161.29     13624033.62        2453075.       13622925.
      2453064.34     13621590.41
#Sta/Elev= 30
  3888.7  266.84  3957.5  264.79  4056.3  258.59  4108.4  255.34  4163.1  252.68
  4188.2  248.88  4258.4  245.35  4278.5  246.25  4368.8  240.97  4579.4  231.09
  4709.3  227.53  4960.6  227.83  4980.6  220.43  4981.4  217.33  4981.9  216.83
  4999.8  217.33  5010.7   217.9  5030.7  224.17  5040.7  224.81  5120.7  224.28
  5186.8   226.9  5270.7  228.88  5390.7  228.14  5583.2  235.56  5600.7  234.71
  5720.7  238.55  5909.3   239.2  6110.7  236.44  6204.6  238.88  6335.3  241.35
#Mann= 11 ,-1 , 0
  3888.7     .05       0  4056.3     .07       0  4108.4    .035       0
  4368.8     .05       0  4709.3      .1       0  4981.4     .05       0
  4999.8      .1       0  5186.8     .05       0  5583.2     .12       0
  5909.3     .05       0  6204.6    .035       0
Bank Sta=4981.4,4999.8
XS Rating Curve= 0 ,0
Exp/Cntr=0.3,0.1

Type RM Length L Ch R = 1 ,17221   ,431,431,431
BEGIN DESCRIPTION:
BIRDS CREEK 21.0
END DESCRIPTION:
XS GIS Cut Line= 3
      2453774.99     13623774.98        2453375.       13622575.
        2453325.       13622175.
#Sta/Elev= 30
  3735.1   250.5  3798.3   247.9  3977.5     236  3998.6  237.47  4030.2  233.65
  4082.9  233.39  4399.2  226.29  4623.8  226.75  4694.3  228.32  4788.6  227.86
    4884  227.94  4926.2  224.31  4978.9  223.97  4989.4   219.3  5000.9   218.2
  5001.4   217.7  5019.3   218.2  5030.2   220.5  5037.8  224.33  5042.3  224.07
  5100.8  222.18  5110.8  222.93  5123.4  228.15    5131  229.97  5292.7  236.17
  5322.5   238.7  5342.6  235.66  5360.3  236.21  5372.9   238.6  5403.1  238.77
#Mann= 7 ,-1 , 0
  3735.1     .05       0  4623.8    .035       0  4788.6      .1       0
  5000.9     .05       0  5019.3      .1       0  5042.3     .05       0
  5292.7     .12       0
Bank Sta=5000.9,5019.3
XS Rating Curve= 0 ,0
Exp/Cntr=0.3,0.1

Type RM Length L Ch R = 1 ,16790   ,966,966,966
BEGIN DESCRIPTION:
BIRDS CREEK 20.0
END DESCRIPTION:
XS GIS Cut Line= 3
        2453925.     13623575.01        2453725.       13622375.
        2453725.     13622174.96
#Sta/Elev= 30
  3783.4  241.45  3854.4  237.68  3872.1   235.7  3884.8  237.43  3894.9  237.29
  3915.2  234.76  4097.7  227.58    4270  225.41  4685.7  226.62  4728.8  225.59
  4766.8   222.6  4784.5   222.3  4789.6  223.21  4850.4  224.17  4888.4  222.88
  4918.3  223.55  4949.3  223.51  4959.4  220.47  4962.9  214.81  4963.4  214.31
  4981.3  214.81  5002.5  214.96    5010   216.3    5020  222.08  5031.5  226.85
    5060     233    5090  233.67    5120  232.36  5157.6  234.44    5200  235.98
#Mann= 6 ,-1 , 0
  3783.4     .05       0  4918.3    .035       0  4962.9    .035       0
  4981.3    .035       0  5031.5      .1       0  5157.6     .05       0
Bank Sta=4962.9,4981.3
XS Rating Curve= 0 ,0
Exp/Cntr=0.3,0.1

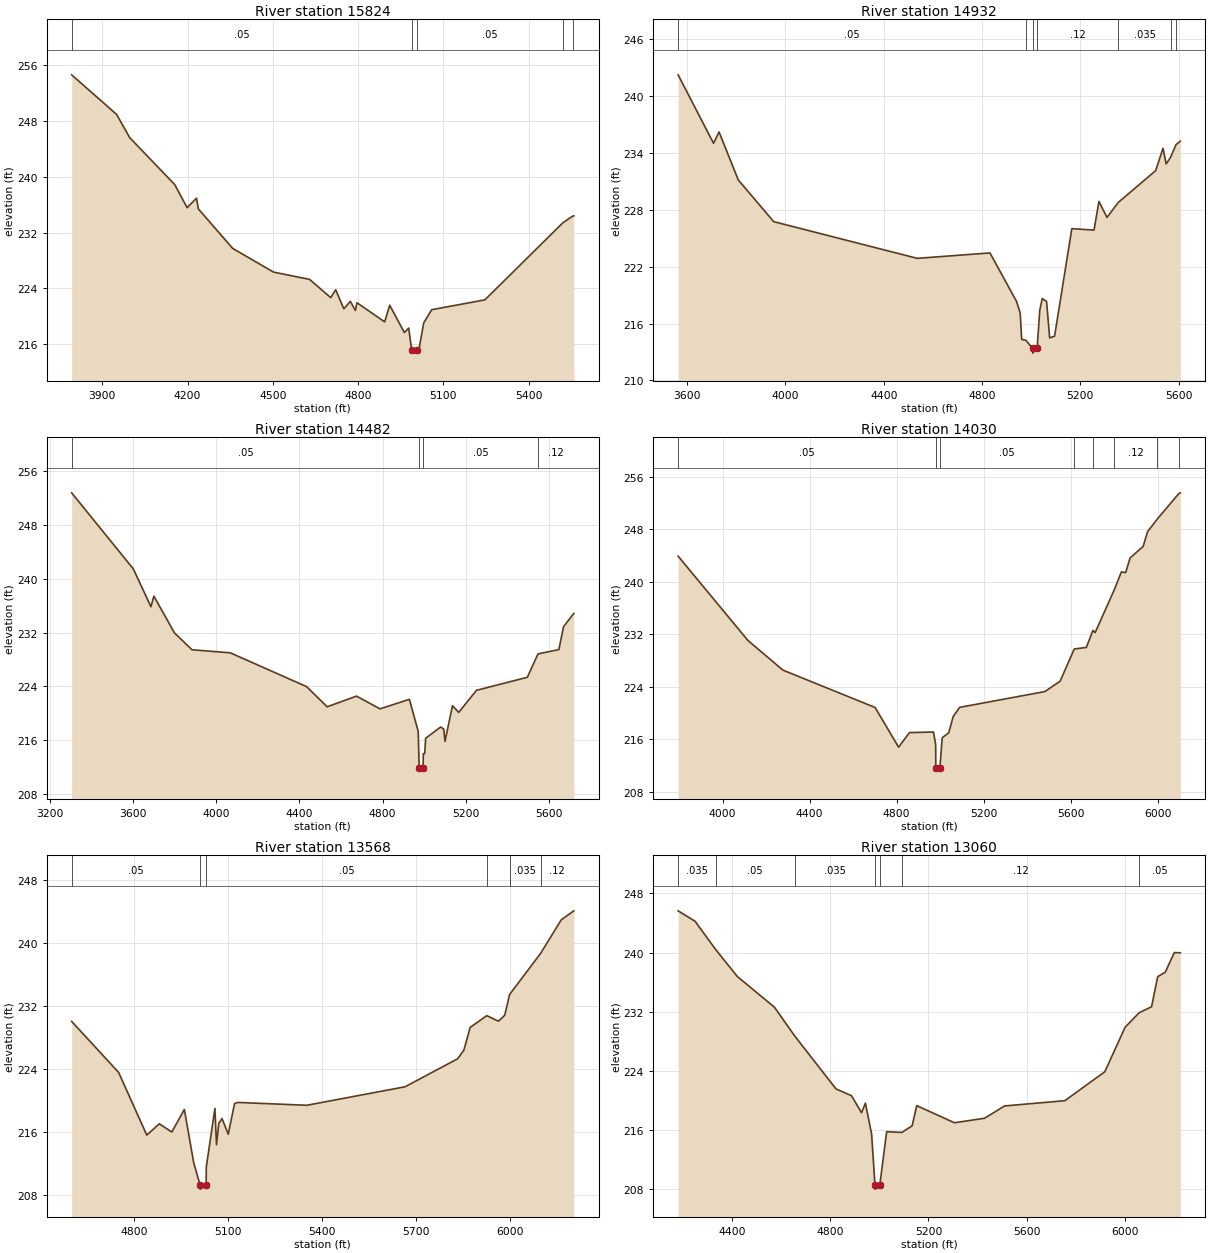
Type RM Length L Ch R = 1 ,15824   ,892,892,892
BEGIN DESCRIPTION:
BIRDS CREEK 19.0
END DESCRIPTION:
XS GIS Cut Line= 3
      2453875.01     13623824.98        2454375.       13622725.
        2454125.       13622225.
#Sta/Elev= 30
  3792.2  254.64  3950.4  248.96  3996.5  245.63  4154.7  238.91  4198.6  235.58
  4231.6  236.95  4238.1  235.41    4359  229.74  4502.9  226.34  4629.2   225.3
  4703.9  222.68  4721.5  223.81    4750  221.08  4773.1  222.15  4790.7  220.84
  4796.2  221.95  4893.9   219.2  4911.5  221.59  4963.1  217.67  4978.5  218.31
  4988.5  215.22    4989  214.72    5007  215.22  5014.5  215.29  5031.2  219.05
  5059.2  220.95  5246.4  222.36    5521  233.42  5555.2  234.37  5559.5  234.41
#Mann= 5 ,-1 , 0
  3792.2     .05       0  4988.5     .05       0    5007     .05       0
    5521    .035       0  5555.2     .05       0
Bank Sta=4988.5,5007
XS Rating Curve= 0 ,0
Exp/Cntr=0.3,0.1

Type RM Length L Ch R = 1 ,14932   ,450,450,450
BEGIN DESCRIPTION:
BIRDS CREEK 18.0
END DESCRIPTION:
XS GIS Cut Line= 3
      2454075.01     13623574.99        2454875.       13622375.
        2454825.     13621774.99
#Sta/Elev= 30
    3563  242.24  3707.2  235.02  3729.7  236.21  3807.9  231.15  3952.1  226.75
  4536.5  222.88  4832.4  223.45  4940.6  218.34  4955.6   217.1  4961.6  214.33
  4979.1  214.23    5006  213.38  5006.5  212.88  5024.5  213.38  5035.3  217.42
  5045.3  218.64  5062.9  218.33  5075.5  214.49  5095.5  214.67  5165.8  226.01
  5256.1  225.86  5276.1  228.88  5308.8   227.2  5355.3  228.79  5506.9  232.13
    5537  234.49  5549.6  232.84  5567.9  233.54  5589.9  234.88  5607.3  235.24
#Mann= 7 ,-1 , 0
    3563     .05       0  4979.1     .12       0    5006     .05       0
  5024.5     .12       0  5355.3    .035       0  5567.9     .12       0
  5589.9    .035       0
Bank Sta=5006,5024.5
XS Rating Curve= 0 ,0
Exp/Cntr=0.3,0.1

Type RM Length L Ch R = 1 ,14482   ,452,452,452
BEGIN DESCRIPTION:
BIRDS CREEK 17.0
END DESCRIPTION:
XS GIS Cut Line= 3
        2453975.       13623825.        2455175.       13622625.
      2455575.02     13622024.97
#Sta/Elev= 30
  3302.9  252.78  3599.9  241.46  3684.7  235.84  3698.9  237.41  3797.9  231.95
  3882.7  229.43  4066.6  228.98  4434.3  223.95  4533.3  220.95  4674.7  222.54
  4787.8  220.64  4929.2  222.06  4971.7   217.3  4976.5  211.88    4977  211.38
  4995.1  211.88  4996.4  213.98    5003  213.98  5007.5  216.27  5079.6  217.94
  5094.6  217.64  5100.6   215.8  5136.7  221.12  5166.7  220.12  5252.3   223.4
  5497.2  225.34  5548.6  228.82    5649  229.46  5671.5  232.87  5721.1  234.85
#Mann= 4 ,-1 , 0
  3302.9     .05       0  4976.5     .05       0  4995.1     .05       0
  5548.6     .12       0
Bank Sta=4976.5,4995.1
XS Rating Curve= 0 ,0
Exp/Cntr=0.3,0.1

Type RM Length L Ch R = 1 ,14030   ,462,462,462
BEGIN DESCRIPTION:
BIRDS CREEK 16.0
END DESCRIPTION:
XS GIS Cut Line= 3
        2455675.     13623975.01        2455575.       13622775.
        2455675.     13621675.01
#Sta/Elev= 30
  3795.4   243.9  4116.5  231.06  4277.1  226.55    4701  220.86  4808.9  214.82
  4859.1  217.04  4969.5  217.12  4979.5   215.2  4980.1  211.67  4980.6  211.17
  4998.9  211.67  5009.6  216.25  5039.7  217.01  5059.8  219.47  5089.9  220.88
  5481.5  223.28  5551.8  224.87  5616.4  229.76  5672.3  230.01  5702.4   232.6
  5712.5  232.26  5801.1  238.81    5833  241.49  5853.1  241.41  5873.2  243.63
  5933.4  245.39  5953.5  247.62  5998.4  249.55  6097.1  253.42  6104.1  253.54
#Mann= 8 ,-1 , 0
  3795.4     .05       0  4980.1     .05       0  4998.9     .05       0
  5616.4     .12       0  5702.4    .035       0  5801.1     .12       0
  5998.4    .094       0  6097.1    .063       0
Bank Sta=4980.1,4998.9
XS Rating Curve= 0 ,0
Exp/Cntr=0.3,0.1

Type RM Length L Ch R = 1 ,13568   ,508,508,508
BEGIN DESCRIPTION:
BIRDS CREEK 15.0
END DESCRIPTION:
XS GIS Cut Line= 3
        2455875.       13623475.        2455875.       13623075.
        2455775.     13621874.96
#Sta/Elev= 30
    4600  230.05    4750  223.59    4840  215.64    4880  217.07    4920  216.03
    4960  218.89    4990  212.13  5010.4  209.29  5010.9  208.79  5029.7  209.29
  5030.1  211.59  5057.7  219.03  5062.7  214.43  5070.2  217.15  5080.3  217.74
  5100.3  215.76  5120.4  219.64  5130.5  219.78  5351.2  219.42  5664.8  221.76
  5832.9  225.31  5852.9  226.41    5873  229.29  5926.1  230.78  5963.3  230.08
  5983.4  230.83    5999  233.46  6098.1  238.68    6164  242.93  6204.2  244.07
#Mann= 6 ,-1 , 0
    4600     .05       0  5010.4     .05       0  5029.7     .05       0
  5926.1     .12       0    5999    .035       0  6098.1     .12       0
Bank Sta=5010.4,5029.7
XS Rating Curve= 0 ,0
Exp/Cntr=0.3,0.1

Type RM Length L Ch R = 1 ,13060   ,455,455,455
BEGIN DESCRIPTION:
BIRDS CREEK 14.0
END DESCRIPTION:
XS GIS Cut Line= 3
        2456128.     13624033.58      2456224.95     13623393.73
        2456525.     13622024.98
#Sta/Elev= 30
  4178.9  245.65  4248.3  244.23  4331.6  240.43  4420.2  236.76  4571.9  232.59
  4654.4   228.7  4822.9  221.53  4886.2   220.6  4927.1   218.3  4942.8   219.6
  4968.1  215.42    4982  208.45  4982.5  207.95  5001.4  208.45  5029.5  215.73
  5091.2  215.63  5133.4  216.52  5152.3  219.26  5305.9  216.94  5428.8  217.55
  5510.7  219.22  5756.4  219.93  5919.4  223.85  6002.1  229.87  6059.6  231.85
    6110  232.65  6135.1  236.73  6165.9  237.33  6202.8  239.99  6227.3  239.97
#Mann= 7 ,-1 , 0
  4178.9    .035       0  4331.6     .05       0  4654.4    .035       0
    4982    .035       0  5001.4    .035       0  5091.2     .12       0
  6059.6     .05       0
Bank Sta=4982,5001.4
XS Rating Curve= 0 ,0
Exp/Cntr=0.3,0.1

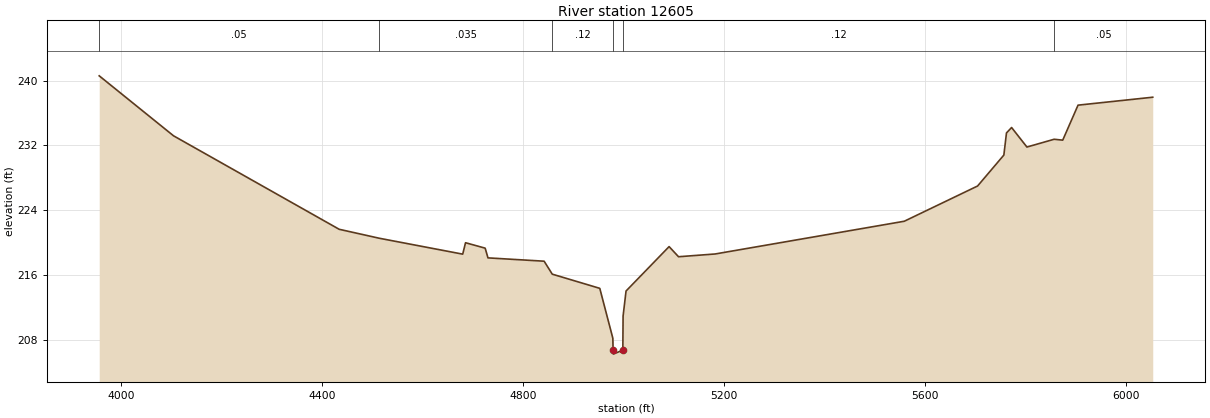
Type RM Length L Ch R = 1 ,12605   ,398,398,398
BEGIN DESCRIPTION:
BIRDS CREEK 13.0
END DESCRIPTION:
XS GIS Cut Line= 3
      2456205.58     13623965.71      2456632.14     13623112.57
      2456845.25     13621988.93
#Sta/Elev= 30
  3956.7  240.59  4104.6  233.19  4434.4  221.65  4514.5  220.54  4680.4  218.58
    4686  219.99  4725.1  219.32  4730.7  218.12  4842.5  217.71  4858.7  216.11
  4953.3  214.36  4979.3   208.2  4979.8  206.74  4980.3  206.24  4999.2  206.74
  4999.7  210.94  5005.6  214.03  5091.3  219.51  5110.1  218.26  5182.9   218.6
  5559.5  222.64  5705.5  226.99  5757.8  230.81    5763  233.54  5773.2  234.21
  5803.7   231.8  5857.9  232.76    5875  232.65  5905.5  236.97  6054.2  237.95
#Mann= 6 ,-1 , 0
  3956.7     .05       0  4514.5    .035       0  4858.7     .12       0
  4979.8     .05       0  4999.2     .12       0  5857.9     .05       0
Bank Sta=4979.8,4999.2
XS Rating Curve= 0 ,0
Exp/Cntr=0.3,0.1