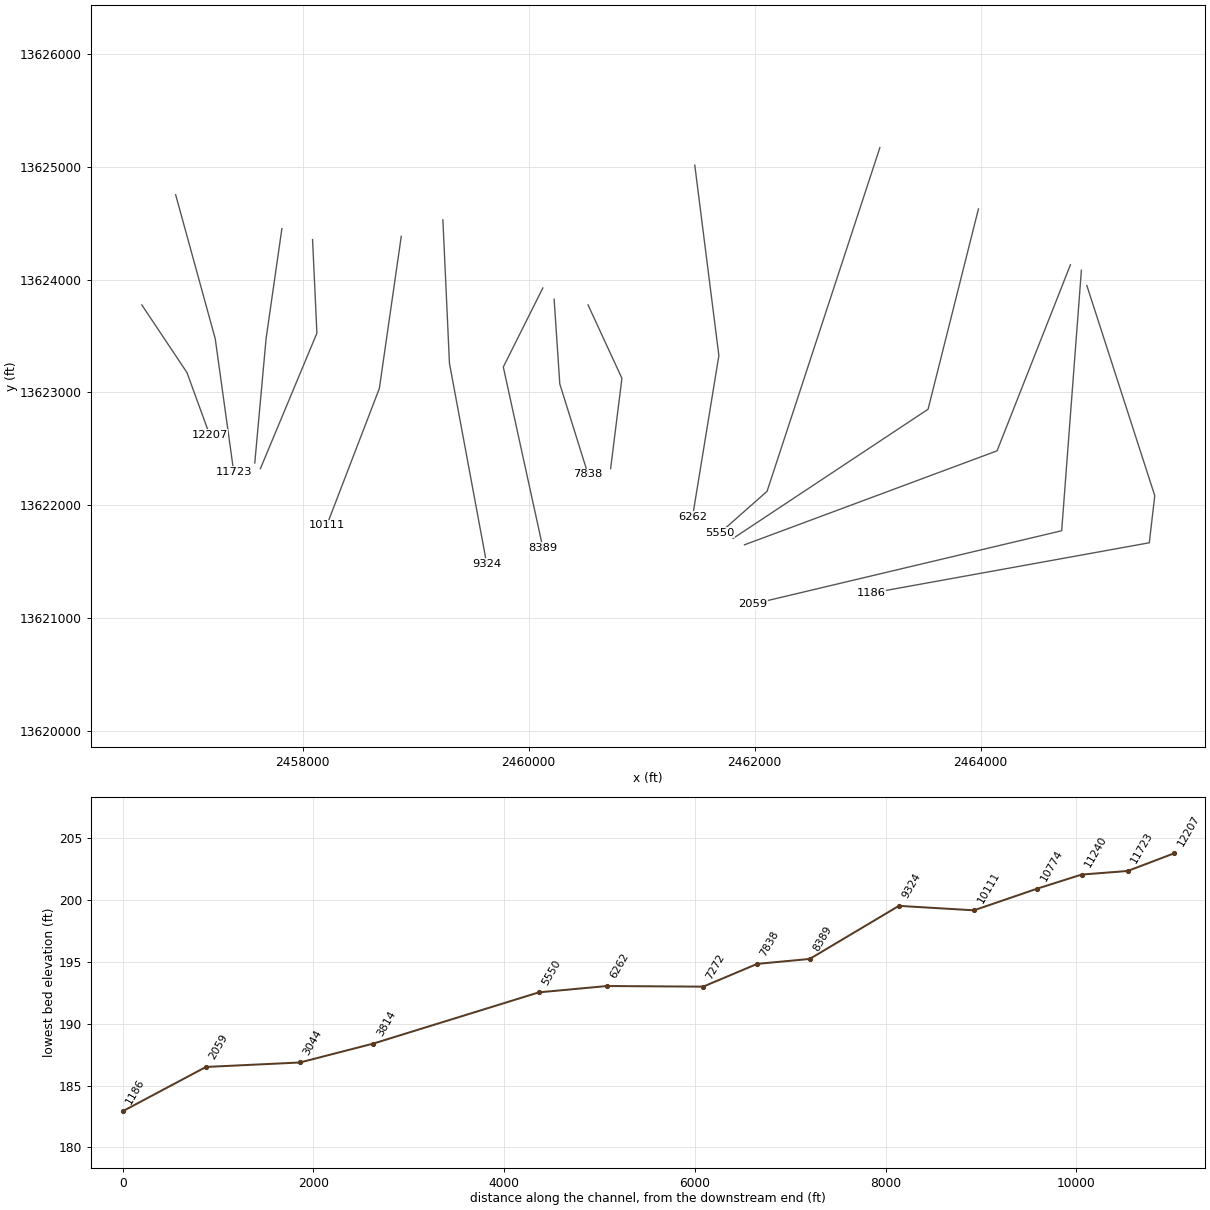
HEC-RAS study BIRDS CREEK.prj: BIRDS CREEK Base Level Engineering

--- BIRDS CREEK.g01 (geometry) --- (continued)

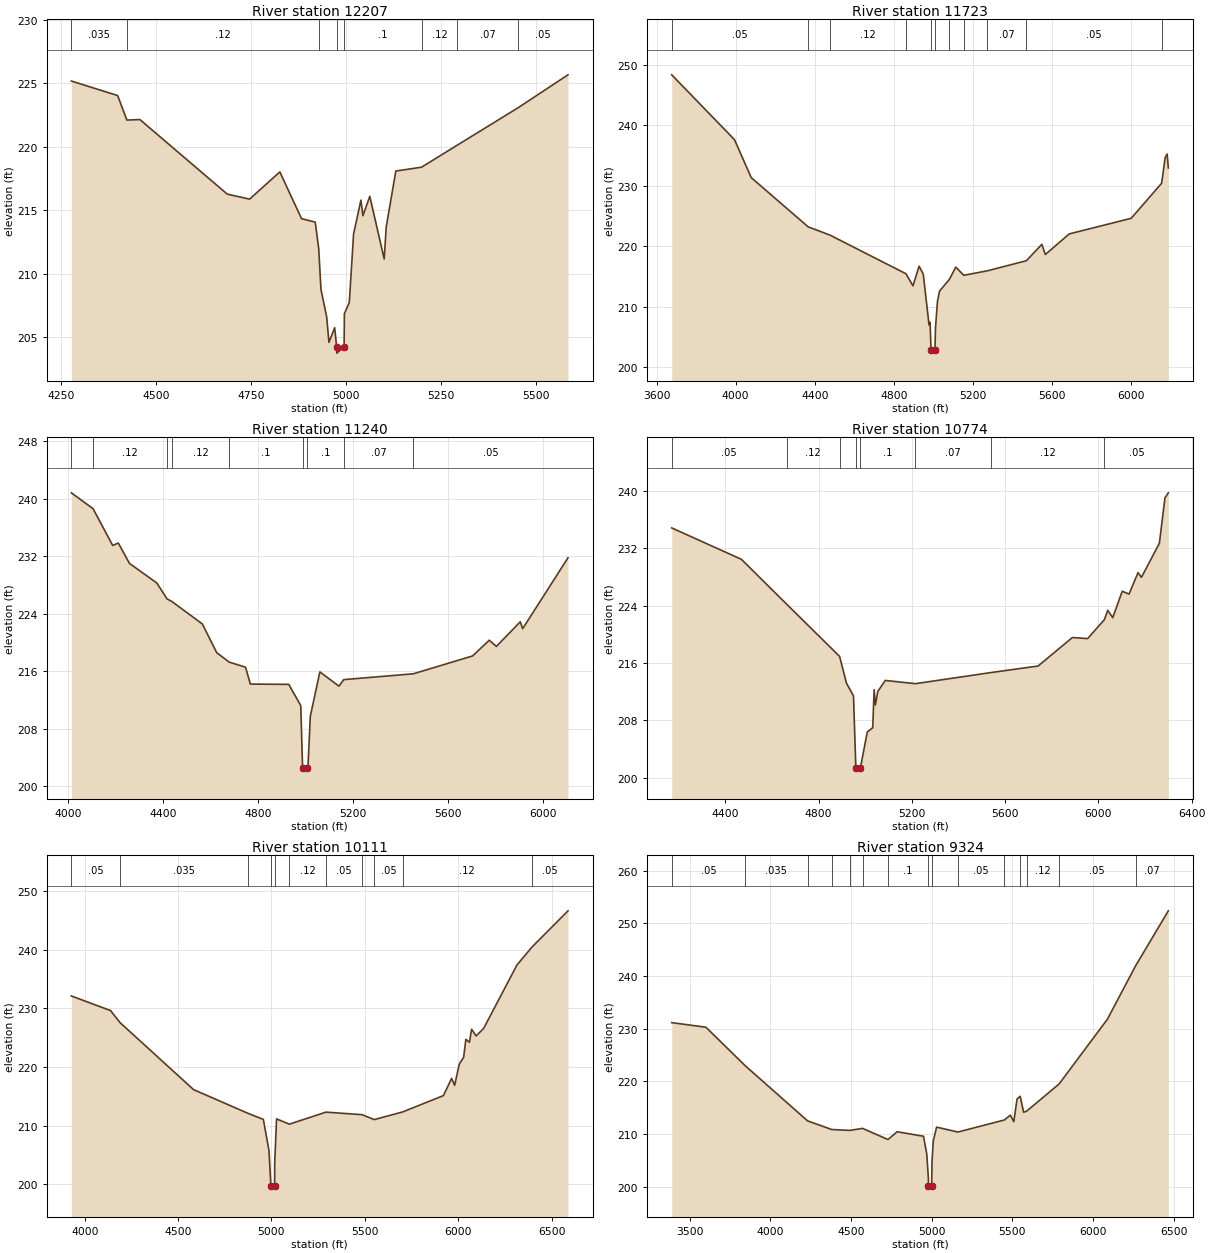
Type RM Length L Ch R = 1 ,12207   ,484,484,484
BEGIN DESCRIPTION:
BIRDS CREEK 12.0
END DESCRIPTION:
XS GIS Cut Line= 3
      2456574.97     13623775.04        2456975.       13623175.
        2457175.     13622624.99
#Sta/Elev= 30
  4277.1  225.18  4398.8  224.04  4423.2  222.11  4457.4  222.15  4687.3  216.28
  4745.9  215.89  4825.5  218.03  4882.6  214.35  4918.6  214.08  4927.8  211.98
  4933.7  208.77  4948.7  206.63  4954.7  204.62  4969.7  205.77  4974.9  204.27
  4975.4  203.77  4994.5  204.27  4995.3  206.87  5008.2  207.76  5019.5  213.15
  5038.8  215.81  5044.1  214.58  5062.1  216.11    5100  211.18  5105.3  213.69
  5130.6   218.1  5198.2   218.4  5292.5  220.14  5452.8  223.09  5583.5  225.67
#Mann= 8 ,-1 , 0
  4277.1    .035       0  4423.2     .12       0  4927.8      .1       0
  4974.9     .05       0  4994.5      .1       0  5198.2     .12       0
  5292.5     .07       0  5452.8     .05       0
Bank Sta=4974.9,4994.5
XS Rating Curve= 0 ,0
Exp/Cntr=0.3,0.1

Type RM Length L Ch R = 1 ,11723   ,483,483,483
BEGIN DESCRIPTION:
BIRDS CREEK 11.0
END DESCRIPTION:
XS GIS Cut Line= 3
      2456874.52     13624751.04        2457225.       13623475.
      2457388.24     13622299.07
#Sta/Elev= 30
  3676.7  248.36  3994.1  237.64  4078.6  231.37  4366.4  223.23  4476.8  221.86
  4861.1  215.47  4896.3  213.47  4927.4  216.73  4948.3  215.41  4977.6  207.02
  4982.8  207.45  4987.6  202.85  4988.1  202.35  5007.3  202.85  5010.1  206.53
  5020.2   210.9  5030.3  212.59  5080.7  214.56  5112.6  216.57  5153.4  215.22
    5273  215.96  5469.8  217.63  5547.8  220.34  5565.4  218.65  5686.2  222.06
  5999.5  224.64  6153.4  230.44  6171.1  234.67  6181.2  235.26  6187.2  232.96
#Mann= 11 ,-1 , 0
  3676.7     .05       0  4366.4     .07       0  4476.8     .12       0
  4861.1      .1       0  4987.6     .05       0  5007.3      .1       0
  5080.7     .07       0  5153.4      .1       0    5273     .07       0
  5469.8     .05       0  6153.4     .12       0
Bank Sta=4987.6,5007.3
XS Rating Curve= 0 ,0
Exp/Cntr=0.3,0.1

Type RM Length L Ch R = 1 ,11240   ,466,466,466
BEGIN DESCRIPTION:
BIRDS CREEK 10.0
END DESCRIPTION:
XS GIS Cut Line= 3
      2457814.95     13624450.53        2457675.       13623475.
        2457575.     13622375.05
#Sta/Elev= 30
  4014.4  240.84  4105.7  238.63  4188.4   233.5  4211.9  233.85    4259     231
  4373.6  228.29  4417.3  226.05  4436.9  225.71  4565.5  222.57  4626.1  218.57
  4678.6  217.25  4747.4  216.54  4767.6  214.19  4929.2  214.15  4979.7   211.2
  4987.5  202.56    4988  202.06  5007.2  202.56    5010  202.59    5020  209.71
  5060.2  215.89  5140.5   213.9  5160.5  214.81  5453.4  215.62  5702.8  218.11
  5773.1   220.3  5803.2  219.44  5903.6  222.87  5913.7  221.91  6104.4  231.79
#Mann= 9 ,-1 , 0
  4014.4     .05       0  4105.7     .12       0  4417.3     .07       0
  4436.9     .12       0  4678.6      .1       0  4987.5     .05       0
  5007.2      .1       0  5160.5     .07       0  5453.4     .05       0
Bank Sta=4987.5,5007.2
XS Rating Curve= 0 ,0
Exp/Cntr=0.3,0.1

Type RM Length L Ch R = 1 ,10774   ,663,663,663
BEGIN DESCRIPTION:
BIRDS CREEK 9.0
END DESCRIPTION:
XS GIS Cut Line= 3
      2458086.41     13624353.53        2458125.       13623525.
      2457625.01     13622325.02
#Sta/Elev= 30
  4170.6  234.82  4469.5  230.44  4662.8  224.21  4890.5  216.91  4919.9  213.18
    4950  211.41  4960.1  201.42  4960.6  200.92  4979.9  201.42  5009.2  206.38
  5032.5  206.97  5038.5  212.28  5043.9  210.15  5054.2  212.02  5086.2  213.56
  5215.6  213.11  5539.7  214.66  5741.6  215.57  5888.4  219.54  5953.9  219.39
  6025.9  222.04    6040  223.33  6061.7  222.31  6102.3  225.99  6131.6   225.6
    6170  228.59  6184.7  227.93  6261.6  232.68  6285.4  238.99    6300  239.71
#Mann= 8 ,-1 , 0
  4170.6     .05       0  4662.8     .12       0  4890.5      .1       0
  4960.1     .05       0  4979.9      .1       0  5215.6     .07       0
  5539.7     .12       0  6025.9     .05       0
Bank Sta=4960.1,4979.9
XS Rating Curve= 0 ,0
Exp/Cntr=0.3,0.1

Type RM Length L Ch R = 1 ,10111   ,787,787,787
BEGIN DESCRIPTION:
BIRDS CREEK 8.0
END DESCRIPTION:
XS GIS Cut Line= 3
      2458871.72     13624382.68      2458677.81     13623035.01
      2458212.45     13621823.13
#Sta/Elev= 30
  3928.6  232.09  4138.4   229.6  4188.9  227.56  4582.9  216.13  4876.6  212.06
  4956.8  211.05  4987.1   205.7  4997.3  199.67  4997.8  199.17  5017.2  199.67
  5017.4  203.49  5027.5  211.14    5096  210.24  5292.1  212.29  5485.1  211.86
  5550.5  211.02  5702.3  212.32  5921.2  215.11    5965  218.05  5981.3  216.86
  6005.9  220.47  6029.3  221.62  6041.3  224.69  6060.6   224.2  6072.1  226.42
    6096  225.28  6136.4  226.55  6314.7  237.36  6395.6  240.43  6588.3   246.6
#Mann= 11 ,-1 , 0
  3928.6     .05       0  4188.9    .035       0  4876.6      .1       0
  4997.3     .05       0  5017.2      .1       0    5096     .12       0
  5292.1     .05       0  5485.1     .07       0  5550.5     .05       0
  5702.3     .12       0  6395.6     .05       0
Bank Sta=4997.3,5017.2
XS Rating Curve= 0 ,0
Exp/Cntr=0.3,0.1

Type RM Length L Ch R = 1 ,9324    ,935,935,935
BEGIN DESCRIPTION:
BIRDS CREEK 7.0
END DESCRIPTION:
XS GIS Cut Line= 3
      2459240.13     13624528.08       2459298.3       13623258.
      2459627.94     13621483.78
#Sta/Elev= 30
  3389.7  231.14  3601.7  230.27  3845.2  222.95  4231.4  212.49    4381  210.85
  4492.4  210.68    4572  211.06  4729.2  208.95  4786.2  210.42  4949.1  209.57
  4969.3  206.24  4979.5  201.56  4979.6  200.03  4980.1  199.53  4999.6  200.03
  5001.9   204.8    5010  208.72  5030.3   211.3  5162.6  210.37  5450.2  212.66
  5487.3  213.58  5508.4  212.33  5528.7  216.64  5548.2  217.16  5569.4  214.13
  5587.4  214.32  5788.9  219.49  6088.1  231.78  6262.4   241.9  6465.7  252.37
#Mann= 15 ,-1 , 0
  3389.7     .05       0  3845.2    .035       0  4231.4      .1       0
    4381     .12       0  4492.4    .035       0    4572     .12       0
  4729.2      .1       0  4979.6     .05       0  4999.6      .1       0
  5162.6     .05       0  5450.2     .07       0  5548.2     .05       0
  5587.4     .12       0  5788.9     .05       0  6262.4     .07       0
Bank Sta=4979.6,4999.6
XS Rating Curve= 0 ,0
Exp/Cntr=0.3,0.1

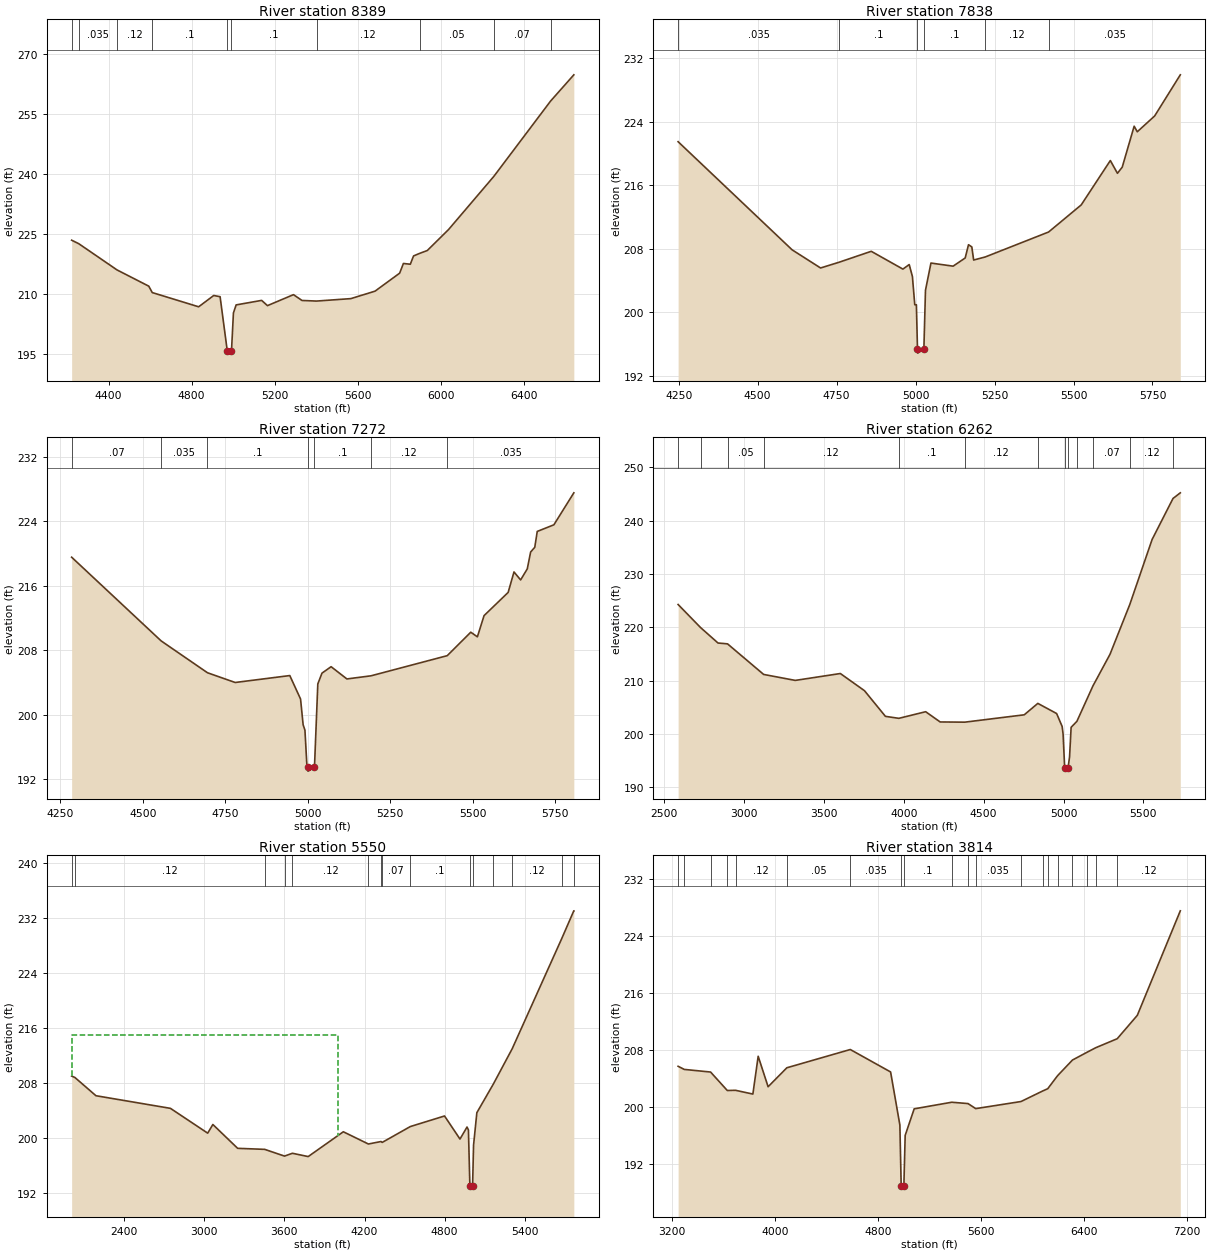
Type RM Length L Ch R = 1 ,8389    ,551,551,551
BEGIN DESCRIPTION:
BIRDS CREEK 6.0
END DESCRIPTION:
XS GIS Cut Line= 3
      2460124.99     13623924.98        2459775.       13623225.
      2460124.99     13621625.04
#Sta/Elev= 30
  4221.6  223.42    4256  222.54  4440.6  215.99  4593.3  211.95  4610.1  210.35
  4833.7   206.8  4906.4  209.62  4937.1  209.32  4971.8  195.74  4972.3  195.24
  4991.9  195.74  5001.4  205.27  5014.4  207.27  5137.3   208.4  5165.4  207.09
  5290.8  209.83  5331.8  208.38  5401.7  208.23  5567.2  208.84  5683.8   210.7
  5802.6   215.2  5820.6  217.61  5853.8  217.42  5869.5  219.49  5899.9  220.15
  5935.7  220.84  6038.1  226.07  6256.6  239.35  6529.9  258.13    6642  264.68
#Mann= 10 ,-1 , 0
  4221.6     .07       0    4256    .035       0  4440.6     .12       0
  4610.1      .1       0  4971.8     .05       0  4991.9      .1       0
  5401.7     .12       0  5899.9     .05       0  6256.6     .07       0
  6529.9    .035       0
Bank Sta=4971.8,4991.9
XS Rating Curve= 0 ,0
Exp/Cntr=0.3,0.1

Type RM Length L Ch R = 1 ,7838    ,566,566,566
BEGIN DESCRIPTION:
BIRDS CREEK 5.0
END DESCRIPTION:
XS GIS Cut Line= 3
        2460225.     13623825.02        2460275.       13623075.
      2460524.99     13622275.04
#Sta/Elev= 30
  4248.3  221.46  4609.1  207.85  4699.3  205.56  4758.4  206.29  4859.7  207.66
  4959.9  205.42  4979.9  205.99    4990  204.49  4997.5  200.93  5002.6  200.93
  5006.1  195.34  5006.6  194.84  5026.3  195.34  5031.4  202.75  5048.7  206.18
  5118.9  205.79  5157.1  206.82  5167.6  208.49  5178.1  208.21  5183.9  206.56
  5220.8  206.95  5421.2  210.09  5524.4   213.5  5616.6  219.09  5639.1  217.48
  5654.3  218.26    5692  223.41  5701.9  222.71  5756.9   224.7  5838.1  229.88
#Mann= 6 ,-1 , 0
  4248.3    .035       0  4758.4      .1       0  5006.1     .05       0
  5026.3      .1       0  5220.8     .12       0  5421.2    .035       0
Bank Sta=5006.1,5026.3
XS Rating Curve= 0 ,0
Exp/Cntr=0.3,0.1

Type RM Length L Ch R = 1 ,7272    ,1010,1010,1010
BEGIN DESCRIPTION:
BIRDS CREEK 4.0
END DESCRIPTION:
XS GIS Cut Line= 3
      2460525.02     13623774.96        2460825.       13623125.
        2460725.     13622324.97
#Sta/Elev= 30
  4284.6  219.55  4555.9  209.16  4696.3  205.21  4780.2     204  4945.8  204.86
  4978.4  201.95  4986.2  198.75  4991.7  198.08  4997.7  193.65  5000.4   193.5
  5000.9     193  5020.6   193.5  5030.7  203.82  5043.3  205.16    5071  205.96
  5118.9  204.44    5192  204.83    5423  207.33  5494.3  210.24  5514.4  209.67
  5534.6   212.3  5607.6  215.18  5625.3  217.72  5645.4  216.73  5665.6   218.1
  5675.7  220.19  5688.3  220.78  5695.8  222.75  5746.2  223.57  5806.7  227.54
#Mann= 7 ,-1 , 0
  4284.6     .07       0  4555.9    .035       0  4696.3      .1       0
  5000.4     .05       0  5020.6      .1       0    5192     .12       0
    5423    .035       0
Bank Sta=5000.4,5020.6
XS Rating Curve= 0 ,0
Exp/Cntr=0.3,0.1

Type RM Length L Ch R = 1 ,6262    ,712,712,712
BEGIN DESCRIPTION:
X18240
END DESCRIPTION:
XS GIS Cut Line= 3
      2461470.01     13625012.78       2461683.3     13623325.87
      2461450.62     13621900.68
#Sta/Elev= 30
  2586.9  224.29  2727.4  219.97  2836.7  217.07  2896.4  216.91  3122.4  211.18
  3320.5  210.06  3602.7  211.35  3753.9  208.13  3884.9  203.32  3969.1  202.95
  4136.9  204.19  4227.6  202.27  4381.9  202.23  4754.2  203.61  4839.2  205.75
  4956.9  203.85  4991.4  201.43  4997.4  199.99  5007.5  193.55    5008  193.05
  5027.8  193.55  5037.9  195.71  5047.7  201.27  5083.9  202.39  5184.2  209.02
  5291.2  214.96    5415  224.29  5554.7  236.48  5685.6  244.17  5731.3  245.23
#Mann= 13 ,-1 , 0
  2586.9     .05       0  2727.4    .035       0  2896.4     .05       0
  3122.4     .12       0  3969.1      .1       0  4381.9     .12       0
  4839.2      .1       0  5007.5     .05       0  5027.8      .1       0
  5083.9     .12       0  5184.2     .07       0    5415     .12       0
  5685.6    .035       0
Bank Sta=5007.5,5027.8
XS Rating Curve= 0 ,0
Exp/Cntr=0.3,0.1

Type RM Length L Ch R = 1 ,5550    ,1736,1736,1736
BEGIN DESCRIPTION:
X18239
END DESCRIPTION:
XS GIS Cut Line= 3
       2463108.5     13625167.98      2462109.89     13622123.67
      2461692.97     13621755.23
#Sta/Elev= 30
  2007.1     209  2031.1   208.8  2189.1  206.14  2746.9   204.3  3025.8  200.69
  3064.5  201.95  3250.2  198.48  3452.5  198.33    3601  197.35  3660.3  197.76
  3778.3  197.28  4041.4  200.89    4229  199.11  4323.8  199.47  4332.4  199.34
    4543  201.65  4799.2  203.19  4914.9  199.83  4967.6  201.58  4978.1  201.16
    4989  193.04  4989.5  192.54  5009.3  193.04  5016.5  198.94  5041.2  203.67
  5165.6  207.87  5305.9  212.98    5680  229.16  5767.1  233.06  5767.4  233.06
#Mann= 15 ,-1 , 0
  2007.1     .05       0  2031.1     .12       0  3452.5    .035       0
    3601     .07       0  3660.3     .12       0    4229     .07       0
  4323.8     .12       0  4332.4     .07       0    4543      .1       0
    4989     .05       0  5009.3      .1       0  5165.6    .035       0
  5305.9     .12       0    5680    .035       0  5767.1     .07       0
#XS Ineff= 2 , 0
       0    4000     215               0
Permanent Ineff=
       F       F
Bank Sta=4989,5009.3
XS Rating Curve= 0 ,0
Exp/Cntr=0.3,0.1

Type RM Length L Ch R = 1 ,3814    ,770,770,770
BEGIN DESCRIPTION:
BIRDS CREEK 3.0
END DESCRIPTION:
XS GIS Cut Line= 3
      2463981.04     13624624.98      2463535.07      13622850.8
      2461809.63     13621706.98
#Sta/Elev= 30
  3247.2  205.69  3294.7  205.25  3499.3  204.88  3629.2  202.28  3692.8  202.31
  3827.7  201.78  3868.9   207.1    3946  202.81  4091.6  205.48  4584.1  208.05
  4897.2  204.89  4969.1  197.43  4979.3   188.9  4979.8   188.4  5000.2   188.9
  5010.3  195.96  5080.3   199.7  5371.9  200.63  5498.4  200.44  5558.2  199.73
  5909.8  200.73  6077.7  202.21  6117.2  202.53  6193.5  204.36  6309.4  206.57
  6425.2  207.69  6489.8   208.3  6656.9  209.57  6812.9  212.86  7146.7  227.57
#Mann= 20 ,-1 , 0
  3247.2     .05       0  3294.7    .035       0  3499.3    .035       0
  3629.2     .05       0  3692.8     .12       0  4091.6     .05       0
  4584.1    .035       0  4979.3     .05       0  5000.2      .1       0
  5371.9    .035       0  5498.4     .07       0  5558.2    .035       0
  5909.8     .07       0  6077.7    .035       0  6117.2     .12       0
  6193.5     .07       0  6309.4     .07       0  6425.2     .12       0
  6489.8     .07       0  6656.9     .12       0
Bank Sta=4979.3,5000.2
XS Rating Curve= 0 ,0
Exp/Cntr=0.3,0.1

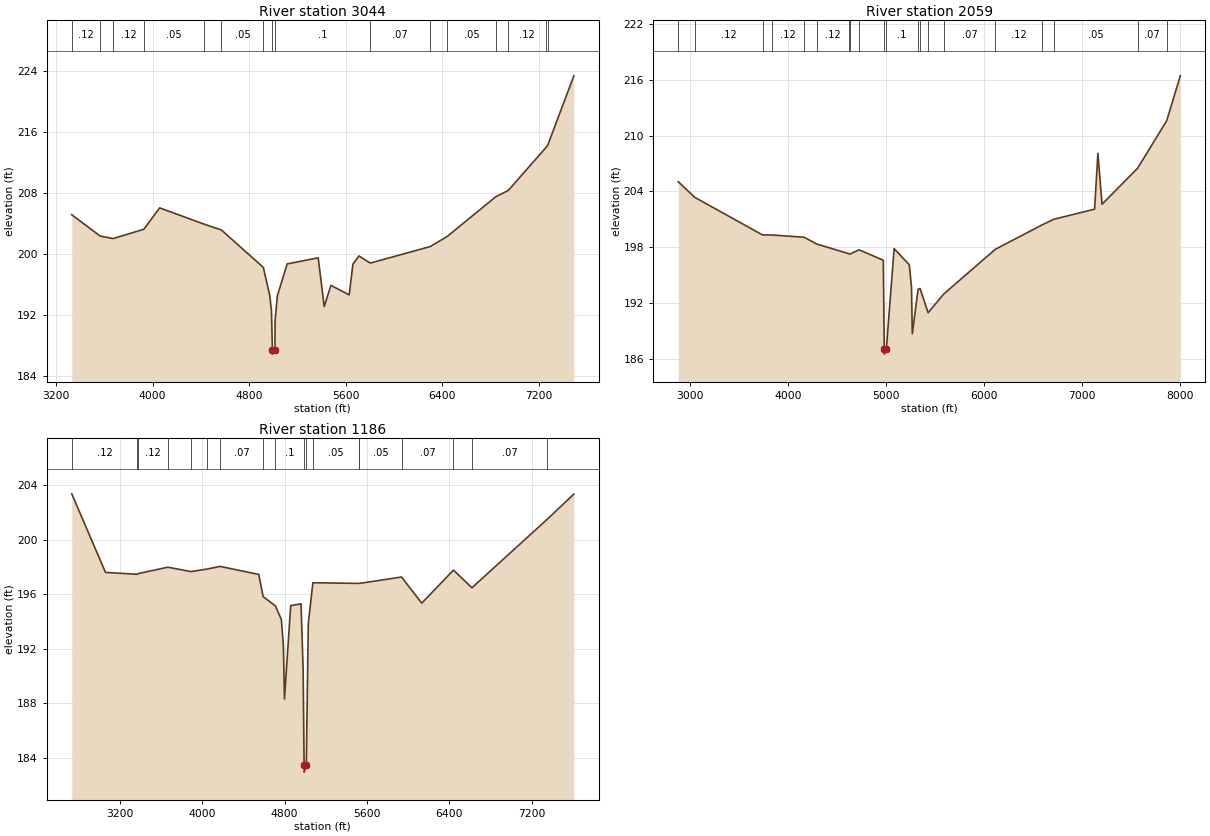
Type RM Length L Ch R = 1 ,3044    ,985,985,985
BEGIN DESCRIPTION:
BIRDS CREEK 2.0
END DESCRIPTION:
XS GIS Cut Line= 3
      2464795.42     13624130.52      2464145.86     13622482.39
        2461910.     13621649.99
#Sta/Elev= 30
  3330.4  205.15    3567  202.34  3674.1  202.03  3927.8  203.25  4058.1  206.05
  4423.8  203.93  4569.7  203.15  4916.8  198.24  4970.1  194.53  4983.9  192.53
  4991.9  187.37  4992.4  186.87  5012.8  187.37  5013.6   191.2  5032.7   194.5
  5113.8   198.7  5370.8   199.5  5420.8  193.11  5476.2  195.89  5627.8  194.64
  5658.2  198.66  5708.2  199.75  5802.4  198.81    6299  200.98  6440.5  202.32
  6841.2  207.51    6945  208.34    7257  213.97  7271.3  214.26  7487.7  223.37
#Mann= 16 ,-1 , 0
  3330.4     .12       0    3567    .035       0  3674.1     .12       0
  3927.8     .05       0  4423.8    .035       0  4569.7     .05       0
  4916.8      .1       0  4991.9     .05       0  5012.8      .1       0
  5802.4     .07       0    6299     .12       0  6440.5     .05       0
  6841.2     .07       0    6945     .12       0    7257     .07       0
  7271.3     .12       0
Bank Sta=4991.9,5012.8
XS Rating Curve= 0 ,0
Exp/Cntr=0.3,0.1

Type RM Length L Ch R = 1 ,2059    ,873,873,873
BEGIN DESCRIPTION:
X18238
END DESCRIPTION:
XS GIS Cut Line= 3
      2464892.38     13624082.04      2464717.87     13621774.65
      2461983.86     13621125.08
#Sta/Elev= 30
  2877.4  205.06  3044.7  203.38  3737.8  199.33  3836.8  199.32  4161.9  199.08
  4293.3  198.34    4620  197.31  4631.1  197.27    4722  197.73  4970.4  196.61
  4979.9  187.01  4980.4  186.51    5001  187.01  5080.7  197.86  5235.5  196.12
  5257.9  193.75  5266.3   188.7  5325.4  193.49  5345.9  193.56  5427.6  190.96
  5585.7  192.96    6113  197.78    6589   200.4  6712.2  201.02  7126.7   202.1
  7160.4  208.11  7202.6  202.63  7566.5  206.51  7862.9  211.62  8001.5  216.44
#Mann= 20 ,-1 , 0
  2877.4    .035       0  3044.7     .12       0  3737.8    .035       0
  3836.8     .12       0  4161.9     .05       0  4293.3     .12       0
    4620      .1       0  4631.1     .12       0    4722      .1       0
  4979.9     .05       0    5001      .1       0  5325.4     .12       0
  5345.9     .07       0  5427.6     .12       0  5585.7     .07       0
    6113     .12       0    6589     .07       0  6712.2     .05       0
  7566.5     .07       0  7862.9     .05       0
Bank Sta=4979.9,5001
XS Rating Curve= 0 ,0
Exp/Cntr=0.3,0.1

Type RM Length L Ch R = 1 ,1186    ,0,0,0
BEGIN DESCRIPTION:
BIRDS CREEK 1.0
END DESCRIPTION:
XS GIS Cut Line= 4
      2464940.85     13623946.38      2465541.96     13622084.89
      2465493.48       13621668.      2463030.88     13621222.02
#Sta/Elev= 30
  2731.7  203.37  3059.3   197.6  3369.4  197.46  3376.3  197.51  3665.6  197.98
  3890.7  197.66  4043.7  197.84    4173  198.04  4548.6  197.45  4591.3  195.82
  4710.7  195.14  4768.3  194.14  4787.4  192.28  4798.5   188.3  4858.9  195.16
  4959.5  195.29  4979.7  190.46  4989.3  183.43  4989.8  182.93  5010.4  183.43
    5030  193.84  5074.6  196.84  5523.3  196.79  5526.8  196.79  5936.1  197.26
  6132.4  195.34  6440.7  197.77    6620  196.47  7354.2  201.52  7610.2  203.35
#Mann= 18 ,-1 , 0
  2731.7     .12       0  3369.4    .035       0  3376.3     .12       0
  3665.6     .05       0  3890.7     .07       0  4043.7     .12       0
    4173     .07       0  4591.3     .12       0  4710.7      .1       0
  4989.3     .05       0  5010.4      .1       0  5074.6     .05       0
  5523.3     .12       0  5526.8     .05       0  5936.1     .07       0
  6440.7     .12       0    6620     .07       0  7354.2     .05       0
Bank Sta=4989.3,5010.4
XS Rating Curve= 0 ,0
Exp/Cntr=0.3,0.1

Chan Stop Cuts=-1
Use User Specified Reach Order=0
Composite Channel Slope=5