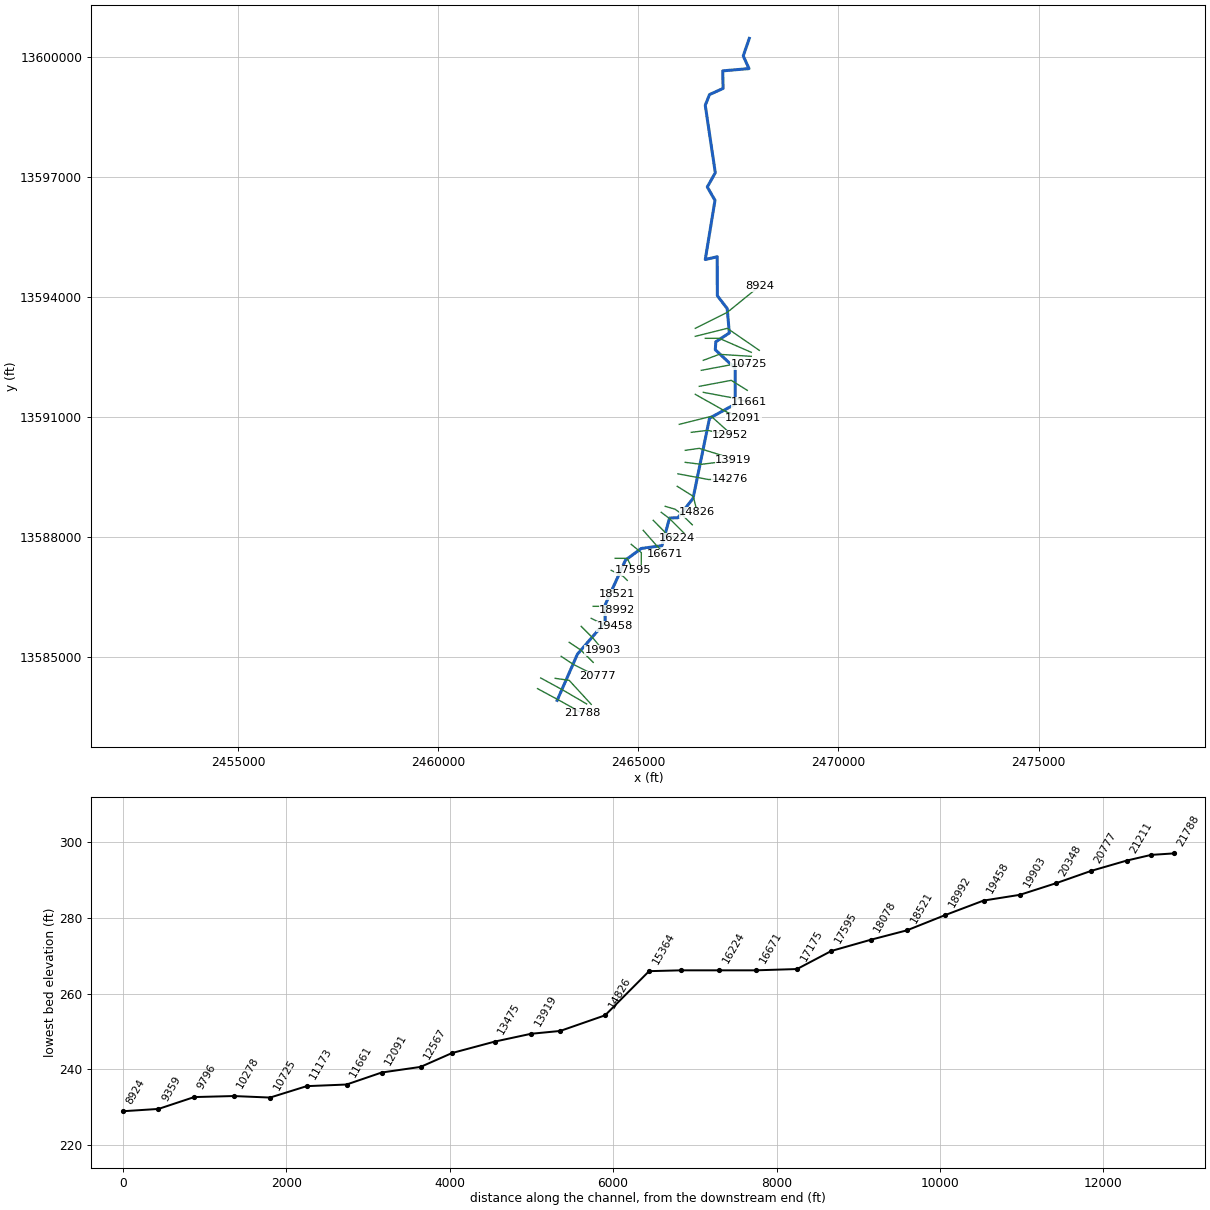
--- BLACKJACK CREEK.prj (project) ---

Proj Title=BLACKJACK CREEK Base Level Engineering
Current Plan=p01
Default Exp/Contr=0.3,0.1
English Units
Geom File=g01
Flow File=f01
Plan File=p01
Y Axis Title=Elevation
X Axis Title(PF)=Main Channel Distance
X Axis Title(XS)=Station
BEGIN DESCRIPTION:
BLACKJACK CREEK
END DESCRIPTION:
DSS Export Rating Curves= 0
DSS Export Rating Curve Sorted= 0
DSS Export Volume Flow Curves= 0
DXF OffsetX= 0
DXF OffsetY= 0
DXF ScaleX= 1
DXF ScaleY= 10

--- BLACKJACK CREEK.p01 (plan) ---

Plan Title=Multiple Run
Short Identifier=Multiple
Geom File=g01
Flow File=f01
Subcritical Flow
K Sum by GR= 0
Std Step Tol= 0.01
Critical Tol= 0.01
Num of Std Step Trials= 20
Max Error Tol= 0.3
Flow Tol Ratio= 0.001
Split Flow NTrial= 30
Split Flow Tol= 0.02
Split Flow Ratio= 0.02
Log Output Level= 0
Friction Slope Method= 1
Unsteady Friction Slope Method= 2
Unsteady Bridges Friction Slope Method= 1
Parabolic Critical Depth
Global Vel Dist=  1 , 1 , 1
Global Log Level= 0
CheckData=True
Encroach Param= -1, 0, 0, 0
BEGIN DESCRIPTION:
Multiple Run
END DESCRIPTION:

--- BLACKJACK CREEK.f01 (steady flow) ---

Flow Title=Multiple
Number of Profiles=7
Profile Names=10-year,25-year,50-year,1pct_min,100-year,1pct_plu,500-year
River Rch & RM= BLACKJACK CREEK,Reach-1,21788
     688    1114    1500     978    1951    3893    3271
River Rch & RM= BLACKJACK CREEK,Reach-1,16671
     835    1362    1842    1205    2405    4798    4061
River Rch & RM= BLACKJACK CREEK,Reach-1,14276
    1578    2656    3670    2447    4883    9743    8573
River Rch & RM= BLACKJACK CREEK,Reach-1,12567
    1745    2947    4081    2726    5439   10853    9583
River Rch & RM= BLACKJACK CREEK,Reach-1,8455
    1986    3369    4678    3133    6250   12471   11067
River Rch & RM= BLACKJACK CREEK,Reach-1,4198
    2083    3541    4925    3302    6589   13146   11697
Boundary for River Rch & Prof#=BLACKJACK CREEK,Reach-1,1
Up Type=0
Dn Type=3
Dn Slope=0.005
Boundary for River Rch & Prof#=BLACKJACK CREEK,Reach-1,2
Up Type=0
Dn Type=3
Dn Slope=0.005
Boundary for River Rch & Prof#=BLACKJACK CREEK,Reach-1,3
Up Type=0
Dn Type=3
Dn Slope=0.005
Boundary for River Rch & Prof#=BLACKJACK CREEK,Reach-1,4
Up Type=0
Dn Type=3
Dn Slope=0.005
Boundary for River Rch & Prof#=BLACKJACK CREEK,Reach-1,5
Up Type=0
Dn Type=3
Dn Slope=0.005
Boundary for River Rch & Prof#=BLACKJACK CREEK,Reach-1,6
Up Type=0
Dn Type=3
Dn Slope=0.005
Boundary for River Rch & Prof#=BLACKJACK CREEK,Reach-1,7
Up Type=0
Dn Type=3
Dn Slope=0.005

--- BLACKJACK CREEK.g01 (geometry) ---

Geom Title=Existing Conditions

River Reach=BLACKJACK CREEK,Reach-1
Reach XY= 30
      2462975.00     13583925.00      2463480.47     13585077.45
      2464171.25     13585876.55      2464177.26     13586319.06
      2464682.80     13587431.21      2465076.22     13587721.56
      2465592.13     13587791.29      2465782.62     13588481.51
      2465992.09     13588491.14      2466369.17     13588972.70
      2466780.79     13590977.32      2467422.94     13591330.85
      2467421.66     13592223.28      2466925.38     13592690.16
      2466938.36     13592888.35      2467275.79     13593109.86
      2467222.94     13593719.14      2466975.92     13594040.94
      2466973.95     13595014.91      2466674.95     13594944.91
      2466917.69     13596425.10      2466725.50     13596759.79
      2466925.50     13597114.79      2466674.80     13598800.08
      2466780.59     13599069.39      2467120.03     13599222.41
      2467111.75     13599661.89      2467767.36     13599718.54
      2467624.16     13600035.06      2467775.00     13600475.00

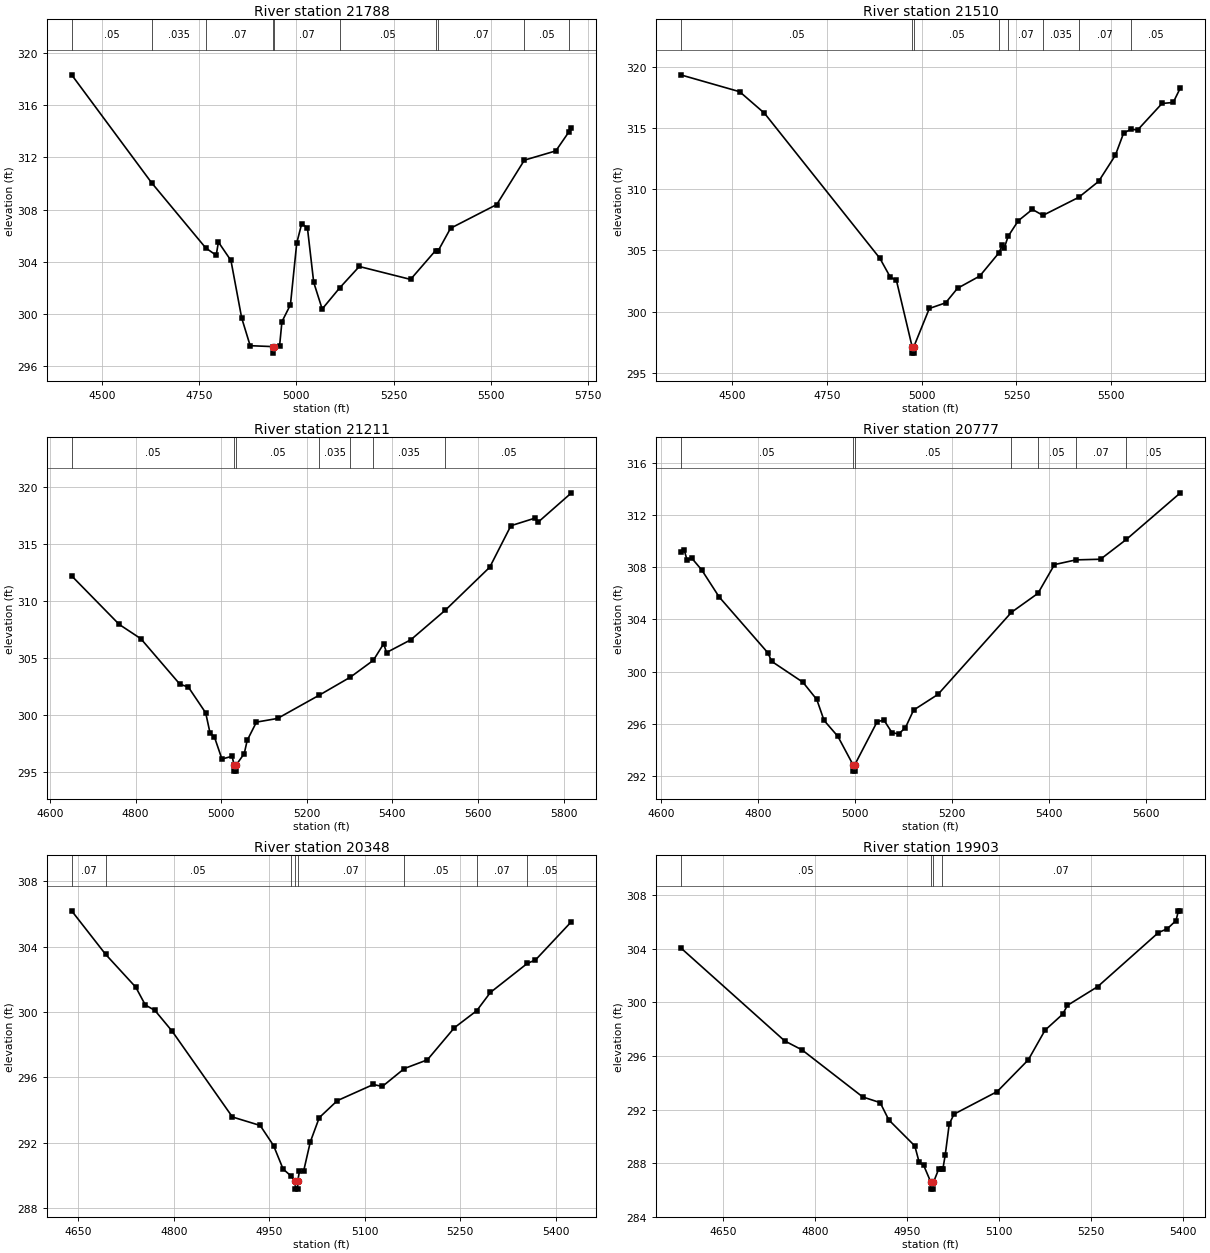
Type RM Length L Ch R = 1,21788,278,278,278
BEGIN DESCRIPTION:
X18246
END DESCRIPTION:
XS GIS Cut Line= 3
      2462484.15     13584217.97      2463044.16     13583914.80
      2463612.62     13583598.99
#Sta/Elev= 30
  4421.2  318.33  4627.0  310.06  4766.5  305.06  4793.4  304.50  4799.1  305.51
  4831.4  304.10  4859.0  299.70  4880.9  297.57  4938.8  297.50  4939.1  297.00
  4942.8  297.50  4956.6  297.54  4962.7  299.41  4984.6  300.71  5000.8  305.43
  5013.5  306.91  5028.3  306.61  5044.5  302.43  5066.3  300.38  5111.1  301.99
  5161.9  303.64  5293.9  302.65  5358.3  304.86  5364.4  304.81  5396.9  306.57
  5515.9  308.39  5587.0  311.79  5668.0  312.50  5701.3  313.94  5708.3  314.28
#Mann=10,-1,0
  4421.2    0.05       0  4627.0   0.035       0  4766.5    0.07       0
  4938.8    0.05       0  4942.8    0.07       0  5111.1    0.05       0
  5358.3   0.035       0  5364.4    0.07       0  5587.0    0.05       0
  5701.3   0.035       0
Bank Sta=4938.8,4942.8
Exp/Cntr=0.3,0.1

Type RM Length L Ch R = 1,21510,299,299,299
BEGIN DESCRIPTION:
BLACKJACK CREEK 46.0
END DESCRIPTION:
XS GIS Cut Line= 3
      2462562.88     13584484.49      2463112.90     13584184.48
      2463711.48     13583835.30
#Sta/Elev= 30
  4363.3  319.36  4519.2  317.98  4584.7  316.22  4889.4  304.36  4916.9  302.82
  4933.0  302.56  4974.7  297.11  4975.0  296.61  4978.5  296.61  4978.7  297.11
  5019.9  300.26  5062.9  300.72  5094.3  301.91  5153.0  302.91  5204.0  304.82
  5211.7  305.41  5217.5  305.18  5228.0  306.16  5254.7  307.43  5291.9  308.36
  5319.8  307.87  5414.5  309.35  5466.9  310.65  5511.1  312.79  5532.6  314.58
  5551.4  314.91  5569.8  314.85  5634.3  317.02  5663.7  317.10  5682.8  318.30
#Mann=8,-1,0
  4363.3    0.05       0  4974.7    0.05       0  4978.7    0.05       0
  5204.0   0.035       0  5228.0    0.07       0  5319.8   0.035       0
  5414.5    0.07       0  5551.4    0.05       0
Bank Sta=4974.7,4978.7
Exp/Cntr=0.3,0.1

Type RM Length L Ch R = 1,21211,434,434,434
BEGIN DESCRIPTION:
BLACKJACK CREEK 45.0
END DESCRIPTION:
XS GIS Cut Line= 3
      2462925.00     13584475.00      2463275.00     13584425.00
      2463825.01     13583824.99
#Sta/Elev= 30
  4650.8  312.20  4761.9  307.95  4812.4  306.70  4903.3  302.73  4923.5  302.46
  4963.9  300.21  4974.0  298.45  4984.1  298.12  5001.8  296.17  5025.6  296.41
  5030.4  295.61  5030.7  295.11  5034.2  295.11  5034.4  295.61  5054.0  296.65
  5060.8  297.80  5082.4  299.40  5131.7  299.72  5229.7  301.77  5302.0  303.34
  5355.5  304.81  5379.6  306.26  5386.3  305.49  5443.1  306.61  5523.7  309.20
  5627.4  312.96  5676.8  316.59  5733.5  317.26  5740.3  316.90  5818.3  319.47
#Mann=7,-1,0
  4650.8    0.05       0  5030.4    0.05       0  5034.4    0.05       0
  5229.7   0.035       0  5302.0    0.05       0  5355.5   0.035       0
  5523.7    0.05       0
Bank Sta=5030.4,5034.4
Exp/Cntr=0.3,0.1

Type RM Length L Ch R = 1,20777,429,429,429
BEGIN DESCRIPTION:
BLACKJACK CREEK 44.0
END DESCRIPTION:
XS GIS Cut Line= 3
      2463074.98     13585025.01      2463375.00     13584825.00
      2463975.00     13584525.00
#Sta/Elev= 30
  4639.7  309.17  4647.2  309.31  4653.2  308.52  4662.3  308.71  4683.3  307.79
  4719.3  305.72  4820.0  301.44  4827.5  300.80  4892.1  299.20  4920.7  297.88
  4935.7  296.28  4964.2  295.06  4995.3  292.90  4995.5  292.40  4999.0  292.40
  4999.3  292.90  5045.0  296.16  5059.0  296.32  5075.7  295.35  5089.7  295.24
  5103.7  295.73  5120.5  297.07  5170.8  298.27  5322.4  304.55  5377.1  306.00
  5411.2  308.20  5455.4  308.56  5506.2  308.61  5559.7  310.13  5671.1  313.69
#Mann=7,-1,0
  4639.7    0.05       0  4995.3    0.05       0  4999.3    0.05       0
  5322.4    0.07       0  5377.1    0.05       0  5455.4    0.07       0
  5559.7    0.05       0
Bank Sta=4995.3,4999.3
Exp/Cntr=0.3,0.1

Type RM Length L Ch R = 1,20348,445,445,445
BEGIN DESCRIPTION:
BLACKJACK CREEK 43.0
END DESCRIPTION:
XS GIS Cut Line= 3
      2463275.00     13585375.00      2463575.00     13585175.00
      2463874.98     13584875.02
#Sta/Elev= 30
  4639.7  306.20  4692.9  303.54  4740.4  301.52  4755.4  300.43  4770.4  300.10
  4797.4  298.83  4892.1  293.57  4935.7  293.05  4956.7  291.82  4971.7  290.38
  4984.0  289.96  4990.7  289.65  4991.0  289.15  4994.5  289.15  4994.7  289.65
  4997.3  290.23  5003.8  290.23  5014.4  292.04  5028.5  293.53  5056.8  294.57
  5113.4  295.56  5127.5  295.44  5162.2  296.54  5198.2  297.07  5240.7  299.04
  5275.7  300.08  5297.2  301.20  5355.2  302.98  5368.0  303.19  5424.5  305.54
#Mann=8,-1,0
  4639.7    0.07       0  4692.9    0.05       0  4984.0    0.07       0
  4990.7    0.05       0  4994.7    0.07       0  5162.2    0.05       0
  5275.7    0.07       0  5355.2    0.05       0
Bank Sta=4990.7,4994.7
Exp/Cntr=0.3,0.1

Type RM Length L Ch R = 1,19903,445,445,445
BEGIN DESCRIPTION:
BLACKJACK CREEK 42.0
END DESCRIPTION:
XS GIS Cut Line= 3
      2463575.01     13585774.99      2463875.00     13585475.00
      2464125.02     13585174.97
#Sta/Elev= 30
  4580.8  304.07  4750.5  297.12  4778.8  296.45  4877.8  292.94  4906.1  292.52
  4920.2  291.23  4962.6  289.29  4969.7  288.07  4976.8  287.87  4988.9  286.57
  4989.2  286.07  4992.7  286.07  4992.9  286.57  5001.5  287.56  5006.4  287.56
  5008.3  287.56  5012.2  288.62  5018.7  290.92  5026.5  291.66  5096.8  293.34
  5147.6  295.71  5174.9  297.92  5203.6  299.11  5211.4  299.77  5260.8  301.17
  5359.8  305.20  5374.1  305.48  5388.4  306.09  5392.3  306.82  5395.6  306.82
#Mann=4,-1,0
  4580.8    0.05       0  4988.9    0.05       0  4992.9    0.05       0
  5006.4    0.07       0
Bank Sta=4988.9,4992.9
Exp/Cntr=0.3,0.1

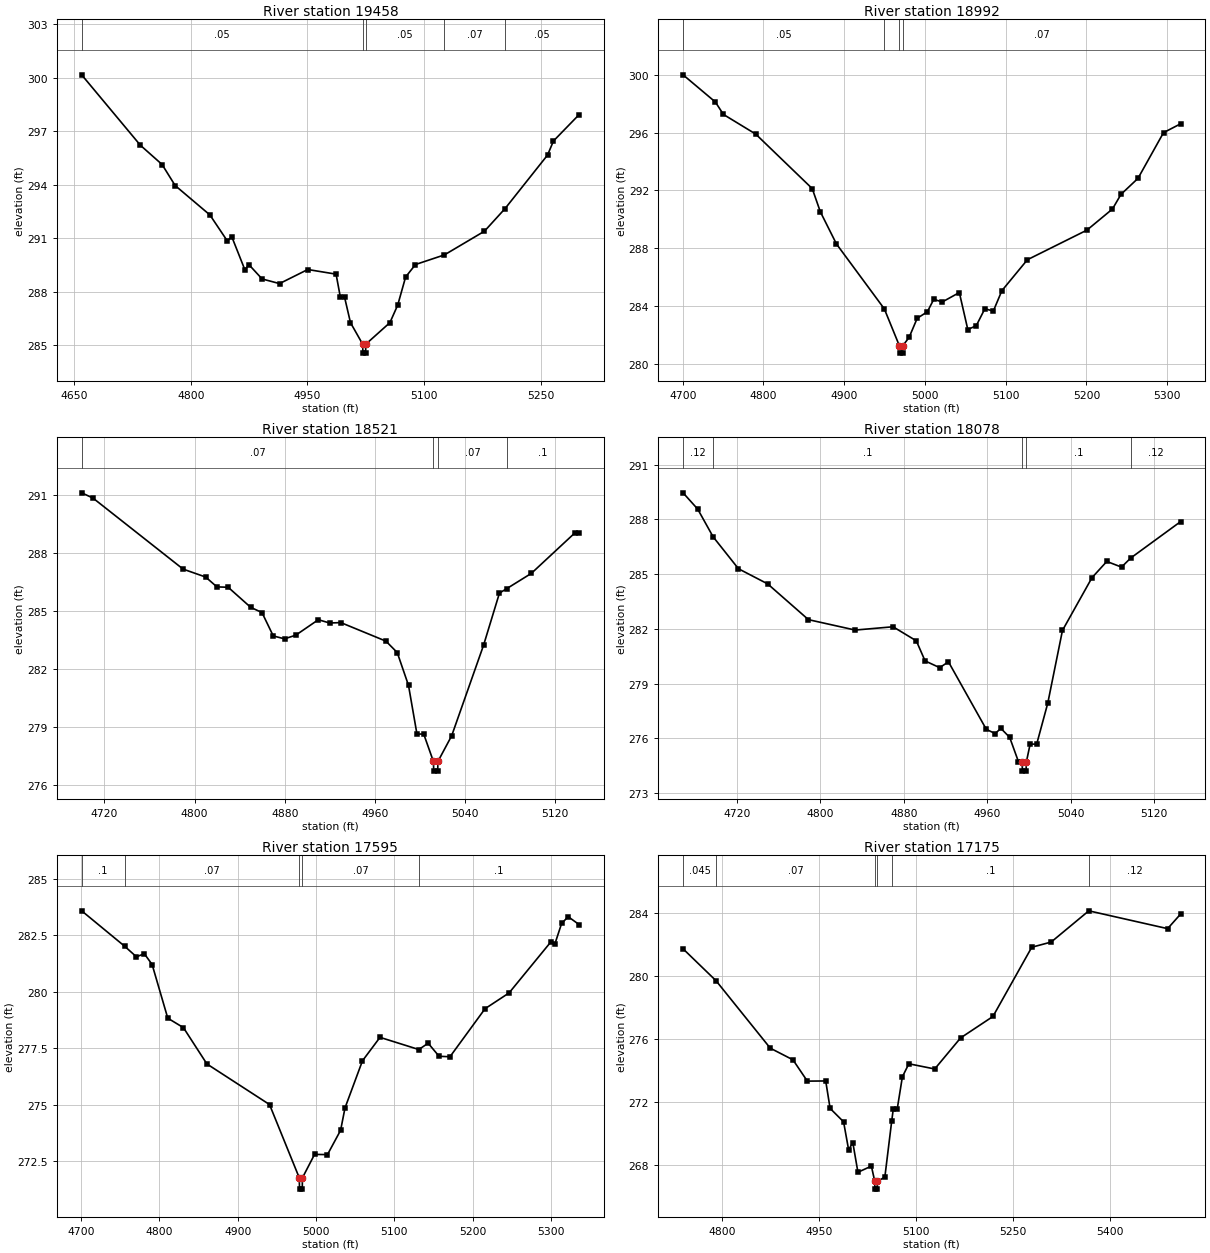
Type RM Length L Ch R = 1,19458,466,466,466
BEGIN DESCRIPTION:
BLACKJACK CREEK 41.0
END DESCRIPTION:
XS GIS Cut Line= 3
      2463824.97     13585975.01      2464125.00     13585825.00
      2464425.02     13585775.00
#Sta/Elev= 30
  4659.8  300.16  4735.3  296.21  4763.2  295.13  4780.0  293.95  4824.7  292.30
  4847.1  290.84  4852.7  291.09  4869.5  289.24  4875.1  289.50  4891.8  288.71
  4914.2  288.45  4950.5  289.24  4986.9  288.98  4992.4  287.69  4997.8  287.69
  5005.4  286.26  5021.1  285.05  5021.4  284.55  5024.9  284.55  5025.1  285.05
  5056.1  286.26  5066.2  287.25  5076.3  288.82  5089.0  289.52  5126.2  290.06
  5177.7  291.39  5204.2  292.66  5258.8  295.66  5266.4  296.45  5299.4  297.93
#Mann=5,-1,0
  4659.8    0.05       0  5021.1    0.05       0  5025.1    0.05       0
  5126.2    0.07       0  5204.2    0.05       0
Bank Sta=5021.1,5025.1
Exp/Cntr=0.3,0.1

Type RM Length L Ch R = 1,18992,471,471,471
BEGIN DESCRIPTION:
BLACKJACK CREEK 40.0
END DESCRIPTION:
XS GIS Cut Line= 3
      2463875.00     13586275.00      2464175.00     13586275.00
      2464474.97     13586175.01
#Sta/Elev= 30
  4700.4  300.00  4740.4  298.12  4750.4  297.26  4790.4  295.90  4860.4  292.13
  4870.4  290.53  4890.4  288.30  4949.7  283.81  4968.4  281.25  4968.7  280.75
  4972.2  280.75  4972.4  281.25  4980.4  281.84  4990.4  283.16  5003.0  283.61
  5010.9  284.47  5021.5  284.29  5042.6  284.94  5053.1  282.38  5063.6  282.65
  5074.2  283.82  5084.7  283.66  5095.3  285.07  5126.9  287.21  5200.7  289.26
  5232.3  290.72  5242.8  291.73  5263.9  292.84  5295.5  296.00  5316.6  296.61
#Mann=4,-1,0
  4700.4    0.05       0  4949.7    0.07       0  4968.4    0.05       0
  4972.4    0.07       0
Bank Sta=4968.4,4972.4
Exp/Cntr=0.3,0.1

Type RM Length L Ch R = 1,18521,443,443,443
BEGIN DESCRIPTION:
BLACKJACK CREEK 39.0
END DESCRIPTION:
XS GIS Cut Line= 3
      2464075.01     13586675.00      2464375.00     13586675.00
      2464474.99     13586575.01
#Sta/Elev= 30
  4699.8  291.11  4709.8  290.84  4789.8  287.16  4809.8  286.75  4819.8  286.24
  4829.8  286.22  4849.8  285.18  4859.8  284.91  4869.8  283.70  4879.8  283.55
  4889.8  283.74  4909.8  284.54  4919.8  284.37  4929.8  284.39  4969.8  283.43
  4979.8  282.84  4989.8  281.14  4997.3  278.62  5003.3  278.62  5011.9  277.20
  5012.2  276.70  5015.7  276.70  5015.9  277.20  5028.1  278.53  5056.4  283.22
  5070.5  285.92  5077.0  286.15  5098.8  286.94  5137.7  289.05  5141.2  289.05
#Mann=4,-1,0
  4699.8    0.07       0  5011.9    0.05       0  5015.9    0.07       0
  5077.0     0.1       0
Bank Sta=5011.9,5015.9
Exp/Cntr=0.3,0.1

Type RM Length L Ch R = 1,18078,483,483,483
BEGIN DESCRIPTION:
BLACKJACK CREEK 38.0
END DESCRIPTION:
XS GIS Cut Line= 3
      2464324.96     13587175.02      2464625.00     13587025.00
      2464725.02     13586924.98
#Sta/Elev= 30
  4668.5  289.46  4682.5  288.57  4697.3  287.05  4721.6  285.30  4749.6  284.47
  4788.7  282.51  4833.5  281.94  4869.8  282.12  4892.1  281.35  4900.5  280.25
  4914.5  279.88  4922.9  280.20  4959.2  276.50  4967.6  276.27  4973.2  276.55
  4981.6  276.06  4990.0  274.73  4993.6  274.71  4993.8  274.21  4997.3  274.21
  4997.6  274.71  5001.2  275.69  5007.5  275.69  5018.1  277.93  5032.2  281.92
  5060.5  284.81  5074.7  285.70  5088.8  285.39  5097.7  285.89  5145.4  287.88
#Mann=5,-1,0
  4668.5    0.12       0  4697.3     0.1       0  4993.6    0.05       0
  4997.6     0.1       0  5097.7    0.12       0
Bank Sta=4993.6,4997.6
Exp/Cntr=0.3,0.1

Type RM Length L Ch R = 1,17595,420,420,420
BEGIN DESCRIPTION:
BLACKJACK CREEK 37.0
END DESCRIPTION:
XS GIS Cut Line= 3
      2464424.95     13587475.00      2464725.00     13587475.00
      2464875.02     13587174.96
#Sta/Elev= 30
  4700.7  283.59  4755.6  282.02  4770.7  281.55  4780.7  281.69  4790.7  281.21
  4810.7  278.83  4830.7  278.41  4860.7  276.80  4940.7  275.00  4978.7  271.75
  4979.0  271.25  4982.5  271.25  4982.7  271.75  4998.2  272.79  5014.7  272.78
  5031.5  273.86  5037.1  274.85  5059.4  276.94  5081.8  277.98  5131.4  277.44
  5143.3  277.72  5157.3  277.14  5171.2  277.12  5216.0  279.25  5246.7  279.95
  5299.8  282.20  5305.4  282.14  5313.8  283.03  5322.2  283.33  5336.2  282.98
#Mann=5,-1,0
  4700.7     0.1       0  4755.6    0.07       0  4978.7    0.05       0
  4982.7    0.07       0  5131.4     0.1       0
Bank Sta=4978.7,4982.7
Exp/Cntr=0.3,0.1

Type RM Length L Ch R = 1,17175,504,504,504
BEGIN DESCRIPTION:
BLACKJACK CREEK 36.0
END DESCRIPTION:
XS GIS Cut Line= 3
      2464825.04     13587824.97      2465077.89     13587615.93
      2465075.00     13587175.01
#Sta/Elev= 30
  4740.0  281.72  4790.9  279.70  4874.8  275.42  4909.9  274.68  4932.1  273.33
  4960.5  273.34  4967.3  271.60  4988.1  270.75  4995.9  268.98  5002.4  269.43
  5010.3  267.55  5031.1  267.94  5036.3  266.98  5036.6  266.48  5040.2  266.48
  5040.4  266.98  5051.9  267.24  5062.5  270.79  5064.9  271.55  5071.0  271.55
  5079.0  273.60  5089.0  274.43  5129.0  274.10  5169.0  276.07  5219.0  277.43
  5279.0  281.82  5309.0  282.15  5367.2  284.13  5489.0  283.00  5509.0  283.92
#Mann=6,-1,0
  4740.0   0.045       0  4790.9    0.07       0  5036.3    0.05       0
  5040.4    0.07       0  5062.5     0.1       0  5367.2    0.12       0
Bank Sta=5036.3,5040.4
Exp/Cntr=0.3,0.1

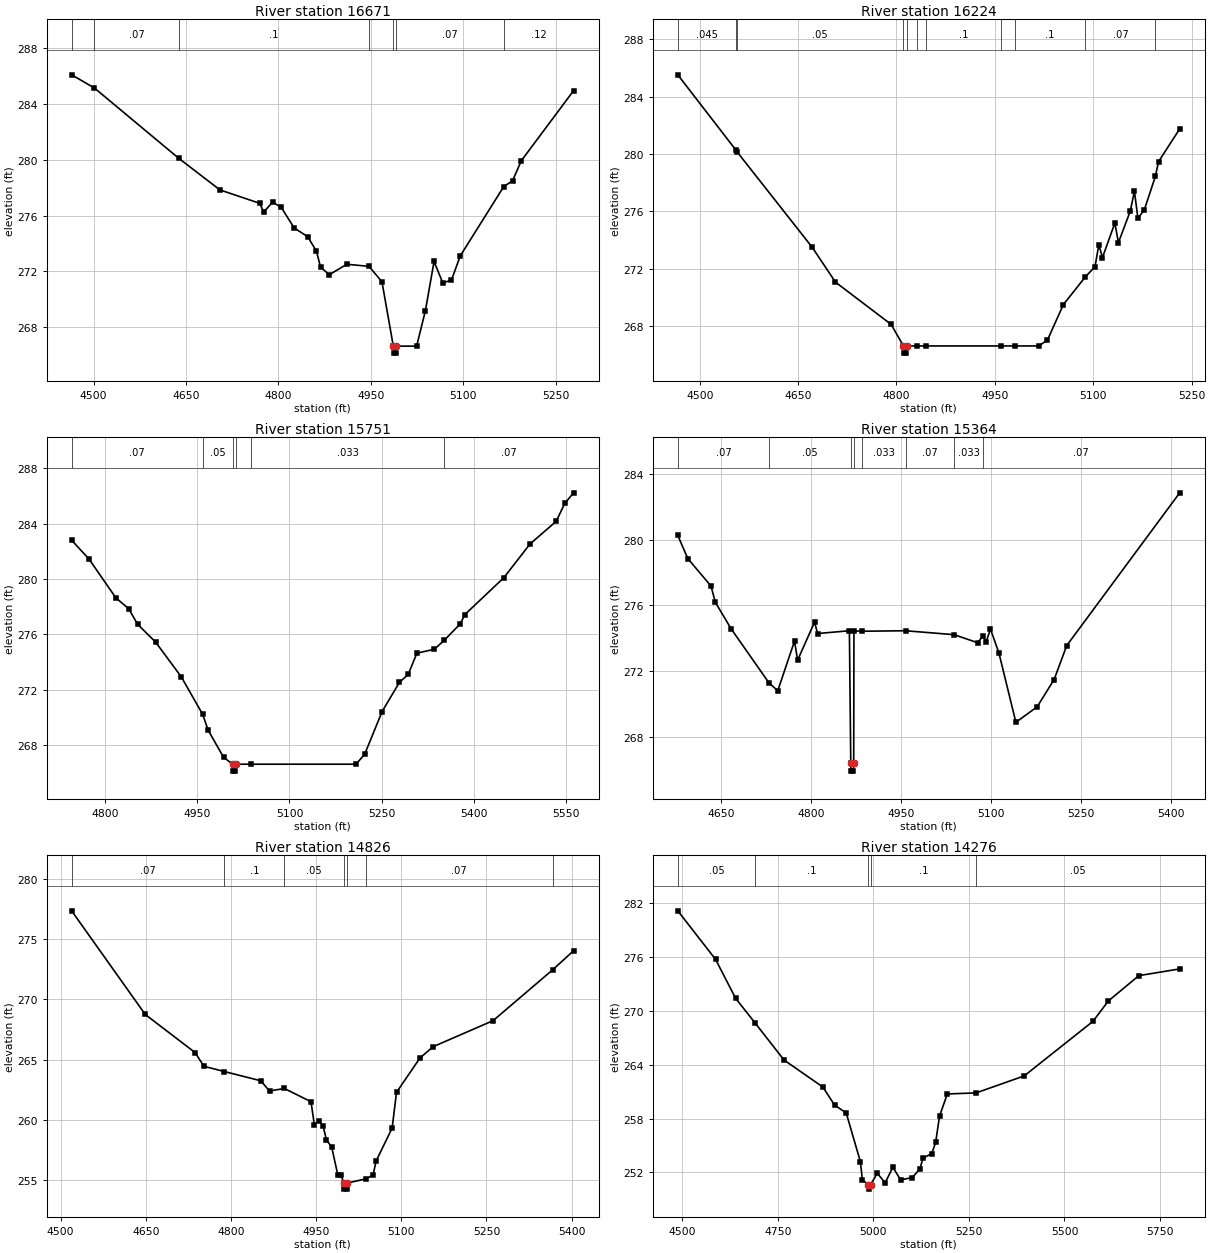
Type RM Length L Ch R = 1,16671,447,447,447
BEGIN DESCRIPTION:
BLACKJACK CREEK 35.0
END DESCRIPTION:
XS GIS Cut Line= 3
      2465125.03     13588174.97      2465475.00     13587775.00
      2465675.00     13587575.00
#Sta/Elev= 30
  4464.4  286.09  4501.2  285.15  4637.8  280.12  4705.0  277.84  4769.5  276.88
  4776.1  276.25  4790.4  276.97  4804.6  276.58  4825.5  275.11  4847.3  274.49
  4861.6  273.45  4868.2  272.31  4882.4  271.76  4910.9  272.51  4946.9  272.36
  4967.9  271.25  4986.3  266.64  4986.7  266.14  4990.8  266.14  4991.1  266.64
  5024.1  266.64  5038.3  269.17  5052.4  272.71  5066.6  271.17  5080.7  271.38
  5094.9  273.11  5165.5  278.08  5179.7  278.49  5193.9  279.93  5278.7  284.95
#Mann=7,-1,0
  4464.4   0.045       0  4501.2    0.07       0  4637.8     0.1       0
  4946.9    0.07       0  4986.3    0.05       0  4991.1    0.07       0
  5165.5    0.12       0
Bank Sta=4986.3,4991.1
Exp/Cntr=0.3,0.1

Type RM Length L Ch R = 1,16224,473,473,473
BEGIN DESCRIPTION:
BLACKJACK CREEK 34.0
END DESCRIPTION:
XS GIS Cut Line= 3
      2465375.02     13588424.98      2465720.77     13588075.31
      2465975.05     13587974.98
#Sta/Elev= 30
  4466.6  285.51  4554.9  280.29  4556.8  280.16  4671.6  273.50  4707.0  271.08
  4791.8  268.14  4810.6  266.64  4811.0  266.14  4815.2  266.14  4815.5  266.64
  4830.8  266.64  4844.6  266.64  4960.0  266.64  4980.8  266.64  5016.6  266.64
  5030.0  267.04  5054.4  269.52  5087.8  271.44  5102.6  272.16  5108.5  273.70
  5113.9  272.78  5132.9  275.20  5138.3  273.83  5156.4  276.03  5162.7  277.41
  5168.0  275.52  5177.9  276.13  5194.7  278.45  5199.4  279.46  5231.7  281.75
#Mann=11,-1,0
  4466.6   0.045       0  4554.9    0.07       0  4556.8    0.05       0
  4810.6    0.05       0  4815.5    0.05       0  4830.8    0.07       0
  4844.6     0.1       0  4960.0    0.07       0  4980.8     0.1       0
  5087.8    0.07       0  5194.7     0.1       0
Bank Sta=4810.6,4815.5
Exp/Cntr=0.3,0.1

Type RM Length L Ch R = 1,15751,387,387,387
BEGIN DESCRIPTION:
BLACKJACK CREEK 33.0
END DESCRIPTION:
XS GIS Cut Line= 3
      2465575.00     13588625.00      2465775.00     13588475.00
      2466175.01     13588074.99
#Sta/Elev= 30
  4746.0  282.80  4774.1  281.45  4817.9  278.64  4838.7  277.86  4853.3  276.73
  4882.5  275.45  4924.1  272.95  4958.9  270.24  4967.9  269.09  4992.9  267.14
  5007.7  266.64  5008.0  266.14  5012.2  266.14  5012.6  266.64  5037.4  266.64
  5208.1  266.64  5222.3  267.36  5250.6  270.44  5278.8  272.55  5293.0  273.12
  5307.1  274.65  5335.4  274.93  5351.6  275.58  5377.8  276.78  5384.9  277.43
  5448.5  280.10  5491.0  282.53  5533.4  284.16  5547.5  285.46  5561.7  286.22
#Mann=6,-1,0
  4746.0    0.07       0  4958.9    0.05       0  5007.7    0.05       0
  5012.6    0.05       0  5037.4   0.033       0  5351.6    0.07       0
Bank Sta=5007.7,5012.6
Exp/Cntr=0.3,0.1

Type RM Length L Ch R = 1,15364,538,538,538
BEGIN DESCRIPTION:
BLACKJACK CREEK 32.0
END DESCRIPTION:
XS GIS Cut Line= 4
      2465675.02     13588775.00      2465919.88     13588703.58
      2466050.61     13588608.61      2466350.16     13588314.00
#Sta/Elev= 30
  4577.9  280.26  4594.6  278.85  4633.3  277.18  4640.4  276.20  4666.8  274.58
  4730.1  271.28  4744.6  270.81  4772.5  273.83  4777.7  272.67  4805.9  274.98
  4811.1  274.29  4864.0  274.46  4866.3  266.42  4866.6  265.92  4870.8  265.92
  4871.2  266.42  4871.6  274.45  4885.3  274.43  4957.6  274.46  5038.7  274.22
  5078.0  273.73  5086.5  274.14  5092.1  273.79  5099.2  274.56  5113.3  273.11
  5141.6  268.89  5177.0  269.83  5205.3  271.49  5226.4  273.56  5414.7  282.85
#Mann=8,-1,0
  4577.9    0.07       0  4730.1    0.05       0  4866.3    0.05       0
  4871.2    0.05       0  4885.3   0.033       0  4957.6    0.07       0
  5038.7   0.033       0  5086.5    0.07       0
Bank Sta=4866.3,4871.2
Exp/Cntr=0.3,0.1

Type RM Length L Ch R = 1,14826,550,550,550
BEGIN DESCRIPTION:
BLACKJACK CREEK 31.0
END DESCRIPTION:
XS GIS Cut Line= 3
      2465975.00     13589275.00      2466375.00     13589025.00
      2466475.00     13588625.01
#Sta/Elev= 30
  4519.4  277.33  4649.1  268.74  4737.0  265.58  4752.3  264.45  4788.5  264.01
  4852.5  263.25  4867.9  262.40  4894.1  262.61  4941.0  261.51  4946.9  259.60
  4955.7  259.95  4962.2  259.52  4968.1  258.36  4977.5  257.74  4988.2  255.45
  4993.7  255.45  4998.9  254.77  4999.3  254.27  5003.6  254.27  5004.0  254.77
  5037.0  255.11  5050.4  255.43  5055.5  256.58  5083.9  259.33  5091.6  262.29
  5132.8  265.13  5156.0  266.07  5261.7  268.23  5366.8  272.45  5403.4  274.02
#Mann=7,-1,0
  4519.4    0.07       0  4788.5     0.1       0  4894.1    0.05       0
  4998.9    0.05       0  5004.0    0.05       0  5037.0    0.07       0
  5366.8    0.12       0
Bank Sta=4998.9,5004
Exp/Cntr=0.3,0.1

Type RM Length L Ch R = 1,14276,357,357,357
BEGIN DESCRIPTION:
X18247
END DESCRIPTION:
XS GIS Cut Line= 3
      2465991.73     13589587.85      2466755.64     13589445.48
      2467291.87     13589448.94
#Sta/Elev= 30
  4488.2  281.14  4586.9  275.74  4639.6  271.39  4691.2  268.61  4766.2  264.52
  4867.9  261.51  4898.4  259.50  4928.9  258.63  4966.1  253.18  4971.2  251.16
  4987.1  250.64  4987.6  250.14  4992.8  250.64  5010.3  251.91  5030.7  250.83
  5051.0  252.58  5071.3  251.17  5101.9  251.43  5122.2  252.43  5129.4  253.58
  5152.7  254.10  5162.9  255.34  5173.1  258.27  5193.4  260.74  5268.8  260.86
  5394.6  262.75  5574.6  268.83  5614.6  271.09  5694.6  273.92  5801.5  274.67
#Mann=5,-1,0
  4488.2    0.05       0  4691.2     0.1       0  4987.1    0.05       0
  4992.8     0.1       0  5268.8    0.05       0
Bank Sta=4987.1,4992.8
Exp/Cntr=0.3,0.1

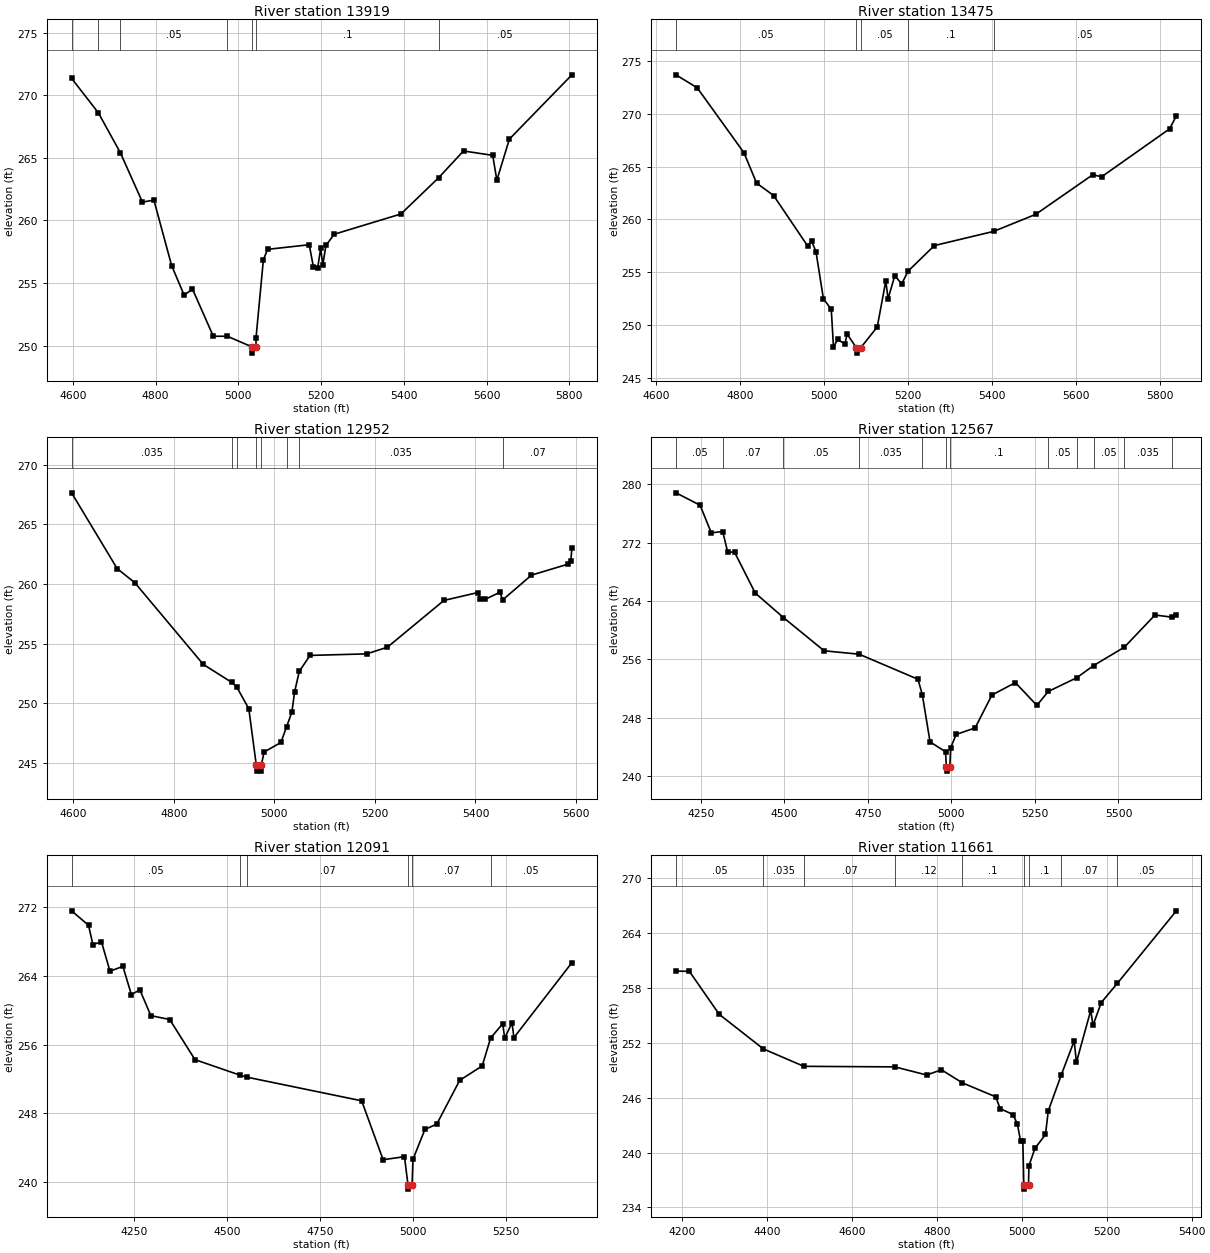
Type RM Length L Ch R = 1,13919,444,444,444
BEGIN DESCRIPTION:
BLACKJACK CREEK 30.0
END DESCRIPTION:
XS GIS Cut Line= 3
      2466175.00     13589875.00      2466575.00     13589825.00
      2467374.96     13589925.00
#Sta/Elev= 30
  4596.8  271.37  4661.6  268.61  4714.7  265.42  4768.1  261.47  4795.8  261.63
  4838.7  256.39  4868.9  254.03  4889.1  254.51  4939.4  250.74  4973.3  250.74
  5032.9  249.89  5033.4  249.39  5042.5  249.89  5042.7  250.64  5060.4  256.85
  5070.5  257.69  5171.2  258.06  5181.3  256.28  5191.4  256.16  5198.9  257.77
  5204.0  256.44  5211.5  258.00  5231.7  258.90  5392.9  260.52  5484.0  263.42
  5544.1  265.56  5614.7  265.21  5624.7  263.22  5655.0  266.51  5806.1  271.65
#Mann=7,-1,0
  4596.8    0.05       0  4661.6    0.07       0  4714.7    0.05       0
  4973.3     0.1       0  5032.9    0.05       0  5042.5     0.1       0
  5484.0    0.05       0
Bank Sta=5032.9,5042.5
Exp/Cntr=0.3,0.1

Type RM Length L Ch R = 1,13475,523,523,523
BEGIN DESCRIPTION:
BLACKJACK CREEK 29.0
END DESCRIPTION:
XS GIS Cut Line= 3
      2466174.97     13590175.00      2466525.00     13590225.00
      2467324.96     13589975.01
#Sta/Elev= 30
  4646.9  273.69  4697.4  272.46  4808.6  266.32  4838.9  263.43  4879.3  262.26
  4960.1  257.50  4970.2  257.92  4980.3  256.93  4998.0  252.48  5016.7  251.48
  5022.0  247.89  5031.9  248.63  5049.2  248.18  5054.4  249.14  5076.7  247.83
  5077.2  247.33  5086.7  247.83  5126.2  249.81  5146.6  254.17  5151.9  252.48
  5168.1  254.67  5184.4  253.88  5199.7  255.10  5262.4  257.52  5403.4  258.86
  5503.4  260.47  5639.6  264.23  5660.5  264.03  5822.4  268.57  5838.6  269.80
#Mann=5,-1,0
  4646.9    0.05       0  5076.7    0.05       0  5086.7    0.05       0
  5199.7     0.1       0  5403.4    0.05       0
Bank Sta=5076.7,5086.7
Exp/Cntr=0.3,0.1

Type RM Length L Ch R = 1,12952,385,385,385
BEGIN DESCRIPTION:
BLACKJACK CREEK 28.0
END DESCRIPTION:
XS GIS Cut Line= 3
      2466324.97     13590625.00      2466738.28     13590674.65
      2467303.48     13590549.82
#Sta/Elev= 30
  4596.7  267.64  4687.4  261.29  4722.6  260.10  4858.6  253.26  4914.9  251.76
  4925.0  251.38  4949.2  249.54  4964.1  244.81  4964.6  244.31  4973.7  244.31
  4974.2  244.81  4979.5  245.91  5013.0  246.71  5024.5  248.04  5034.9  249.27
  5040.3  250.95  5049.6  252.68  5071.1  254.01  5183.7  254.14  5224.9  254.70
  5337.3  258.62  5404.7  259.28  5409.8  258.71  5419.3  258.71  5448.4  259.30
  5454.3  258.67  5511.4  260.74  5583.1  261.65  5589.6  261.95  5591.8  263.02
#Mann=8,-1,0
  4596.7   0.035       0  4914.9    0.05       0  4925.0   0.035       0
  4964.1   0.035       0  4974.2   0.035       0  5024.5     0.1       0
  5049.6   0.035       0  5454.3    0.07       0
Bank Sta=4964.1,4974.2
Exp/Cntr=0.3,0.1

Type RM Length L Ch R = 1,12567,476,476,476
BEGIN DESCRIPTION:
BLACKJACK CREEK 27.0
END DESCRIPTION:
XS GIS Cut Line= 3
      2466025.01     13590825.00      2466825.00     13591025.00
      2467325.01     13590574.99
#Sta/Elev= 30
  4176.0  278.83  4248.1  277.13  4281.6  273.34  4315.8  273.52  4330.6  270.71
  4351.2  270.69  4413.1  265.08  4497.4  261.72  4619.2  257.16  4724.2  256.69
  4900.1  253.25  4913.1  251.14  4936.2  244.66  4982.6  243.31  4985.2  241.15
  4985.7  240.65  4995.3  241.15  4998.0  243.88  5014.4  245.68  5071.2  246.58
  5121.3  251.09  5191.6  252.79  5255.9  249.67  5290.0  251.58  5374.8  253.45
  5425.8  255.14  5517.6  257.65  5609.4  262.07  5660.4  261.77  5673.3  262.05
#Mann=12,-1,0
  4176.0    0.05       0  4315.8    0.07       0  4497.4    0.05       0
  4724.2   0.035       0  4913.1     0.1       0  4985.2    0.05       0
  4995.3     0.1       0  5290.0    0.05       0  5374.8     0.1       0
  5425.8    0.05       0  5517.6   0.035       0  5660.4    0.07       0
Bank Sta=4985.2,4995.3
Exp/Cntr=0.3,0.1

Type RM Length L Ch R = 1,12091,430,430,430
BEGIN DESCRIPTION:
BLACKJACK CREEK 26.0
END DESCRIPTION:
XS GIS Cut Line= 3
      2466424.98     13591575.01      2467225.00     13591125.00
      2467625.00     13590975.00
#Sta/Elev= 30
  4081.8  271.56  4127.4  269.88  4139.2  267.62  4162.1  267.97  4185.1  264.53
  4219.8  265.10  4242.5  261.82  4265.4  262.36  4295.0  259.36  4345.7  258.91
  4413.6  254.24  4534.2  252.44  4553.4  252.20  4861.7  249.45  4919.4  242.59
  4976.8  242.95  4986.2  239.67  4986.7  239.17  4997.2  239.67  4999.7  242.65
  5031.7  246.11  5063.8  246.75  5125.2  251.83  5185.7  253.51  5208.4  256.76
  5240.9  258.42  5246.2  256.74  5265.8  258.52  5271.1  256.81  5426.9  265.53
#Mann=6,-1,0
  4081.8    0.05       0  4534.2     0.1       0  4553.4    0.07       0
  4986.2    0.05       0  4997.2    0.07       0  5208.4    0.05       0
Bank Sta=4986.2,4997.2
Exp/Cntr=0.3,0.1

Type RM Length L Ch R = 1,11661,488,488,488
BEGIN DESCRIPTION:
BLACKJACK CREEK 25.0
END DESCRIPTION:
XS GIS Cut Line= 3
      2466624.97     13591625.01      2467425.00     13591475.00
      2467775.02     13591374.99
#Sta/Elev= 30
  4186.0  259.86  4217.4  259.84  4287.8  255.13  4391.6  251.35  4486.9  249.44
  4701.3  249.38  4776.1  248.49  4810.9  249.06  4860.3  247.63  4938.9  246.10
  4949.1  244.81  4979.6  244.16  4989.8  243.11  4997.4  241.23  5002.6  241.23
  5004.8  236.50  5005.3  236.00  5015.9  236.50  5016.9  238.56  5031.2  240.47
  5055.9  241.98  5062.4  244.56  5092.9  248.48  5123.5  252.23  5128.7  249.88
  5162.5  255.57  5167.7  253.92  5187.2  256.42  5225.4  258.54  5364.0  266.46
#Mann=9,-1,0
  4186.0    0.05       0  4391.6   0.035       0  4486.9    0.07       0
  4701.3    0.12       0  4860.3     0.1       0  5004.8    0.05       0
  5015.9     0.1       0  5092.9    0.07       0  5225.4    0.05       0
Bank Sta=5004.8,5015.9
Exp/Cntr=0.3,0.1

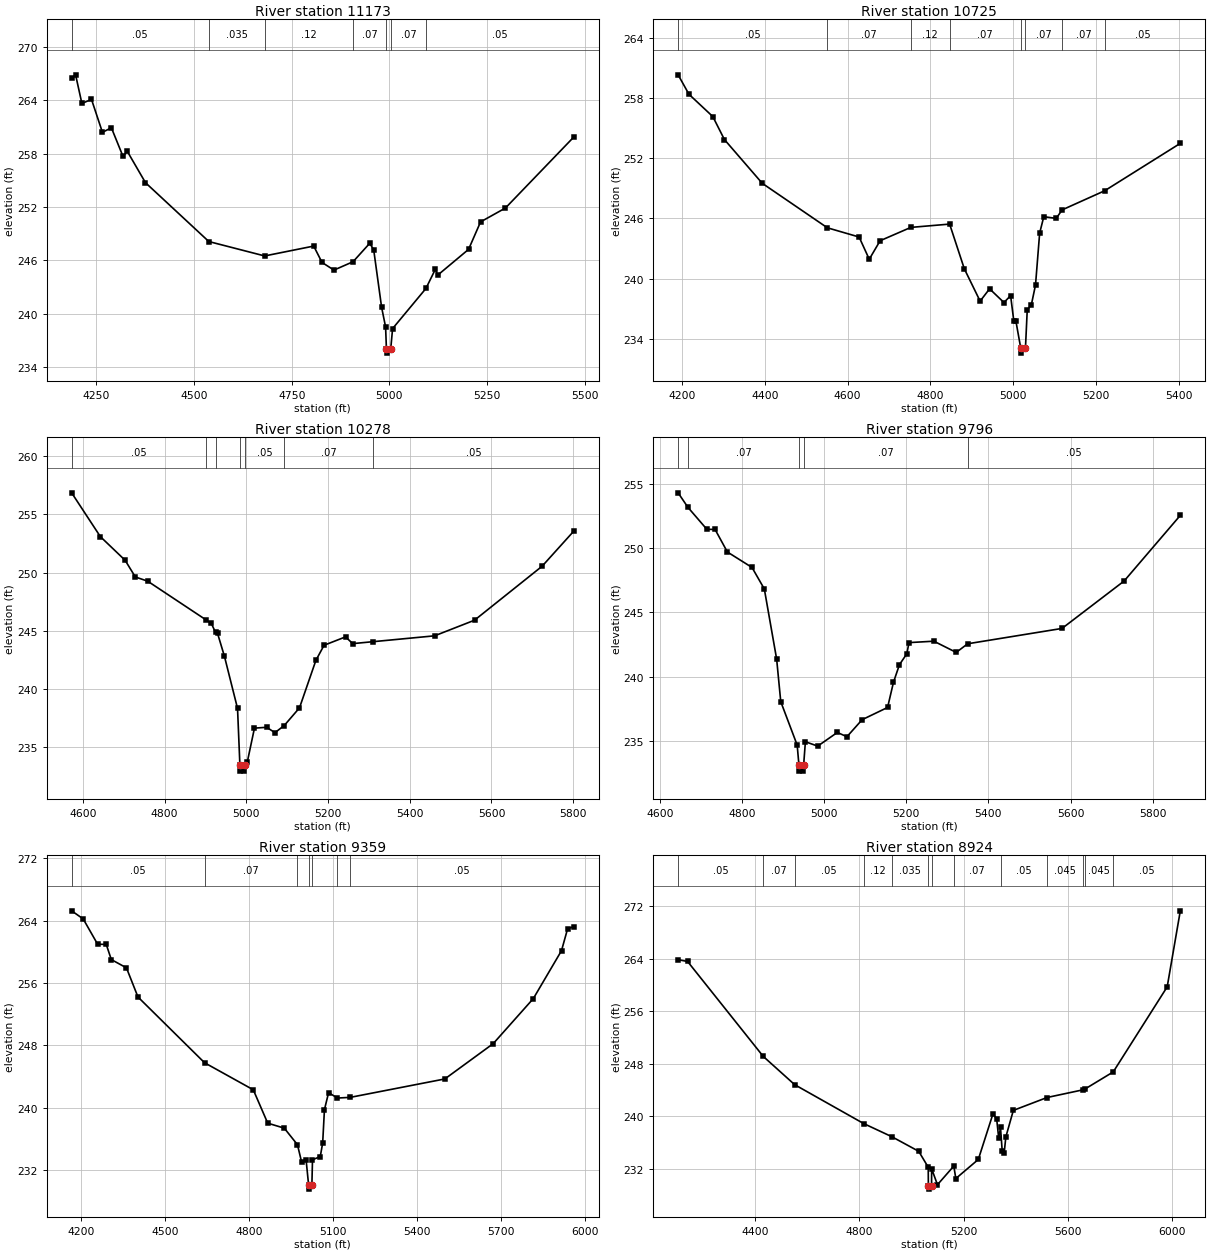
Type RM Length L Ch R = 1,11173,448,448,448
BEGIN DESCRIPTION:
BLACKJACK CREEK 24.0
END DESCRIPTION:
XS GIS Cut Line= 3
      2466525.04     13591775.01      2467325.00     13591925.00
      2467725.00     13591675.00
#Sta/Elev= 30
  4186.5  266.47  4196.6  266.87  4212.7  263.65  4237.3  264.11  4265.3  260.40
  4288.2  260.92  4317.9  257.70  4328.9  258.27  4375.5  254.74  4537.7  248.12
  4680.6  246.50  4806.2  247.61  4827.4  245.77  4858.0  244.91  4906.9  245.85
  4949.5  247.92  4959.7  247.21  4980.0  240.72  4990.2  238.51  4992.3  236.07
  4992.8  235.57  5003.4  236.07  5008.1  238.33  5093.4  242.84  5117.7  245.01
  5123.6  244.34  5202.6  247.24  5233.3  250.33  5297.0  251.89  5472.1  259.88
#Mann=7,-1,0
  4186.5    0.05       0  4537.7   0.035       0  4680.6    0.12       0
  4906.9    0.07       0  4992.3    0.05       0  5003.4    0.07       0
  5093.4    0.05       0
Bank Sta=4992.3,5003.4
Exp/Cntr=0.3,0.1

Type RM Length L Ch R = 1,10725,447,447,447
BEGIN DESCRIPTION:
BLACKJACK CREEK 23.0
END DESCRIPTION:
XS GIS Cut Line= 3
      2466575.04     13592175.01      2467375.00     13592325.00
      2467775.00     13592325.00
#Sta/Elev= 30
  4190.3  260.34  4216.5  258.40  4274.2  256.17  4302.2  253.88  4393.7  249.51
  4551.1  245.07  4627.8  244.15  4652.3  241.93  4678.6  243.78  4752.8  245.11
  4846.6  245.44  4882.1  240.98  4920.3  237.75  4943.2  238.98  4977.9  237.61
  4994.0  238.30  5001.7  235.78  5006.7  235.78  5018.5  233.06  5019.0  232.56
  5029.9  233.06  5034.2  236.87  5044.2  237.40  5054.2  239.36  5064.2  244.54
  5074.2  246.18  5104.2  246.01  5118.6  246.86  5221.5  248.77  5404.2  253.50
#Mann=8,-1,0
  4190.3    0.05       0  4551.1    0.07       0  4752.8    0.12       0
  4846.6    0.07       0  5018.5    0.05       0  5029.9    0.07       0
  5118.6    0.07       0  5221.5    0.05       0
Bank Sta=5018.5,5029.9
Exp/Cntr=0.3,0.1

Type RM Length L Ch R = 1,10278,482,482,482
BEGIN DESCRIPTION:
BLACKJACK CREEK 22.0
END DESCRIPTION:
XS GIS Cut Line= 3
      2466624.97     13592424.99      2467025.00     13592575.00
      2467825.00     13592525.00
#Sta/Elev= 30
  4572.8  256.84  4643.1  253.08  4703.7  251.05  4728.6  249.62  4758.8  249.26
  4901.5  245.94  4914.6  245.63  4924.8  244.87  4929.7  244.79  4946.6  242.82
  4978.7  238.34  4984.5  233.46  4985.0  232.96  4995.5  232.96  4996.0  233.46
  5002.5  233.73  5020.1  236.65  5050.1  236.72  5070.2  236.26  5092.9  236.87
  5130.3  238.39  5170.4  242.46  5190.4  243.76  5243.0  244.48  5260.5  243.90
  5311.1  244.07  5460.9  244.57  5558.6  245.91  5723.9  250.54  5801.6  253.56
#Mann=7,-1,0
  4572.8    0.05       0  4901.5    0.07       0  4924.8    0.05       0
  4984.5    0.05       0  4996.0    0.05       0  5092.9    0.07       0
  5311.1    0.05       0
Bank Sta=4984.5,4996
Exp/Cntr=0.3,0.1

Type RM Length L Ch R = 1,9796,437,437,437
BEGIN DESCRIPTION:
BLACKJACK CREEK 21.0
END DESCRIPTION:
XS GIS Cut Line= 3
      2466675.01     13592975.00      2467025.00     13592975.00
      2467825.00     13592625.00
#Sta/Elev= 30
  4644.2  254.28  4668.2  253.15  4714.2  251.45  4734.2  251.44  4764.2  249.69
  4824.2  248.49  4854.2  246.82  4884.2  241.38  4894.2  238.08  4934.2  234.71
  4938.4  233.19  4938.9  232.69  4949.5  232.69  4950.0  233.19  4954.2  234.97
  4984.2  234.63  5032.0  235.69  5055.4  235.36  5092.4  236.68  5154.4  237.63
  5168.8  239.59  5183.3  240.95  5201.2  241.79  5206.6  242.66  5267.1  242.77
  5321.6  241.90  5349.5  242.57  5579.3  243.76  5730.6  247.44  5867.4  252.53
#Mann=5,-1,0
  4644.2    0.05       0  4668.2    0.07       0  4938.4    0.05       0
  4950.0    0.07       0  5349.5    0.05       0
Bank Sta=4938.4,4950
Exp/Cntr=0.3,0.1

Type RM Length L Ch R = 1,9359,435,435,435
BEGIN DESCRIPTION:
BLACKJACK CREEK 20.0
END DESCRIPTION:
XS GIS Cut Line= 3
      2466424.96     13593024.99      2467225.00     13593225.00
      2468025.01     13592674.99
#Sta/Elev= 30
  4166.1  265.25  4207.4  264.21  4258.9  260.97  4289.8  260.94  4307.9  259.00
  4362.0  257.94  4403.2  254.20  4641.2  245.77  4815.5  242.30  4867.1  238.02
  4926.3  237.38  4973.4  235.26  4988.2  233.04  5004.3  233.32  5013.4  230.06
  5013.9  229.56  5025.0  230.06  5027.2  233.32  5055.0  233.74  5063.6  235.48
  5069.9  239.75  5084.8  241.94  5116.3  241.24  5162.6  241.33  5500.4  243.69
  5673.4  248.22  5816.8  254.00  5917.5  260.14  5939.2  262.94  5961.6  263.23
#Mann=7,-1,0
  4166.1    0.05       0  4641.2    0.07       0  4973.4    0.12       0
  5013.4    0.05       0  5025.0    0.12       0  5116.3    0.07       0
  5162.6    0.05       0
Bank Sta=5013.4,5025
Exp/Cntr=0.3,0.1

Type RM Length L Ch R = 1,8924,469,469,469
BEGIN DESCRIPTION:
BLACKJACK CREEK 19.0
END DESCRIPTION:
XS GIS Cut Line= 3
      2466425.03     13593225.02      2467225.00     13593625.00
      2468025.02     13594275.02
#Sta/Elev= 30
  4105.5  263.83  4141.8  263.56  4431.8  249.13  4552.3  244.83  4816.8  238.92
  4925.3  236.91  5027.9  234.70  5064.3  232.28  5064.9  229.45  5065.4  228.95
  5077.1  229.45  5077.4  232.05  5099.7  229.62  5162.4  232.46  5170.1  230.56
  5256.3  233.46  5312.3  240.37  5326.7  239.64  5334.6  236.65  5341.4  238.32
  5347.8  234.81  5355.5  234.45  5361.9  236.89  5390.6  240.92  5519.9  242.88
  5657.9  244.05  5665.3  244.17  5773.6  246.77  5980.4  259.70  6030.7  271.26
#Mann=13,-1,0
  4105.5    0.05       0  4431.8    0.07       0  4552.3    0.05       0
  4816.8    0.12       0  4925.3   0.035       0  5064.9   0.035       0
  5077.1   0.035       0  5162.4    0.07       0  5341.4    0.05       0
  5519.9   0.045       0  5657.9    0.05       0  5665.3   0.045       0
  5773.6    0.05       0
Bank Sta=5064.9,5077.1
Exp/Cntr=0.3,0.1