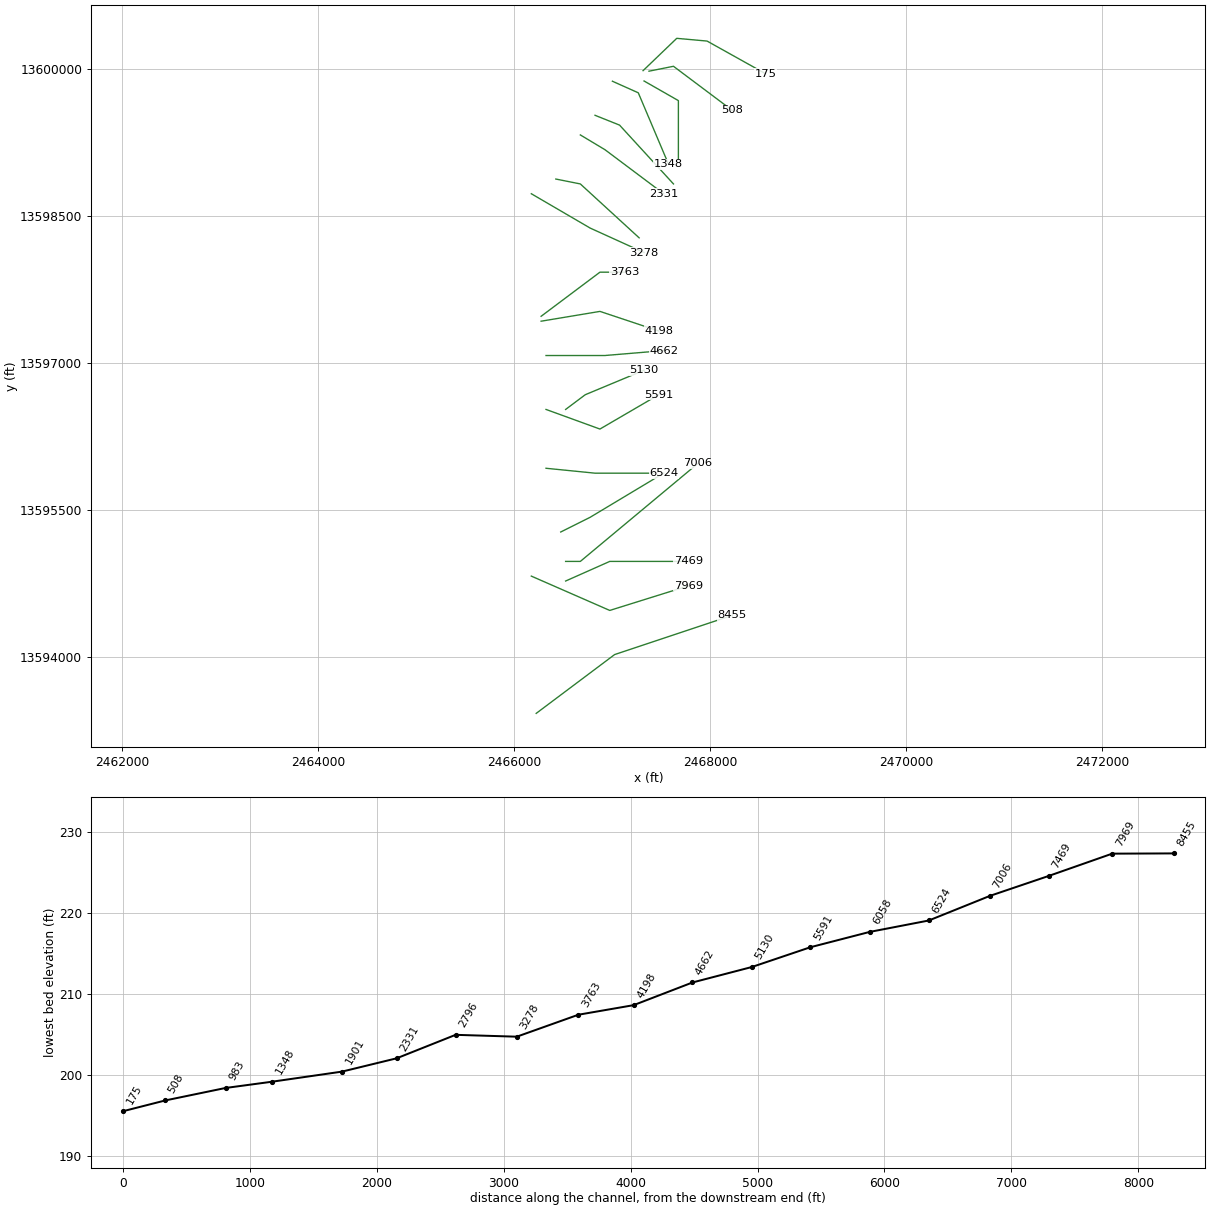
HEC-RAS study BLACKJACK CREEK.prj: BLACKJACK CREEK Base Level Engineering

--- BLACKJACK CREEK.g01 (geometry) --- (continued)

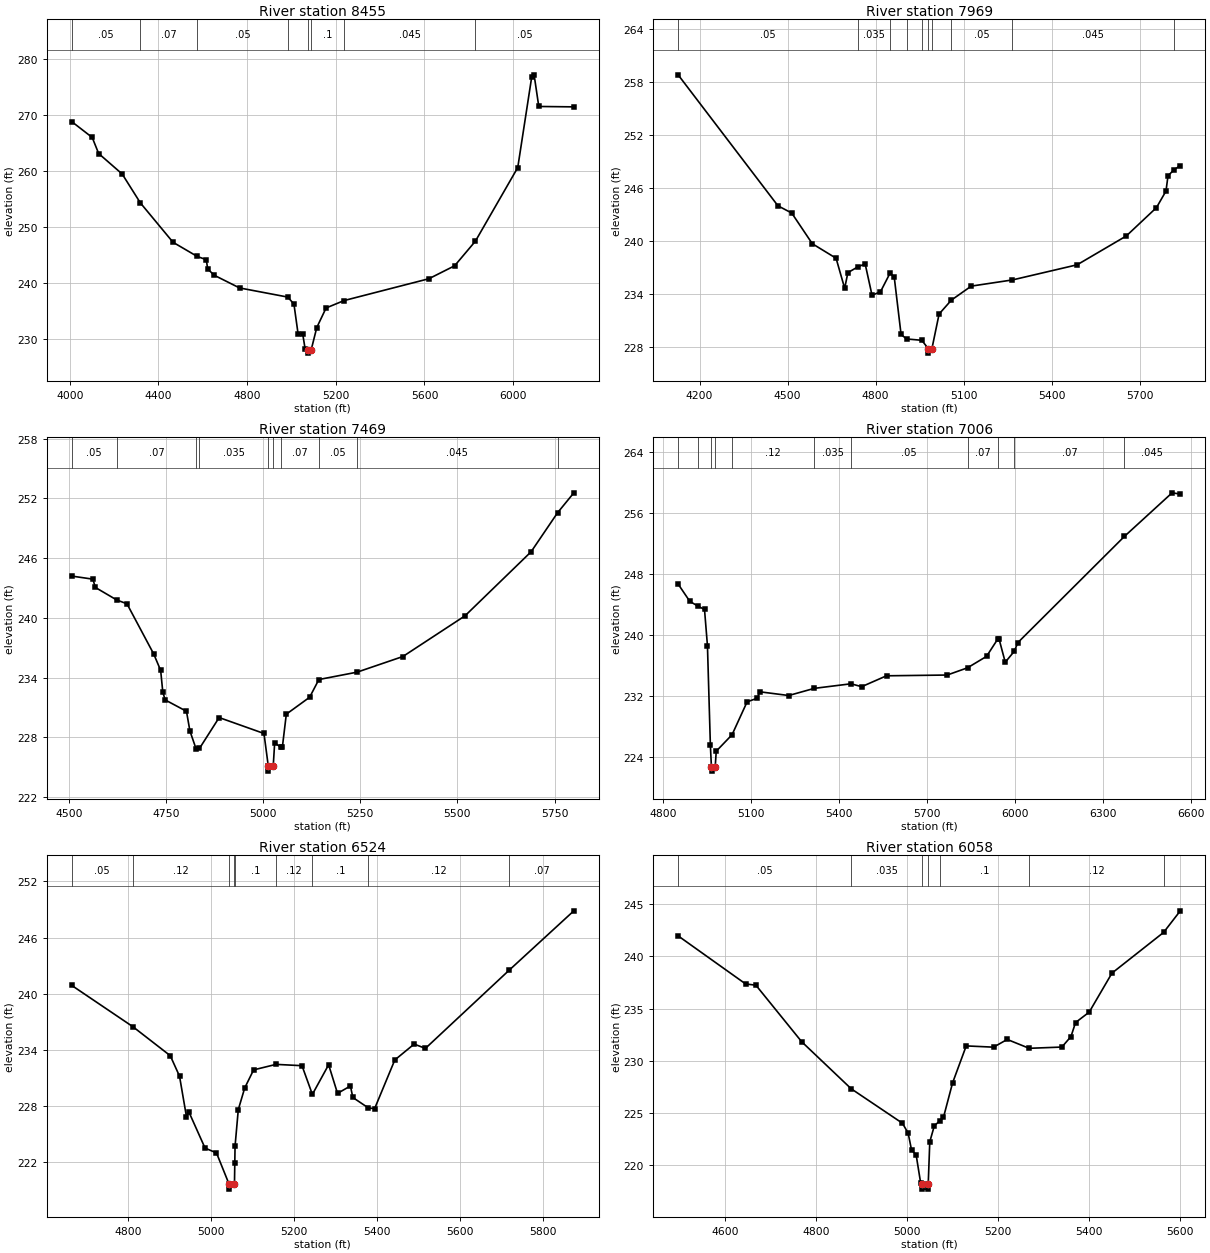
Type RM Length L Ch R = 1,8455,486,486,486
BEGIN DESCRIPTION:
BLACKJACK CREEK 18.0
END DESCRIPTION:
XS GIS Cut Line= 3
      2466225.03     13593425.03      2467025.00     13594025.00
      2468225.03     13594425.01
#Sta/Elev= 30
  4008.7  268.87  4101.4  266.02  4130.5  263.14  4236.8  259.46  4318.7  254.29
  4465.9  247.24  4575.2  244.70  4615.9  244.12  4622.2  242.47  4651.4  241.34
  4765.9  239.06  4983.6  237.42  5011.3  236.16  5029.7  230.89  5050.8  230.81
  5061.4  228.20  5076.3  227.88  5076.8  227.38  5088.5  227.88  5114.1  231.95
  5156.2  235.47  5237.6  236.80  5620.0  240.71  5736.0  243.03  5829.5  247.43
  6020.6  260.62  6083.8  276.91  6094.4  277.24  6115.5  271.57  6273.6  271.50
#Mann=8,-1,0
  4008.7    0.05       0  4318.7    0.07       0  4575.2    0.05       0
  4983.6     0.1       0  5076.3    0.05       0  5088.5     0.1       0
  5237.6   0.045       0  5829.5    0.05       0
Bank Sta=5076.3,5088.5
Exp/Cntr=0.3,0.1

Type RM Length L Ch R = 1,7969,500,500,500
BEGIN DESCRIPTION:
BLACKJACK CREEK 17.0
END DESCRIPTION:
XS GIS Cut Line= 3
      2466175.00     13594825.00      2466975.00     13594475.00
      2467775.04     13594725.01
#Sta/Elev= 30
  4126.8  258.79  4467.1  243.99  4513.9  243.18  4584.1  239.71  4665.1  238.07
  4694.4  234.67  4705.3  236.44  4739.9  237.11  4764.2  237.43  4787.6  233.89
  4816.4  234.28  4848.6  236.36  4863.2  235.97  4886.6  229.46  4905.3  228.95
  4957.3  228.80  4979.4  227.85  4979.9  227.35  4991.7  227.85  5016.2  231.77
  5058.1  233.34  5125.7  234.92  5266.3  235.62  5486.7  237.33  5654.3  240.59
  5757.0  243.79  5789.4  245.66  5796.3  247.39  5816.8  248.06  5838.2  248.54
#Mann=10,-1,0
  4126.8    0.05       0  4739.9   0.035       0  4848.6    0.07       0
  4905.3   0.035       0  4957.3     0.1       0  4979.4    0.05       0
  4991.7     0.1       0  5058.1    0.05       0  5266.3   0.045       0
  5816.8    0.05       0
Bank Sta=4979.4,4991.7
Exp/Cntr=0.3,0.1

Type RM Length L Ch R = 1,7469,463,463,463
BEGIN DESCRIPTION:
BLACKJACK CREEK 16.0
END DESCRIPTION:
XS GIS Cut Line= 3
      2466524.98     13594774.99      2466975.00     13594975.00
      2467775.04     13594975.00
#Sta/Elev= 30
  4507.1  244.19  4561.8  243.88  4568.0  243.05  4623.5  241.78  4649.4  241.41
  4718.5  236.35  4736.2  234.71  4741.7  232.53  4747.9  231.75  4802.6  230.61
  4811.5  228.63  4827.5  226.82  4836.1  226.88  4886.7  229.98  5002.1  228.38
  5013.2  225.10  5013.7  224.60  5025.9  225.10  5029.6  227.44  5045.1  227.01
  5049.6  227.07  5059.6  230.32  5119.6  232.02  5143.4  233.80  5241.8  234.54
  5359.6  236.11  5519.6  240.20  5689.6  246.63  5757.9  250.56  5799.6  252.55
#Mann=10,-1,0
  4507.1    0.05       0  4623.5    0.07       0  4827.5    0.12       0
  4836.1   0.035       0  5013.2   0.035       0  5025.9   0.035       0
  5045.1    0.07       0  5143.4    0.05       0  5241.8   0.045       0
  5757.9    0.05       0
Bank Sta=5013.2,5025.9
Exp/Cntr=0.3,0.1

Type RM Length L Ch R = 1,7006,482,482,482
BEGIN DESCRIPTION:
BLACKJACK CREEK 15.0
END DESCRIPTION:
XS GIS Cut Line= 3
      2466525.01     13594975.00      2466675.00     13594975.00
      2467874.97     13595974.98
#Sta/Elev= 30
  4850.6  246.71  4890.6  244.43  4919.2  243.79  4940.6  243.37  4950.6  238.61
  4960.6  225.52  4964.2  222.64  4964.7  222.14  4976.9  222.64  4980.6  224.76
  5034.5  226.92  5085.8  231.24  5121.0  231.72  5128.8  232.56  5227.7  232.07
  5314.8  233.01  5439.9  233.61  5476.4  233.23  5561.0  234.66  5767.9  234.76
  5837.2  235.71  5902.0  237.21  5940.2  239.48  5945.0  239.45  5965.8  236.44
  5996.6  237.88  6008.8  239.02  6372.2  252.97  6534.6  258.69  6562.6  258.53
#Mann=11,-1,0
  4850.6    0.05       0  4919.2   0.035       0  4964.2   0.035       0
  4976.9   0.035       0  5034.5    0.12       0  5314.8   0.035       0
  5439.9    0.05       0  5837.2    0.07       0  5940.2    0.12       0
  5996.6    0.07       0  6372.2   0.045       0
Bank Sta=4964.2,4976.9
Exp/Cntr=0.3,0.1

Type RM Length L Ch R = 1,6524,466,466,466
BEGIN DESCRIPTION:
BLACKJACK CREEK 14.0
END DESCRIPTION:
XS GIS Cut Line= 3
      2466475.01     13595275.00      2466775.00     13595425.00
      2467524.96     13595874.98
#Sta/Elev= 30
  4664.6  240.89  4812.1  236.47  4902.2  233.37  4924.5  231.18  4941.3  226.83
  4946.9  227.37  4986.0  223.49  5013.6  222.97  5044.2  219.60  5044.7  219.10
  5056.9  219.60  5057.7  221.94  5058.3  223.69  5066.1  227.60  5081.6  229.92
  5103.0  231.85  5157.1  232.44  5219.6  232.30  5244.6  229.23  5283.8  232.40
  5305.2  229.34  5336.3  230.13  5342.1  228.90  5379.6  227.78  5394.6  227.71
  5443.2  232.91  5489.8  234.61  5517.0  234.15  5718.0  242.48  5874.6  248.86
#Mann=9,-1,0
  4664.6    0.05       0  4812.1    0.12       0  5044.2    0.05       0
  5056.9    0.12       0  5057.7     0.1       0  5157.1    0.12       0
  5244.6     0.1       0  5379.6    0.12       0  5718.0    0.07       0
Bank Sta=5044.2,5056.9
Exp/Cntr=0.3,0.1

Type RM Length L Ch R = 1,6058,467,467,467
BEGIN DESCRIPTION:
BLACKJACK CREEK 13.0
END DESCRIPTION:
XS GIS Cut Line= 3
      2466325.00     13595925.00      2466825.00     13595875.00
      2467425.01     13595875.00
#Sta/Elev= 30
  4497.5  241.97  4645.7  237.36  4668.3  237.24  4768.8  231.82  4877.5  227.31
  4989.9  224.01  5002.5  223.06  5010.0  221.43  5020.0  220.99  5030.0  218.27
  5033.4  218.19  5033.9  217.69  5046.1  217.69  5046.6  218.19  5050.0  222.23
  5060.0  223.76  5071.5  224.22  5080.0  224.56  5100.0  227.87  5130.0  231.42
  5190.0  231.30  5220.0  232.04  5268.2  231.19  5340.0  231.31  5360.0  232.32
  5370.0  233.66  5400.0  234.66  5450.0  238.40  5563.3  242.30  5600.0  244.37
#Mann=7,-1,0
  4497.5    0.05       0  4877.5   0.035       0  5033.4   0.035       0
  5046.6   0.035       0  5071.5     0.1       0  5268.2    0.12       0
  5563.3    0.07       0
Bank Sta=5033.4,5046.6
Exp/Cntr=0.3,0.1

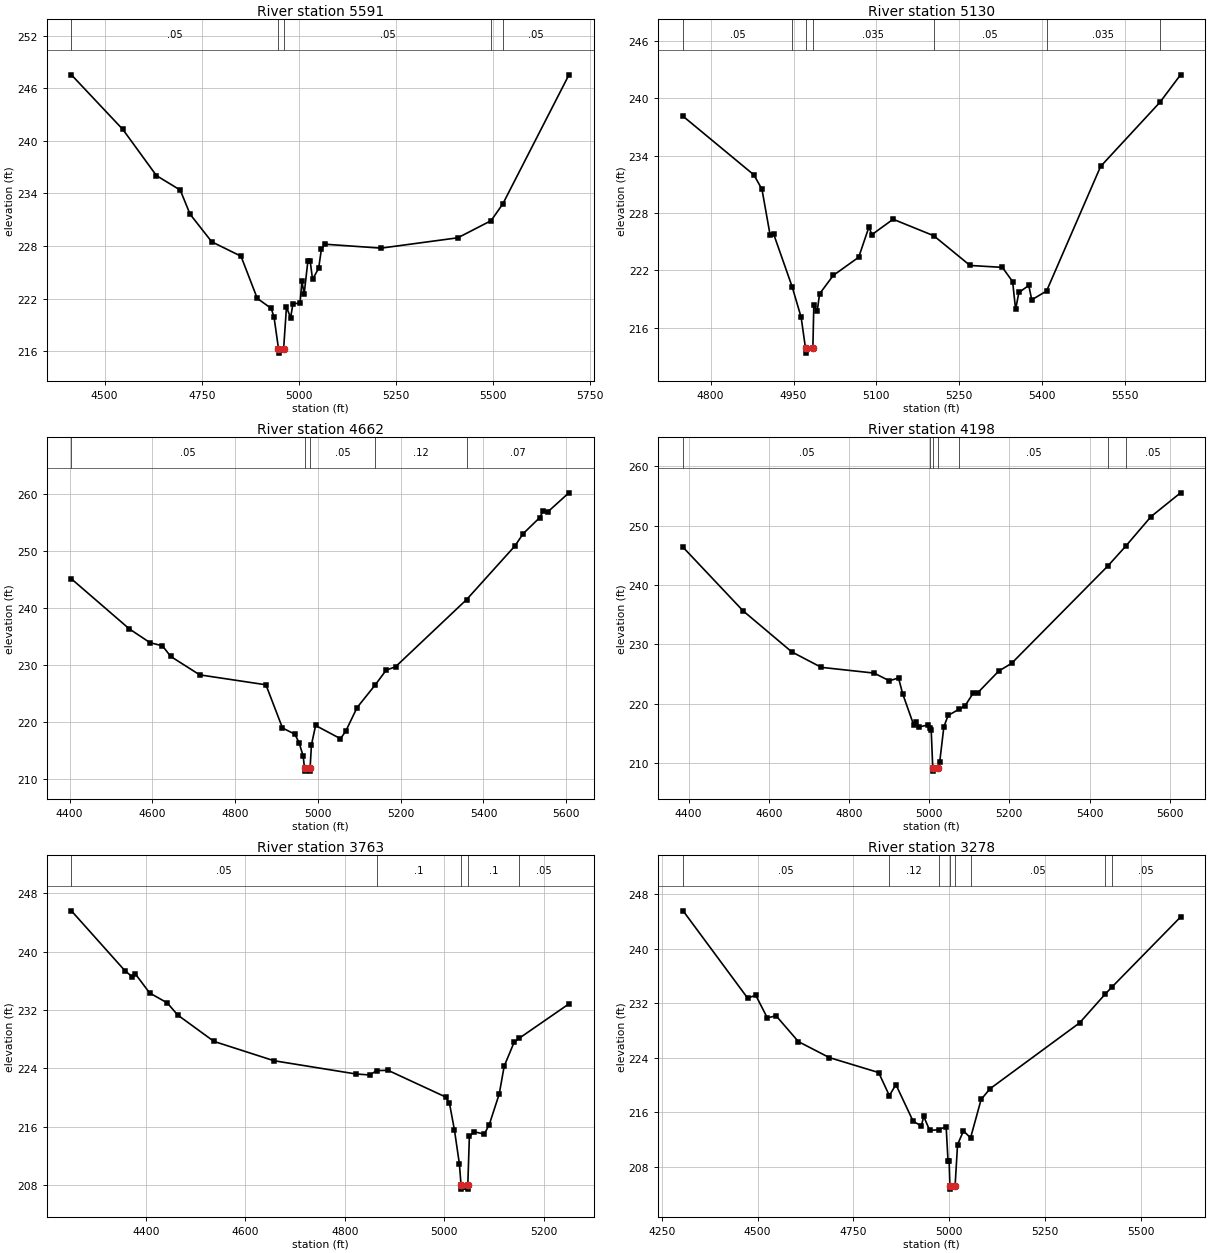
Type RM Length L Ch R = 1,5591,461,461,461
BEGIN DESCRIPTION:
BLACKJACK CREEK 12.0
END DESCRIPTION:
XS GIS Cut Line= 3
      2466324.98     13596525.01      2466875.00     13596325.00
      2467475.02     13596675.01
#Sta/Elev= 30
  4414.7  247.53  4547.1  241.30  4633.5  236.04  4694.7  234.39  4720.0  231.64
  4775.8  228.49  4851.0  226.85  4892.9  222.04  4928.8  220.90  4936.1  219.88
  4947.5  216.30  4948.0  215.80  4960.7  216.30  4968.0  221.04  4978.7  219.84
  4984.7  221.44  5002.8  221.49  5007.8  223.97  5013.6  222.55  5023.1  226.31
  5028.9  226.34  5035.1  224.21  5050.8  225.47  5057.8  227.62  5066.5  228.22
  5211.2  227.77  5408.9  228.95  5494.4  230.90  5524.6  232.81  5694.6  247.51
#Mann=5,-1,0
  4414.7    0.05       0  4947.5    0.05       0  4960.7    0.05       0
  5494.4   0.035       0  5524.6    0.05       0
Bank Sta=4947.5,4960.7
Exp/Cntr=0.3,0.1

Type RM Length L Ch R = 1,5130,468,468,468
BEGIN DESCRIPTION:
BLACKJACK CREEK 11.0
END DESCRIPTION:
XS GIS Cut Line= 3
      2466524.98     13596524.98      2466725.00     13596675.00
      2467324.97     13596924.99
#Sta/Elev= 30
  4750.2  238.11  4878.4  231.98  4892.9  230.48  4907.5  225.75  4913.8  225.84
  4947.6  220.28  4963.8  217.10  4971.7  213.86  4972.2  213.36  4985.0  213.86
  4986.7  218.37  4992.9  217.76  4997.1  219.55  5021.9  221.48  5067.9  223.38
  5086.4  226.53  5091.8  225.74  5130.2  227.35  5203.6  225.63  5269.4  222.52
  5327.9  222.32  5346.4  220.83  5351.8  217.92  5357.7  219.70  5375.6  220.43
  5381.0  218.93  5407.8  219.85  5505.6  232.87  5612.9  239.57  5650.2  242.44
#Mann=7,-1,0
  4750.2    0.05       0  4947.6   0.035       0  4971.7   0.035       0
  4985.0   0.035       0  5203.6    0.05       0  5407.8   0.035       0
  5612.9    0.12       0
Bank Sta=4971.7,4985
Exp/Cntr=0.3,0.1

Type RM Length L Ch R = 1,4662,464,464,464
BEGIN DESCRIPTION:
BLACKJACK CREEK 10.0
END DESCRIPTION:
XS GIS Cut Line= 3
      2466325.03     13597075.00      2466925.00     13597075.00
      2467524.95     13597125.00
#Sta/Elev= 30
  4404.3  245.10  4544.3  236.34  4594.3  233.93  4624.3  233.38  4644.3  231.52
  4714.3  228.30  4874.3  226.56  4914.3  219.00  4944.3  217.91  4954.3  216.44
  4964.3  214.08  4967.6  211.95  4968.1  211.45  4980.5  211.45  4981.0  211.95
  4984.3  216.05  4994.3  219.44  5054.4  217.13  5067.0  218.42  5094.6  222.58
  5138.5  226.55  5164.8  229.12  5187.4  229.71  5359.1  241.47  5475.9  250.86
  5496.0  253.02  5536.1  255.84  5543.6  256.93  5556.2  256.88  5606.3  260.16
#Mann=5,-1,0
  4404.3    0.05       0  4967.6    0.05       0  4981.0    0.05       0
  5138.5    0.12       0  5359.1    0.07       0
Bank Sta=4967.6,4981
Exp/Cntr=0.3,0.1

Type RM Length L Ch R = 1,4198,435,435,435
BEGIN DESCRIPTION:
BLACKJACK CREEK 9.0
END DESCRIPTION:
XS GIS Cut Line= 3
      2466274.99     13597425.00      2466875.00     13597525.00
      2467474.96     13597325.01
#Sta/Elev= 30
  4386.3  246.37  4535.8  235.67  4657.5  228.74  4731.0  226.14  4862.8  225.17
  4900.8  223.87  4923.6  224.36  4933.8  221.72  4961.6  216.40  4966.7  216.98
  4974.3  216.08  4997.2  216.43  5002.5  215.91  5005.1  215.65  5009.0  209.15
  5009.5  208.65  5022.4  209.15  5026.2  210.11  5036.7  216.12  5047.3  218.03
  5073.9  219.06  5089.5  219.65  5110.5  221.86  5121.1  221.85  5173.8  225.53
  5205.4  226.80  5445.8  243.23  5490.9  246.61  5553.3  251.54  5627.0  255.55
#Mann=7,-1,0
  4386.3    0.05       0  5002.5     0.1       0  5009.0    0.05       0
  5022.4     0.1       0  5073.9    0.05       0  5445.8    0.12       0
  5490.9    0.05       0
Bank Sta=5009,5022.4
Exp/Cntr=0.3,0.1

Type RM Length L Ch R = 1,3763,485,485,485
BEGIN DESCRIPTION:
BLACKJACK CREEK 8.0
END DESCRIPTION:
XS GIS Cut Line= 3
      2466275.00     13597475.00      2466875.00     13597925.00
      2467124.99     13597925.00
#Sta/Elev= 30
  4250.5  245.58  4357.8  237.40  4372.4  236.57  4378.6  236.98  4407.8  234.33
  4443.2  232.97  4464.0  231.32  4537.0  227.70  4657.8  225.05  4822.4  223.24
  4850.5  223.10  4864.0  223.70  4887.0  223.74  5003.0  220.08  5010.5  219.21
  5020.5  215.56  5030.5  210.89  5033.8  207.97  5034.3  207.47  5046.8  207.47
  5047.3  207.97  5050.5  214.70  5060.5  215.32  5080.5  215.00  5090.5  216.31
  5110.5  220.50  5120.5  224.31  5140.5  227.59  5150.2  228.11  5250.5  232.83
#Mann=5,-1,0
  4250.5    0.05       0  4864.0     0.1       0  5033.8    0.05       0
  5047.3     0.1       0  5150.2    0.05       0
Bank Sta=5033.8,5047.3
Exp/Cntr=0.3,0.1

Type RM Length L Ch R = 1,3278,482,482,482
BEGIN DESCRIPTION:
BLACKJACK CREEK 7.0
END DESCRIPTION:
XS GIS Cut Line= 3
      2466174.99     13598725.00      2466775.00     13598375.00
      2467325.02     13598124.99
#Sta/Elev= 30
  4305.4  245.56  4473.7  232.78  4495.2  233.17  4525.4  229.86  4548.1  230.18
  4606.4  226.39  4687.0  224.05  4816.0  221.85  4843.9  218.47  4861.1  220.08
  4906.2  214.69  4927.7  214.03  4933.5  215.44  4949.2  213.38  4972.5  213.45
  4992.2  213.94  4997.1  208.93  5000.0  208.93  5002.0  205.26  5002.5  204.76
  5015.6  205.26  5022.0  211.29  5037.4  213.29  5056.0  212.28  5083.5  217.90
  5106.6  219.47  5340.6  229.13  5407.6  233.36  5425.0  234.38  5604.2  244.65
#Mann=8,-1,0
  4305.4    0.05       0  4843.9    0.12       0  4972.5     0.1       0
  5002.0    0.05       0  5015.6     0.1       0  5056.0    0.05       0
  5407.6   0.035       0  5425.0    0.05       0
Bank Sta=5002,5015.6
Exp/Cntr=0.3,0.1

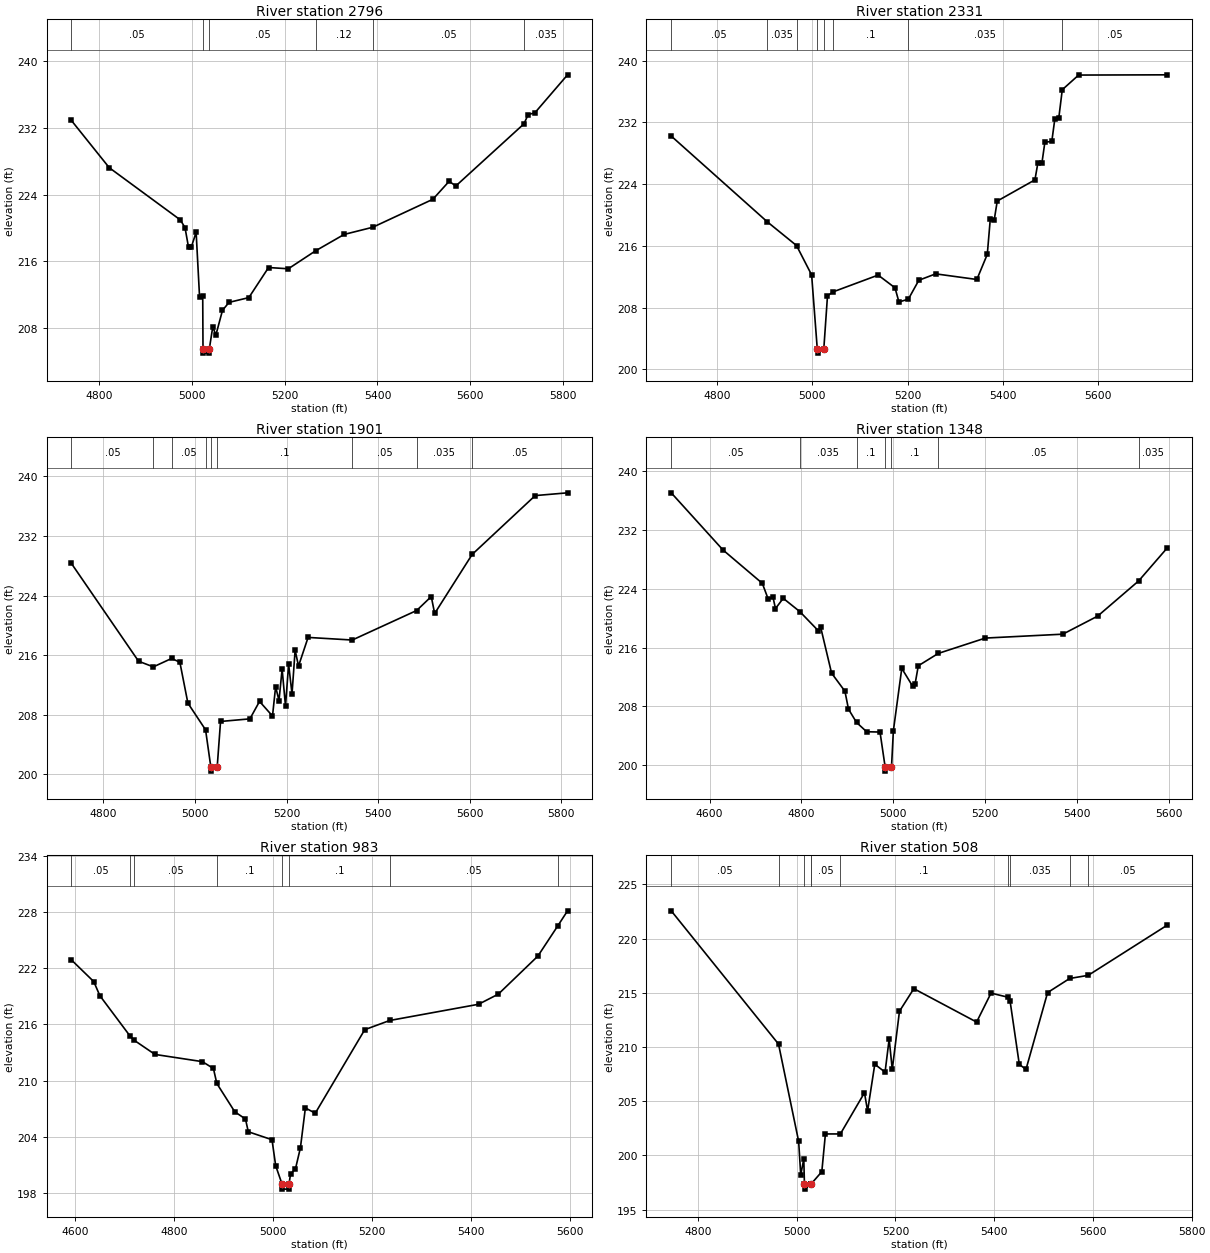
Type RM Length L Ch R = 1,2796,465,465,465
BEGIN DESCRIPTION:
BLACKJACK CREEK 6.0
END DESCRIPTION:
XS GIS Cut Line= 3
      2466425.00     13598875.00      2466675.00     13598825.00
      2467275.00     13598275.00
#Sta/Elev= 30
  4740.6  232.91  4822.2  227.24  4975.2  220.98  4985.4  220.06  4993.0  217.69
  4998.9  217.69  5009.4  219.50  5016.8  211.72  5023.6  211.83  5024.2  205.49
  5024.7  204.99  5037.3  204.99  5037.8  205.49  5045.2  208.13  5052.0  207.17
  5066.2  210.13  5080.3  211.08  5122.9  211.65  5165.4  215.26  5208.0  215.11
  5266.6  217.26  5328.2  219.23  5389.8  220.09  5519.4  223.45  5554.5  225.61
  5568.7  225.04  5715.6  232.50  5724.7  233.62  5738.9  233.81  5809.5  238.38
#Mann=6,-1,0
  4740.6    0.05       0  5024.2    0.05       0  5037.8    0.05       0
  5266.6    0.12       0  5389.8    0.05       0  5715.6   0.035       0
Bank Sta=5024.2,5037.8
Exp/Cntr=0.3,0.1

Type RM Length L Ch R = 1,2331,430,430,430
BEGIN DESCRIPTION:
BLACKJACK CREEK 5.0
END DESCRIPTION:
XS GIS Cut Line= 3
      2466675.00     13599325.00      2466925.00     13599175.00
      2467524.97     13598725.03
#Sta/Elev= 30
  4703.8  230.24  4905.4  219.12  4966.8  216.04  4998.5  212.23  5010.4  202.59
  5010.9  202.09  5024.0  202.59  5031.8  209.52  5043.3  210.03  5138.1  212.21
  5173.5  210.56  5181.8  208.72  5201.5  209.09  5223.5  211.54  5258.9  212.37
  5345.3  211.64  5367.2  214.90  5373.5  219.48  5381.8  219.38  5388.1  221.81
  5467.2  224.56  5473.5  226.79  5481.8  226.71  5488.1  229.45  5502.6  229.54
  5508.9  232.42  5517.2  232.54  5524.6  236.25  5558.9  238.15  5745.3  238.18
#Mann=8,-1,0
  4703.8    0.05       0  4905.4   0.035       0  4966.8    0.05       0
  5010.4    0.05       0  5024.0    0.05       0  5043.3     0.1       0
  5201.5   0.035       0  5524.6    0.05       0
Bank Sta=5010.4,5024
Exp/Cntr=0.3,0.1

Type RM Length L Ch R = 1,1901,553,553,553
BEGIN DESCRIPTION:
BLACKJACK CREEK 4.0
END DESCRIPTION:
XS GIS Cut Line= 3
      2466825.01     13599525.00      2467075.00     13599425.00
      2467625.01     13598824.99
#Sta/Elev= 30
  4730.3  228.31  4877.0  215.19  4909.3  214.43  4949.2  215.56  4967.2  215.05
  4984.7  209.57  5023.3  205.99  5034.9  200.95  5035.4  200.45  5048.6  200.95
  5056.0  207.11  5120.1  207.46  5141.1  209.80  5169.4  207.84  5176.2  211.76
  5183.6  209.92  5190.4  214.13  5197.8  209.17  5204.6  214.79  5212.0  210.80
  5218.8  216.67  5226.2  214.54  5247.1  218.38  5343.5  218.03  5484.1  221.99
  5516.0  223.86  5523.4  221.59  5605.3  229.51  5742.9  237.40  5813.5  237.77
#Mann=9,-1,0
  4730.3    0.05       0  4909.3   0.035       0  4949.2    0.05       0
  5023.3     0.1       0  5034.9    0.05       0  5048.6     0.1       0
  5343.5    0.05       0  5484.1   0.035       0  5605.3    0.05       0
Bank Sta=5034.9,5048.6
Exp/Cntr=0.3,0.1

Type RM Length L Ch R = 1,1348,365,365,365
BEGIN DESCRIPTION:
BLACKJACK CREEK 3.0
END DESCRIPTION:
XS GIS Cut Line= 3
      2467002.14     13599872.57      2467266.05     13599754.51
      2467574.98     13599025.04
#Sta/Elev= 30
  4516.3  237.08  4629.0  229.31  4714.8  224.76  4727.6  222.62  4738.0  222.88
  4743.5  221.33  4760.4  222.72  4796.4  220.92  4836.6  218.32  4842.0  218.77
  4865.7  212.54  4894.8  210.08  4902.6  207.63  4920.2  205.82  4942.2  204.56
  4971.3  204.52  4982.6  199.70  4983.1  199.20  4996.3  199.70  5000.4  204.70
  5018.7  213.18  5042.3  210.77  5047.8  211.09  5054.7  213.54  5098.2  215.22
  5200.7  217.31  5369.6  217.84  5445.6  220.30  5534.9  225.09  5597.6  229.61
#Mann=7,-1,0
  4516.3    0.05       0  4796.4   0.035       0  4920.2     0.1       0
  4982.6    0.05       0  4996.3     0.1       0  5098.2    0.05       0
  5534.9   0.035       0
Bank Sta=4982.6,4996.3
Exp/Cntr=0.3,0.1

Type RM Length L Ch R = 1,983,475,475,475
BEGIN DESCRIPTION:
BLACKJACK CREEK 2.0
END DESCRIPTION:
XS GIS Cut Line= 3
      2467325.01     13599874.99      2467675.00     13599675.00
      2467675.00     13599075.00
#Sta/Elev= 30
  4591.8  222.89  4637.1  220.57  4649.4  219.07  4709.8  214.81  4719.1  214.30
  4760.9  212.80  4856.7  212.03  4879.0  211.30  4885.9  209.70  4922.2  206.68
  4943.8  205.91  4949.5  204.55  4997.4  203.70  5004.9  200.92  5018.0  198.93
  5018.5  198.43  5031.2  198.43  5031.7  198.93  5034.9  200.04  5044.9  200.60
  5054.9  202.85  5064.9  207.09  5084.9  206.53  5184.9  215.44  5235.3  216.42
  5414.9  218.15  5454.9  219.23  5534.9  223.29  5574.6  226.47  5594.9  228.12
#Mann=8,-1,0
  4591.8    0.05       0  4709.8   0.035       0  4719.1    0.05       0
  4885.9     0.1       0  5018.0    0.05       0  5031.7     0.1       0
  5235.3    0.05       0  5574.6   0.035       0
Bank Sta=5018,5031.7
Exp/Cntr=0.3,0.1

Type RM Length L Ch R = 1,508,333,333,333
BEGIN DESCRIPTION:
BLACKJACK CREEK 1.0
END DESCRIPTION:
XS GIS Cut Line= 3
      2467374.97     13599974.99      2467625.00     13600025.00
      2468225.02     13599574.99
#Sta/Elev= 30
  4745.9  222.56  4963.2  210.27  5004.0  201.29  5008.2  198.20  5014.4  199.67
  5015.7  197.39  5016.2  196.89  5029.8  197.39  5029.9  197.40  5050.9  198.50
  5058.2  201.98  5088.5  201.98  5137.3  205.78  5143.6  204.10  5158.2  208.41
  5179.0  207.68  5187.3  210.73  5193.6  207.93  5208.2  213.30  5237.3  215.38
  5364.4  212.30  5393.6  214.97  5427.2  214.60  5432.3  214.21  5450.9  208.40
  5464.4  207.93  5508.2  215.02  5552.9  216.32  5590.5  216.61  5750.9  221.25
#Mann=10,-1,0
  4745.9    0.05       0  4963.2     0.1       0  5015.7    0.05       0
  5029.8     0.1       0  5029.9    0.05       0  5088.5     0.1       0
  5427.2    0.07       0  5432.3   0.035       0  5552.9    0.07       0
  5590.5    0.05       0
Bank Sta=5015.7,5029.8
Exp/Cntr=0.3,0.1

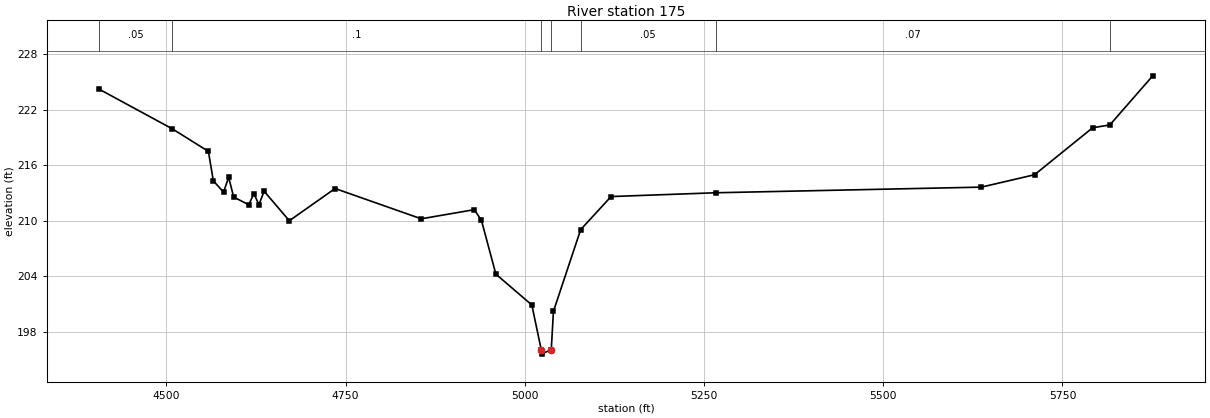
Type RM Length L Ch R = 1,175,0,0,0
BEGIN DESCRIPTION:
X18248
END DESCRIPTION:
XS GIS Cut Line= 4
      2467314.66     13599980.20      2467658.41     13600310.06
      2467967.44     13600282.29      2468563.76     13599949.46
#Sta/Elev= 30
  4406.3  224.24  4508.3  219.95  4558.6  217.51  4565.5  214.32  4579.7  213.10
  4586.9  214.71  4593.8  212.57  4614.9  211.73  4622.1  212.95  4629.1  211.73
  4636.3  213.20  4671.5  210.00  4735.3  213.49  4855.5  210.21  4929.5  211.20
  4939.5  210.04  4959.6  204.22  5009.8  200.88  5022.8  196.06  5023.3  195.56
  5036.9  196.06  5039.9  200.19  5077.9  209.04  5120.3  212.62  5266.2  213.03
  5636.8  213.64  5711.0  214.98  5792.1  220.07  5816.0  220.37  5875.9  225.69
#Mann=7,-1,0
  4406.3    0.05       0  4508.3     0.1       0  5022.8    0.05       0
  5036.9     0.1       0  5077.9    0.05       0  5266.2    0.07       0
  5816.0   0.035       0
Bank Sta=5022.8,5036.9
Exp/Cntr=0.3,0.1

Chan Stop Cuts=-1