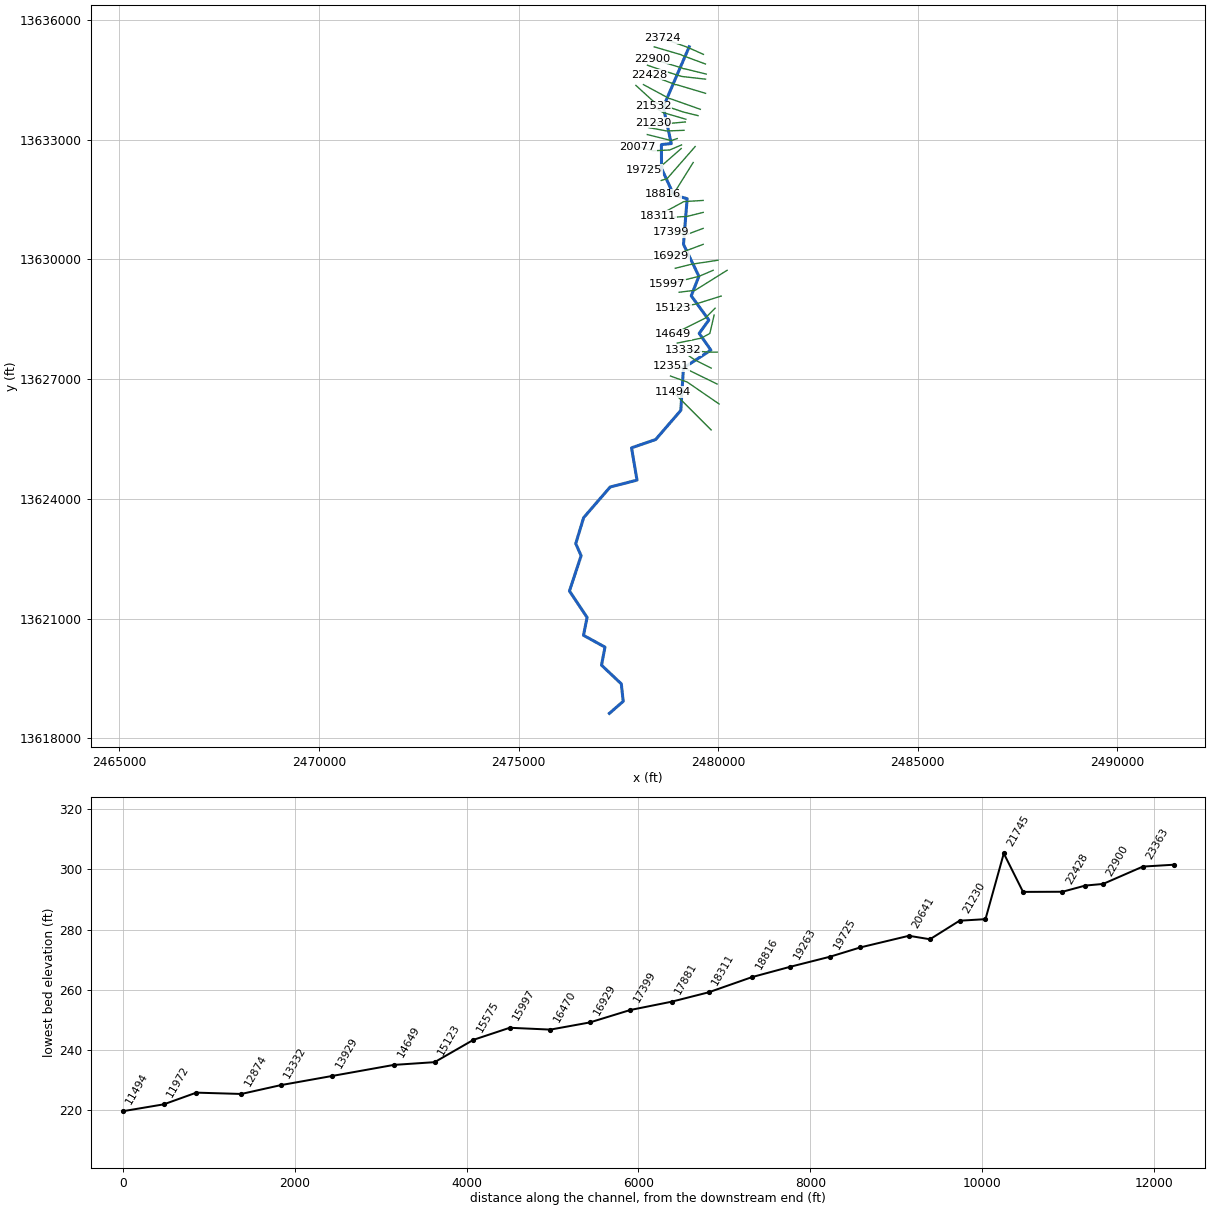
--- BOGGIE CREEK.prj (project) ---

Proj Title=BOGGIE CREEK Base Level Engineering
Current Plan=p01
Default Exp/Contr=0.3,0.1
English Units
Geom File=g01
Flow File=f01
Plan File=p01
Y Axis Title=Elevation
X Axis Title(PF)=Main Channel Distance
X Axis Title(XS)=Station
BEGIN DESCRIPTION:
BOGGIE CREEK
END DESCRIPTION:
DSS Export Rating Curves= 0
DSS Export Rating Curve Sorted= 0
DSS Export Volume Flow Curves= 0
DXF OffsetX= 0
DXF OffsetY= 0
DXF ScaleX= 1
DXF ScaleY= 10

--- BOGGIE CREEK.p01 (plan) ---

Plan Title=Multiple Run
Short Identifier=Multiple
Geom File=g01
Flow File=f01
Subcritical Flow
K Sum by GR= 0
Std Step Tol= 0.01
Critical Tol= 0.01
Num of Std Step Trials= 20
Max Error Tol= 0.3
Flow Tol Ratio= 0.001
Split Flow NTrial= 30
Split Flow Tol= 0.02
Split Flow Ratio= 0.02
Log Output Level= 0
Friction Slope Method= 1
Unsteady Friction Slope Method= 2
Unsteady Bridges Friction Slope Method= 1
Parabolic Critical Depth
Global Vel Dist=  1 , 1 , 1
Global Log Level= 0
CheckData=True
Encroach Param= -1, 0, 0, 0
BEGIN DESCRIPTION:
Multiple Run
END DESCRIPTION:

--- BOGGIE CREEK.f01 (steady flow) ---

Flow Title=Multiple
Number of Profiles=7
Profile Names=10-year,25-year,50-year,1pct_min,100-year,1pct_plu,500-year
River Rch & RM= BOGGIE CREEK,Reach-1,23724
     820    1347    1834    1210    2414    4818    4141
River Rch & RM= BOGGIE CREEK,Reach-1,20077
    1227    2053    2827    1883    3756    7495    6570
River Rch & RM= BOGGIE CREEK,Reach-1,13332
    1581    2668    3694    2471    4930    9836    8700
River Rch & RM= BOGGIE CREEK,Reach-1,6860
    1846    3148    4390    2955    5896   11763   10545
River Rch & RM= BOGGIE CREEK,Reach-1,6029
    2057    3519    4916    3313    6611   13191   11856
Boundary for River Rch & Prof#=BOGGIE CREEK,Reach-1,1
Up Type=0
Dn Type=3
Dn Slope=0.005
Boundary for River Rch & Prof#=BOGGIE CREEK,Reach-1,2
Up Type=0
Dn Type=3
Dn Slope=0.005
Boundary for River Rch & Prof#=BOGGIE CREEK,Reach-1,3
Up Type=0
Dn Type=3
Dn Slope=0.005
Boundary for River Rch & Prof#=BOGGIE CREEK,Reach-1,4
Up Type=0
Dn Type=3
Dn Slope=0.005
Boundary for River Rch & Prof#=BOGGIE CREEK,Reach-1,5
Up Type=0
Dn Type=3
Dn Slope=0.005
Boundary for River Rch & Prof#=BOGGIE CREEK,Reach-1,6
Up Type=0
Dn Type=3
Dn Slope=0.005
Boundary for River Rch & Prof#=BOGGIE CREEK,Reach-1,7
Up Type=0
Dn Type=3
Dn Slope=0.005

--- BOGGIE CREEK.g01 (geometry) ---

Geom Title=Existing Conditions

River Reach=BOGGIE CREEK,Reach-1
Reach XY= 30
      2479275.00     13635325.00      2478626.66     13633818.95
      2478825.30     13632899.69      2478578.45     13632873.81
      2478582.11     13632275.00      2478888.20     13631611.26
      2479223.39     13631518.98      2479132.09     13630375.00
      2479518.03     13629575.24      2479325.55     13629085.64
      2479767.52     13628478.57      2479524.89     13628144.89
      2479817.95     13627725.26      2479130.35     13627277.77
      2479064.81     13626215.32      2478435.12     13625485.63
      2477830.45     13625277.47      2477967.38     13624468.50
      2477294.63     13624295.48      2476630.31     13623527.76
      2476432.60     13622878.34      2476567.47     13622574.99
      2476275.08     13621690.39      2476716.96     13621028.32
      2476626.98     13620580.67      2477164.84     13620284.70
      2477078.06     13619833.28      2477573.94     13619364.34
      2477621.92     13618926.68      2477275.00     13618625.00

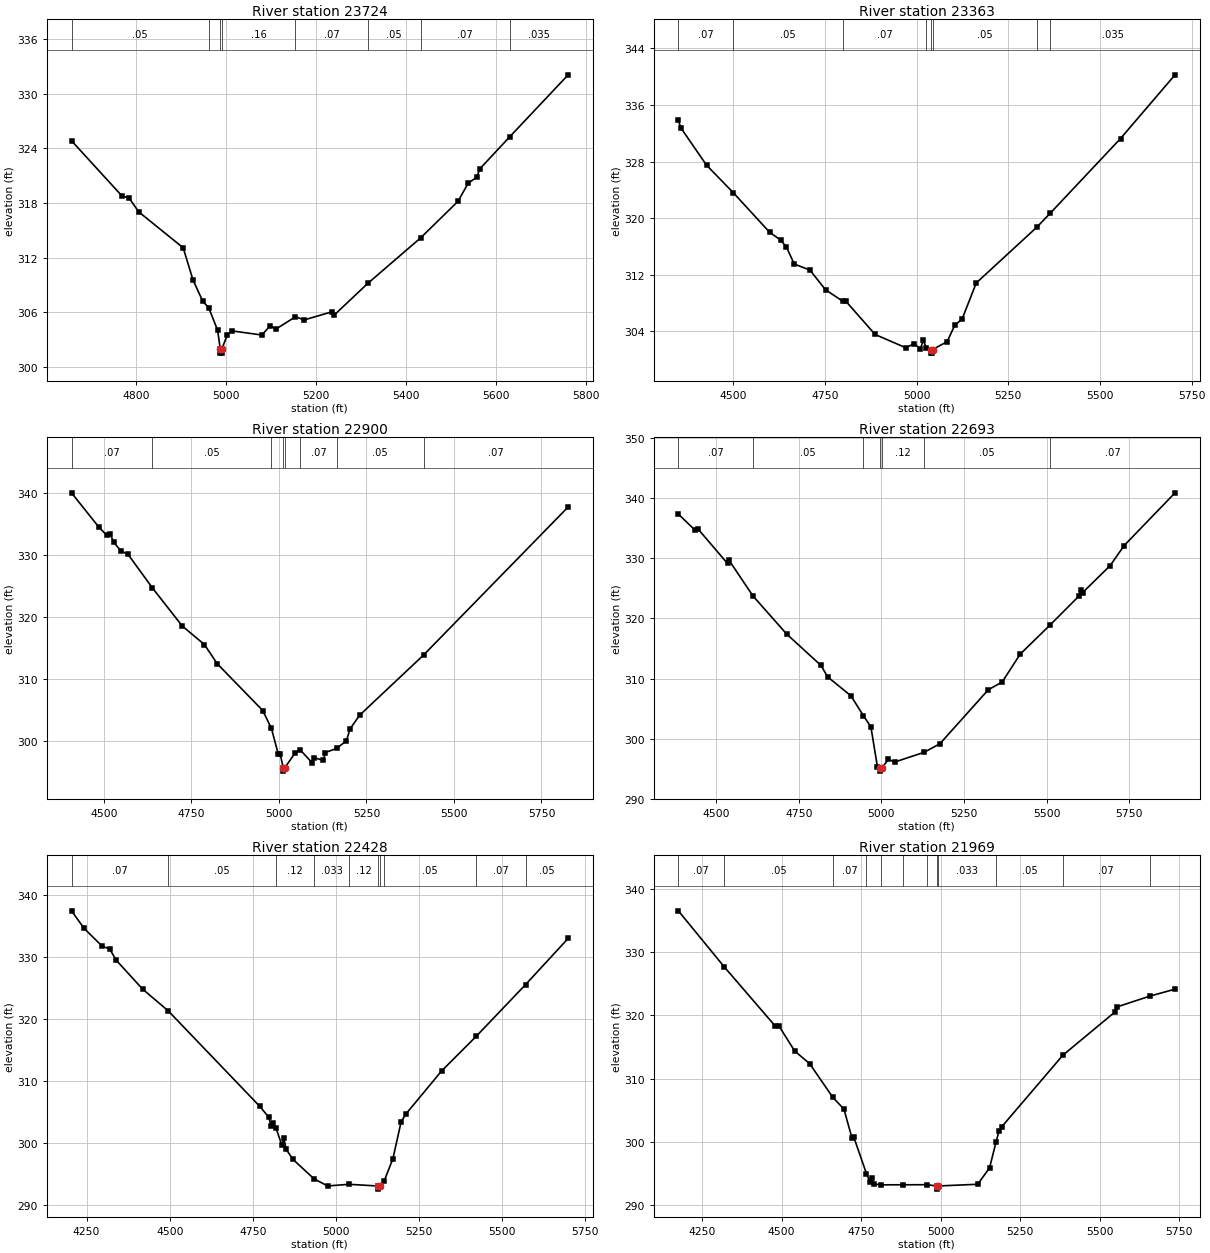
Type RM Length L Ch R = 1,23724,361,361,361
BEGIN DESCRIPTION:
X18308
END DESCRIPTION:
XS GIS Cut Line= 3
      2479632.02     13635134.20      2479227.26     13635313.73
      2478603.88     13635535.67
#Sta/Elev= 30
  4656.8  324.83  4769.1  318.76  4784.8  318.53  4806.7  317.00  4905.2  313.07
  4927.0  309.53  4948.9  307.18  4961.8  306.50  4981.7  304.02  4987.5  302.00
  4987.7  301.50  4991.2  301.50  4991.5  302.00  5003.6  303.53  5012.7  303.95
  5080.2  303.49  5098.1  304.48  5112.6  304.18  5154.9  305.49  5174.4  305.15
  5236.1  306.04  5241.4  305.70  5315.9  309.17  5433.2  314.16  5516.0  318.16
  5539.1  320.17  5558.4  320.84  5564.6  321.73  5631.7  325.28  5761.3  332.07
#Mann=8,-1,0
  4656.8    0.05       0  4961.8    0.16       0  4987.5    0.07       0
  4991.5    0.16       0  5154.9    0.07       0  5315.9    0.05       0
  5433.2    0.07       0  5631.7   0.035       0
Bank Sta=4987.5,4991.5
Exp/Cntr=0.3,0.1

Type RM Length L Ch R = 1,23363,463,463,463
BEGIN DESCRIPTION:
BOGGIE CREEK 3 46.0
END DESCRIPTION:
XS GIS Cut Line= 5
      2479681.35     13634892.98      2479100.11     13635108.26
      2479075.00     13635125.00      2479048.98     13635131.51
      2478398.73     13635322.30
#Sta/Elev= 30
  4350.2  333.81  4357.0  332.76  4427.1  327.48  4499.8  323.60  4598.8  318.00
  4629.2  316.88  4644.9  315.90  4666.2  313.49  4708.9  312.64  4751.5  309.85
  4798.8  308.22  4806.2  308.27  4886.8  303.52  4970.0  301.65  4992.7  302.19
  5010.5  301.51  5018.2  302.71  5026.9  301.56  5039.4  301.38  5039.7  300.88
  5043.2  300.88  5043.4  301.38  5083.3  302.51  5104.1  304.84  5124.0  305.70
  5162.6  310.81  5327.5  318.69  5364.7  320.70  5556.0  331.25  5704.7  340.27
#Mann=8,-1,0
  4350.2    0.07       0  4499.8    0.05       0  4798.8    0.07       0
  5026.9    0.05       0  5039.4    0.05       0  5043.4    0.05       0
  5327.5    0.07       0  5364.7   0.035       0
Bank Sta=5039.4,5043.4
Exp/Cntr=0.3,0.1

Type RM Length L Ch R = 1,22900,207,207,207
BEGIN DESCRIPTION:
BOGGIE CREEK 3 45.0
END DESCRIPTION:
XS GIS Cut Line= 5
      2479702.19     13634640.37      2479152.75     13634775.00
      2479125.00     13634775.00      2479101.19     13634790.87
      2478338.85     13635022.81
#Sta/Elev= 30
  4407.4  340.02  4485.8  334.47  4507.5  333.22  4517.8  333.44  4527.4  332.08
  4548.6  330.66  4569.0  330.08  4638.8  324.66  4723.7  318.54  4787.3  315.53
  4823.8  312.44  4953.7  304.90  4978.5  302.02  4998.3  297.83  5003.8  297.83
  5012.4  295.62  5012.6  295.12  5016.4  295.62  5046.4  298.07  5061.0  298.53
  5094.3  296.50  5099.5  297.29  5127.1  296.86  5132.4  298.12  5164.8  298.78
  5192.7  300.01  5203.3  301.94  5230.9  304.16  5413.2  313.85  5826.3  337.74
#Mann=8,-1,0
  4407.4    0.07       0  4638.8    0.05       0  4978.5    0.12       0
  5012.4    0.05       0  5016.4    0.12       0  5061.0    0.07       0
  5164.8    0.05       0  5413.2    0.07       0
Bank Sta=5012.4,5016.4
Exp/Cntr=0.3,0.1

Type RM Length L Ch R = 1,22693,265,265,265
BEGIN DESCRIPTION:
X18309
END DESCRIPTION:
XS GIS Cut Line= 5
      2479684.01     13634512.75      2479137.43     13634574.92
      2479080.38     13634582.61      2478644.58     13634719.95
      2478229.11     13634861.43
#Sta/Elev= 30
  4385.3  337.37  4434.6  334.76  4444.5  334.91  4534.1  329.15  4539.1  329.65
  4611.1  323.74  4713.2  317.40  4817.1  312.17  4837.2  310.27  4907.7  307.12
  4945.5  303.80  4968.1  301.96  4988.1  295.23  4996.6  295.08  4996.9  294.58
  5000.6  295.08  5021.2  296.52  5040.5  296.10  5129.2  297.71  5176.9  299.13
  5323.6  308.13  5365.6  309.42  5420.0  314.05  5511.3  318.95  5597.3  323.69
  5603.9  324.81  5609.2  324.31  5692.4  328.79  5734.7  332.13  5888.8  340.91
#Mann=7,-1,0
  4385.3    0.07       0  4611.1    0.05       0  4945.5    0.12       0
  4996.6    0.05       0  5000.6    0.12       0  5129.2    0.05       0
  5511.3    0.07       0
Bank Sta=4996.6,5000.6
Exp/Cntr=0.3,0.1

Type RM Length L Ch R = 1,22428,459,459,459
BEGIN DESCRIPTION:
BOGGIE CREEK 3 44.0
END DESCRIPTION:
XS GIS Cut Line= 5
      2479683.98     13634158.59      2478957.44     13634375.00
      2478925.00     13634375.00      2478892.73     13634391.14
      2478268.66     13634626.84
#Sta/Elev= 30
  4204.7  337.47  4242.4  334.65  4297.5  331.73  4319.2  331.33  4339.3  329.49
  4418.7  324.82  4494.8  321.36  4771.2  305.88  4798.4  304.11  4804.4  302.75
  4809.6  303.14  4819.5  302.44  4837.5  299.58  4842.8  300.85  4850.6  298.93
  4870.7  297.34  4934.1  294.19  4975.2  293.04  5038.8  293.31  5127.4  293.03
  5127.6  292.53  5131.4  293.03  5145.1  293.85  5171.4  297.46  5196.2  303.45
  5210.6  304.67  5317.5  311.60  5421.4  317.18  5570.3  325.56  5698.4  333.02
#Mann=10,-1,0
  4204.7    0.07       0  4494.8    0.05       0  4819.5    0.12       0
  4934.1   0.033       0  5038.8    0.12       0  5127.4   0.033       0
  5131.4    0.12       0  5145.1    0.05       0  5421.4    0.07       0
  5570.3    0.05       0
Bank Sta=5127.4,5131.4
Exp/Cntr=0.3,0.1

Type RM Length L Ch R = 1,21969,224,224,224
BEGIN DESCRIPTION:
BOGGIE CREEK 3 43.0
END DESCRIPTION:
XS GIS Cut Line= 5
      2479553.77     13633757.55      2478798.59     13634025.00
      2478775.00     13634025.00      2478750.71     13634041.19
      2478128.38     13634376.44
#Sta/Elev= 30
  4175.7  336.57  4319.1  327.74  4479.7  318.34  4492.7  318.26  4541.4  314.35
  4588.1  312.37  4661.3  307.00  4695.9  305.17  4721.5  300.55  4726.8  300.75
  4766.8  294.93  4778.0  293.65  4783.3  294.29  4789.7  293.30  4813.6  293.16
  4882.7  293.17  4956.1  293.18  4988.4  292.98  4988.7  292.48  4992.4  292.98
  5116.4  293.25  5153.6  295.85  5173.7  299.88  5183.8  301.76  5192.6  302.40
  5384.1  313.70  5547.2  320.52  5553.6  321.34  5656.8  323.05  5736.5  324.16
#Mann=12,-1,0
  4175.7    0.07       0  4319.1    0.05       0  4661.3    0.07       0
  4766.8    0.05       0  4813.6   0.033       0  4882.7    0.07       0
  4956.1   0.033       0  4988.4   0.033       0  4992.4   0.033       0
  5173.7    0.05       0  5384.1    0.07       0  5656.8    0.05       0
Bank Sta=4988.4,4992.4
Exp/Cntr=0.3,0.1

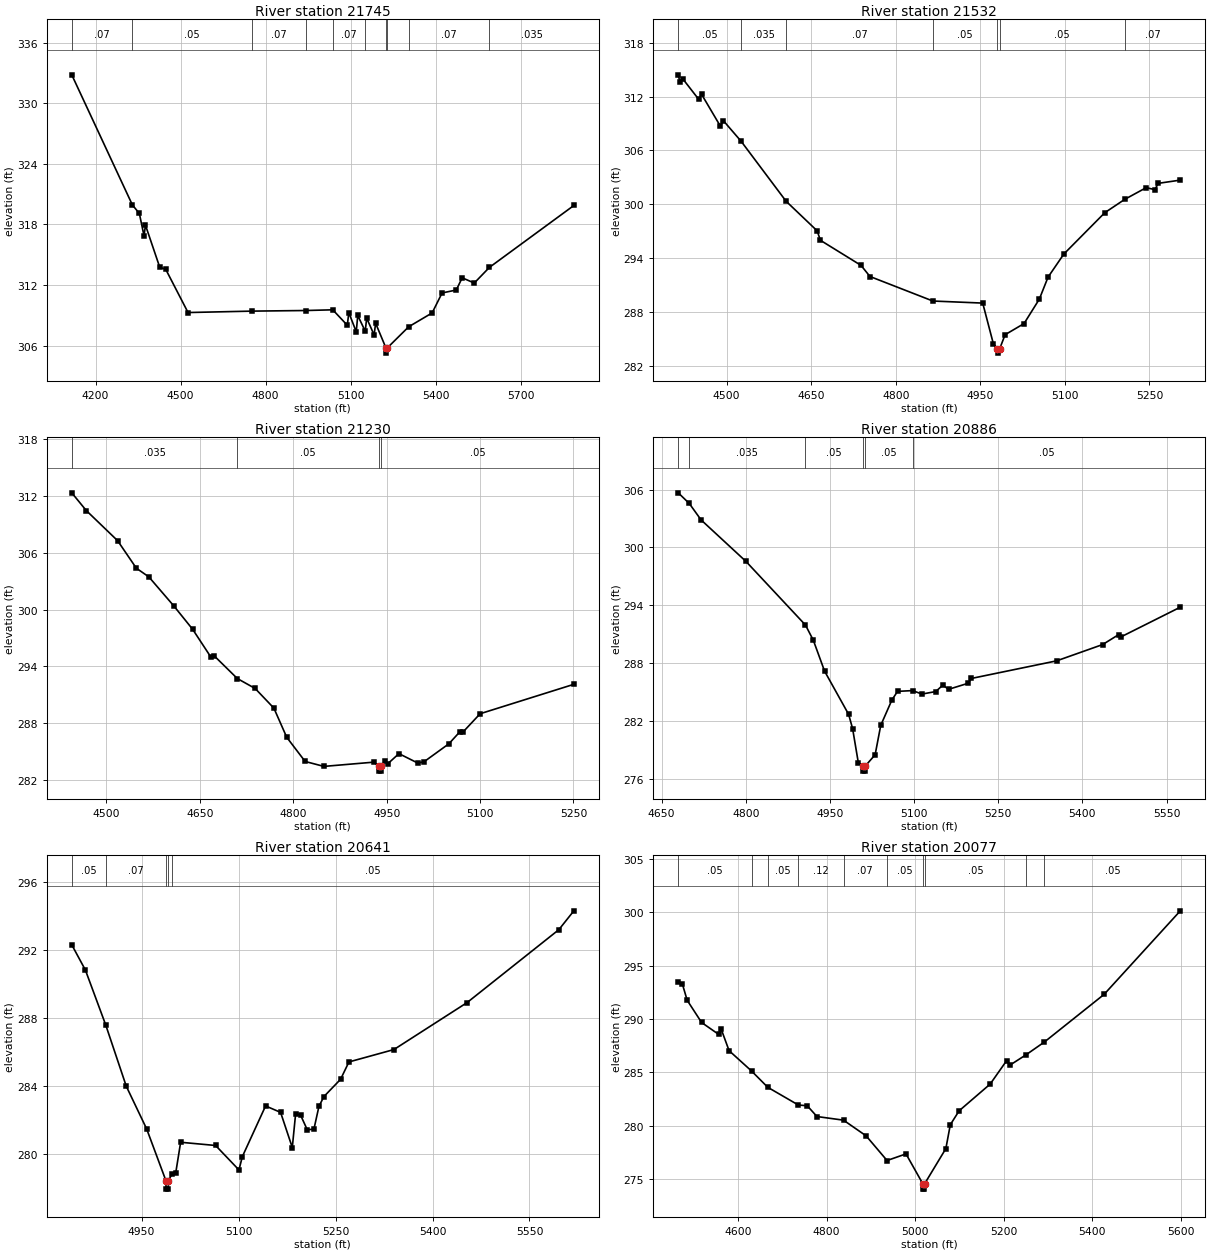
Type RM Length L Ch R = 1,21745,213,213,213
BEGIN DESCRIPTION:
X18310
END DESCRIPTION:
XS GIS Cut Line= 4
      2479496.55     13633598.68      2479130.75     13633688.96
      2478402.47     13633933.79      2477939.61     13634356.14
#Sta/Elev= 30
  4115.9  332.81  4329.7  319.93  4354.4  319.08  4370.8  316.87  4376.0  317.92
  4426.5  313.74  4447.1  313.57  4526.2  309.27  4751.9  309.41  4941.9  309.47
  5036.9  309.54  5088.2  308.01  5093.5  309.26  5119.8  307.36  5125.0  308.98
  5151.5  307.42  5156.5  308.72  5182.8  307.05  5188.1  308.21  5224.7  305.75
  5224.9  305.25  5228.7  305.75  5304.8  307.86  5387.5  309.23  5422.7  311.21
  5472.7  311.50  5493.6  312.71  5536.2  312.19  5589.6  313.74  5887.6  319.87
#Mann=10,-1,0
  4115.9    0.07       0  4329.7    0.05       0  4751.9    0.07       0
  4941.9    0.05       0  5036.9    0.07       0  5151.5    0.05       0
  5224.7    0.05       0  5228.7    0.05       0  5304.8    0.07       0
  5589.6   0.035       0
Bank Sta=5224.7,5228.7
Exp/Cntr=0.3,0.1

Type RM Length L Ch R = 1,21532,302,302,302
BEGIN DESCRIPTION:
BOGGIE CREEK 3 42.0
END DESCRIPTION:
XS GIS Cut Line= 3
      2479191.31     13633508.78      2478625.00     13633675.00
      2478368.83     13633831.90
#Sta/Elev= 30
  4414.2  314.42  4417.0  313.66  4422.3  313.97  4450.4  311.70  4455.6  312.25
  4489.0  308.70  4494.2  309.32  4525.8  307.02  4605.5  300.35  4660.5  297.06
  4666.4  296.00  4738.4  293.21  4754.3  291.97  4865.9  289.24  4954.3  289.01
  4973.1  284.50  4980.5  283.94  4980.7  283.44  4984.5  283.94  4994.0  285.49
  5027.6  286.73  5054.7  289.45  5070.2  291.90  5098.2  294.47  5170.8  299.07
  5206.3  300.56  5244.3  301.86  5259.7  301.64  5265.6  302.34  5304.8  302.70
#Mann=7,-1,0
  4414.2    0.05       0  4525.8   0.035       0  4605.5    0.07       0
  4865.9    0.05       0  4980.5    0.05       0  4984.5    0.05       0
  5206.3    0.07       0
Bank Sta=4980.5,4984.5
Exp/Cntr=0.3,0.1

Type RM Length L Ch R = 1,21230,344,344,344
BEGIN DESCRIPTION:
BOGGIE CREEK 3 41.0
END DESCRIPTION:
XS GIS Cut Line= 3
      2479178.32     13633440.23      2478701.76     13633397.79
      2478375.03     13633425.00
#Sta/Elev= 30
  4444.3  312.35  4467.7  310.47  4517.9  307.29  4548.0  304.38  4568.1  303.46
  4608.3  300.38  4638.4  297.92  4667.9  294.96  4672.9  295.12  4710.2  292.71
  4738.8  291.66  4768.9  289.58  4789.5  286.50  4819.1  283.94  4849.2  283.42
  4929.5  283.87  4937.6  283.42  4937.8  282.92  4941.3  282.92  4941.6  283.42
  4947.0  283.98  4952.0  283.71  4969.7  284.77  4999.8  283.78  5009.8  283.90
  5049.9  285.81  5067.4  287.07  5072.4  287.04  5100.1  288.99  5250.6  292.10
#Mann=4,-1,0
  4444.3   0.035       0  4710.2    0.05       0  4937.6    0.05       0
  4941.6    0.05       0
Bank Sta=4937.6,4941.6
Exp/Cntr=0.3,0.1

Type RM Length L Ch R = 1,20886,245,245,245
BEGIN DESCRIPTION:
X18311
END DESCRIPTION:
XS GIS Cut Line= 3
      2479145.62     13633231.33      2478711.55     13633215.01
      2478258.98     13633299.66
#Sta/Elev= 30
  4679.7  305.66  4699.3  304.56  4720.4  302.85  4800.4  298.54  4906.5  291.93
  4920.5  290.35  4940.5  287.15  4983.4  282.66  4990.5  281.17  5000.6  277.66
  5008.6  277.27  5008.8  276.77  5012.3  276.77  5012.6  277.27  5030.6  278.47
  5040.6  281.52  5060.6  284.17  5070.6  285.05  5097.3  285.13  5114.1  284.77
  5138.6  285.03  5151.3  285.70  5161.4  285.26  5196.3  285.89  5202.1  286.39
  5354.2  288.22  5436.1  289.91  5464.6  290.94  5469.6  290.73  5574.5  293.79
#Mann=6,-1,0
  4679.7    0.05       0  4699.3   0.035       0  4906.5    0.05       0
  5008.6    0.05       0  5012.6    0.05       0  5097.3    0.05       0
Bank Sta=5008.6,5012.6
Exp/Cntr=0.3,0.1

Type RM Length L Ch R = 1,20641,564,564,564
BEGIN DESCRIPTION:
BOGGIE CREEK 3 40.0
END DESCRIPTION:
XS GIS Cut Line= 3
      2478974.98     13633024.99      2478825.00     13632975.00
      2478224.96     13633125.01
#Sta/Elev= 30
  4842.0  292.31  4863.1  290.82  4894.6  287.58  4926.3  283.98  4957.9  281.46
  4987.6  278.42  4987.8  277.92  4991.3  277.92  4991.6  278.42  4997.3  278.84
  5002.7  278.85  5010.4  280.68  5064.5  280.49  5100.6  279.05  5105.8  279.83
  5141.8  282.82  5165.0  282.44  5183.1  280.37  5188.2  282.34  5195.9  282.28
  5206.3  281.41  5216.6  281.46  5224.3  282.79  5232.0  283.37  5257.8  284.39
  5270.7  285.41  5340.3  286.14  5453.6  288.91  5595.4  293.20  5618.6  294.31
#Mann=5,-1,0
  4842.0    0.05       0  4894.6    0.07       0  4987.6    0.05       0
  4991.6    0.07       0  4997.3    0.05       0
Bank Sta=4987.6,4991.6
Exp/Cntr=0.3,0.1

Type RM Length L Ch R = 1,20077,352,352,352
BEGIN DESCRIPTION:
X18312
END DESCRIPTION:
XS GIS Cut Line= 4
      2479083.62     13632865.76      2478783.36     13632738.47
      2478365.57     13632718.89      2477988.58     13632819.64
#Sta/Elev= 30
  4464.9  293.48  4474.2  293.29  4485.1  291.76  4517.7  289.68  4556.1  288.57
  4561.6  289.10  4579.8  287.04  4630.7  285.13  4667.2  283.61  4736.3  281.95
  4756.4  281.88  4778.4  280.87  4838.4  280.53  4889.5  279.06  4936.8  276.75
  4979.6  277.37  5017.6  274.57  5017.9  274.07  5021.4  274.07  5021.7  274.57
  5069.7  277.87  5079.7  280.10  5099.7  281.41  5169.8  283.91  5207.1  286.11
  5214.3  285.68  5251.1  286.66  5292.3  287.85  5427.2  292.31  5599.5  300.14
#Mann=10,-1,0
  4464.9    0.05       0  4630.7    0.07       0  4667.2    0.05       0
  4736.3    0.12       0  4838.4    0.07       0  4936.8    0.05       0
  5017.6    0.05       0  5021.7    0.05       0  5251.1   0.035       0
  5292.3    0.05       0
Bank Sta=5017.6,5021.7
Exp/Cntr=0.3,0.1

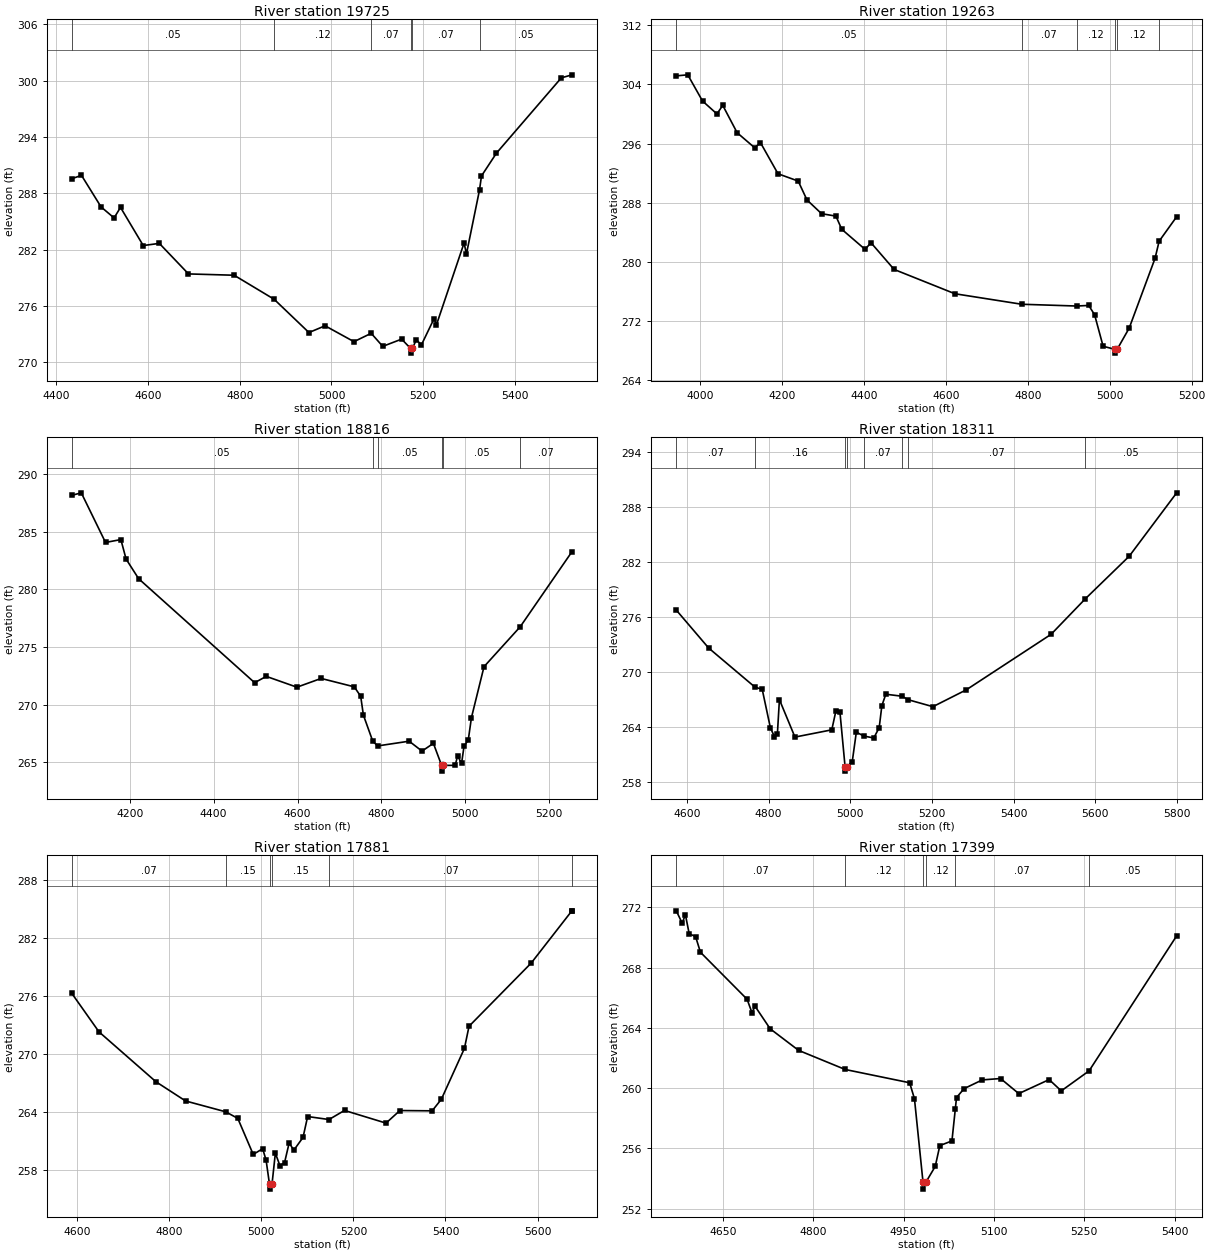
Type RM Length L Ch R = 1,19725,462,462,462
BEGIN DESCRIPTION:
BOGGIE CREEK 3 39.0
END DESCRIPTION:
XS GIS Cut Line= 3
      2479075.04     13632775.03      2478639.75     13632392.49
      2478150.14     13632242.35
#Sta/Elev= 30
  4433.3  289.55  4454.7  289.91  4497.4  286.55  4525.8  285.38  4539.8  286.50
  4589.4  282.44  4624.5  282.67  4688.1  279.42  4787.7  279.28  4875.0  276.72
  4950.9  273.18  4986.1  273.90  5049.1  272.21  5086.7  273.10  5111.9  271.71
  5153.1  272.48  5172.6  271.49  5172.9  270.99  5176.7  271.49  5185.1  272.42
  5196.3  271.87  5223.8  274.66  5229.1  274.01  5289.3  282.71  5294.5  281.55
  5323.0  288.36  5327.3  289.85  5360.0  292.28  5501.5  300.29  5524.9  300.61
#Mann=6,-1,0
  4433.3    0.05       0  4875.0    0.12       0  5086.7    0.07       0
  5172.6    0.07       0  5176.7    0.07       0  5323.0    0.05       0
Bank Sta=5172.6,5176.7
Exp/Cntr=0.3,0.1

Type RM Length L Ch R = 1,19263,447,447,447
BEGIN DESCRIPTION:
BOGGIE CREEK 3 38.0
END DESCRIPTION:
XS GIS Cut Line= 3
      2479424.99     13632824.99      2478725.00     13632025.00
      2478575.01     13631975.00
#Sta/Elev= 30
  3942.2  305.16  3970.2  305.30  4006.2  301.76  4041.4  300.01  4055.6  301.17
  4090.7  297.47  4133.4  295.44  4147.7  296.12  4190.4  291.92  4239.7  290.93
  4261.1  288.38  4296.7  286.52  4331.8  286.19  4346.0  284.41  4403.0  281.69
  4417.2  282.60  4473.7  278.98  4622.2  275.69  4785.2  274.27  4918.9  274.03
  4948.7  274.11  4963.0  272.85  4983.8  268.59  5013.6  268.16  5013.9  267.66
  5017.9  268.16  5047.4  271.04  5110.6  280.49  5120.5  282.80  5163.3  286.11
#Mann=6,-1,0
  3942.2    0.05       0  4785.2    0.07       0  4918.9    0.12       0
  5013.6    0.07       0  5017.9    0.12       0  5120.5    0.05       0
Bank Sta=5013.6,5017.9
Exp/Cntr=0.3,0.1

Type RM Length L Ch R = 1,18816,505,505,505
BEGIN DESCRIPTION:
BOGGIE CREEK 3 37.0
END DESCRIPTION:
XS GIS Cut Line= 3
      2479374.97     13632424.96      2478875.00     13631625.00
      2478625.05     13631625.00
#Sta/Elev= 30
  4061.4  288.17  4084.3  288.39  4142.1  284.08  4178.7  284.33  4191.1  282.64
  4221.1  280.93  4497.7  271.90  4525.4  272.45  4598.5  271.51  4656.3  272.27
  4735.3  271.54  4750.6  270.72  4757.1  269.08  4779.5  266.81  4791.2  266.41
  4866.2  266.82  4896.8  265.96  4924.0  266.63  4943.6  264.72  4943.9  264.22
  4947.9  264.72  4975.9  264.72  4981.8  265.54  4991.2  264.89  4997.1  266.39
  5007.2  266.93  5014.7  268.86  5044.7  273.29  5131.1  276.76  5254.7  283.29
#Mann=6,-1,0
  4061.4    0.05       0  4779.5    0.12       0  4791.2    0.05       0
  4943.6    0.05       0  4947.9    0.05       0  5131.1    0.07       0
Bank Sta=4943.6,4947.9
Exp/Cntr=0.3,0.1

Type RM Length L Ch R = 1,18311,430,430,430
BEGIN DESCRIPTION:
BOGGIE CREEK 3 36.0
END DESCRIPTION:
XS GIS Cut Line= 3
      2479625.00     13631475.00      2479142.40     13631445.95
      2478489.84     13631093.57
#Sta/Elev= 30
  4573.9  276.76  4653.1  272.62  4766.4  268.35  4784.3  268.10  4804.3  263.90
  4814.3  262.93  4821.4  263.21  4826.4  266.98  4864.4  262.89  4954.6  263.68
  4964.6  265.73  4974.6  265.61  4987.1  259.67  4987.5  259.17  4992.4  259.67
  5004.7  260.21  5014.7  263.42  5033.5  263.00  5057.4  262.79  5070.7  263.92
  5077.2  266.32  5086.9  267.57  5127.1  267.35  5140.8  266.98  5202.2  266.21
  5283.9  268.05  5491.4  274.11  5575.5  278.00  5682.7  282.64  5799.0  289.57
#Mann=8,-1,0
  4573.9    0.07       0  4766.4    0.16       0  4987.1    0.07       0
  4992.4    0.16       0  5033.5    0.07       0  5127.1    0.15       0
  5140.8    0.07       0  5575.5    0.05       0
Bank Sta=4987.1,4992.4
Exp/Cntr=0.3,0.1

Type RM Length L Ch R = 1,17881,482,482,482
BEGIN DESCRIPTION:
BOGGIE CREEK 3 35.0
END DESCRIPTION:
XS GIS Cut Line= 3
      2479625.01     13631175.00      2479225.00     13631075.00
      2478551.63     13631034.69
#Sta/Elev= 30
  4588.1  276.33  4647.4  272.33  4771.1  267.17  4835.5  265.18  4922.6  264.06
  4948.9  263.38  4982.4  259.65  5002.9  260.24  5010.4  259.05  5017.8  256.56
  5018.2  256.06  5023.2  256.56  5030.5  259.78  5040.5  258.48  5050.5  258.81
  5060.5  260.84  5070.6  260.09  5090.6  261.41  5100.6  263.57  5147.0  263.26
  5180.7  264.20  5270.9  262.89  5301.0  264.19  5371.1  264.16  5391.1  265.36
  5441.2  270.62  5451.2  272.91  5586.3  279.45  5674.6  284.85  5675.0  284.85
#Mann=6,-1,0
  4588.1    0.07       0  4922.6    0.15       0  5017.8    0.07       0
  5023.2    0.15       0  5147.0    0.07       0  5674.6    0.05       0
Bank Sta=5017.8,5023.2
Exp/Cntr=0.3,0.1

Type RM Length L Ch R = 1,17399,470,470,470
BEGIN DESCRIPTION:
BOGGIE CREEK 3 34.0
END DESCRIPTION:
XS GIS Cut Line= 3
      2479625.01     13630775.00      2479225.00     13630625.00
      2478825.02     13630675.00
#Sta/Elev= 30
  4572.9  271.77  4582.7  270.95  4588.0  271.52  4594.3  270.25  4604.9  270.06
  4613.0  269.02  4690.4  265.90  4698.4  265.02  4703.7  265.43  4728.7  263.94
  4775.8  262.51  4853.2  261.24  4960.1  260.36  4968.1  259.30  4982.2  253.80
  4982.7  253.30  4987.7  253.80  5002.6  254.81  5010.2  256.19  5030.3  256.50
  5035.9  258.62  5037.9  259.38  5050.5  259.97  5080.7  260.55  5111.0  260.64
  5141.2  259.64  5191.6  260.57  5211.7  259.82  5257.9  261.15  5403.2  270.11
#Mann=6,-1,0
  4572.9    0.07       0  4853.2    0.12       0  4982.2    0.07       0
  4987.7    0.12       0  5035.9    0.07       0  5257.9    0.05       0
Bank Sta=4982.2,4987.7
Exp/Cntr=0.3,0.1

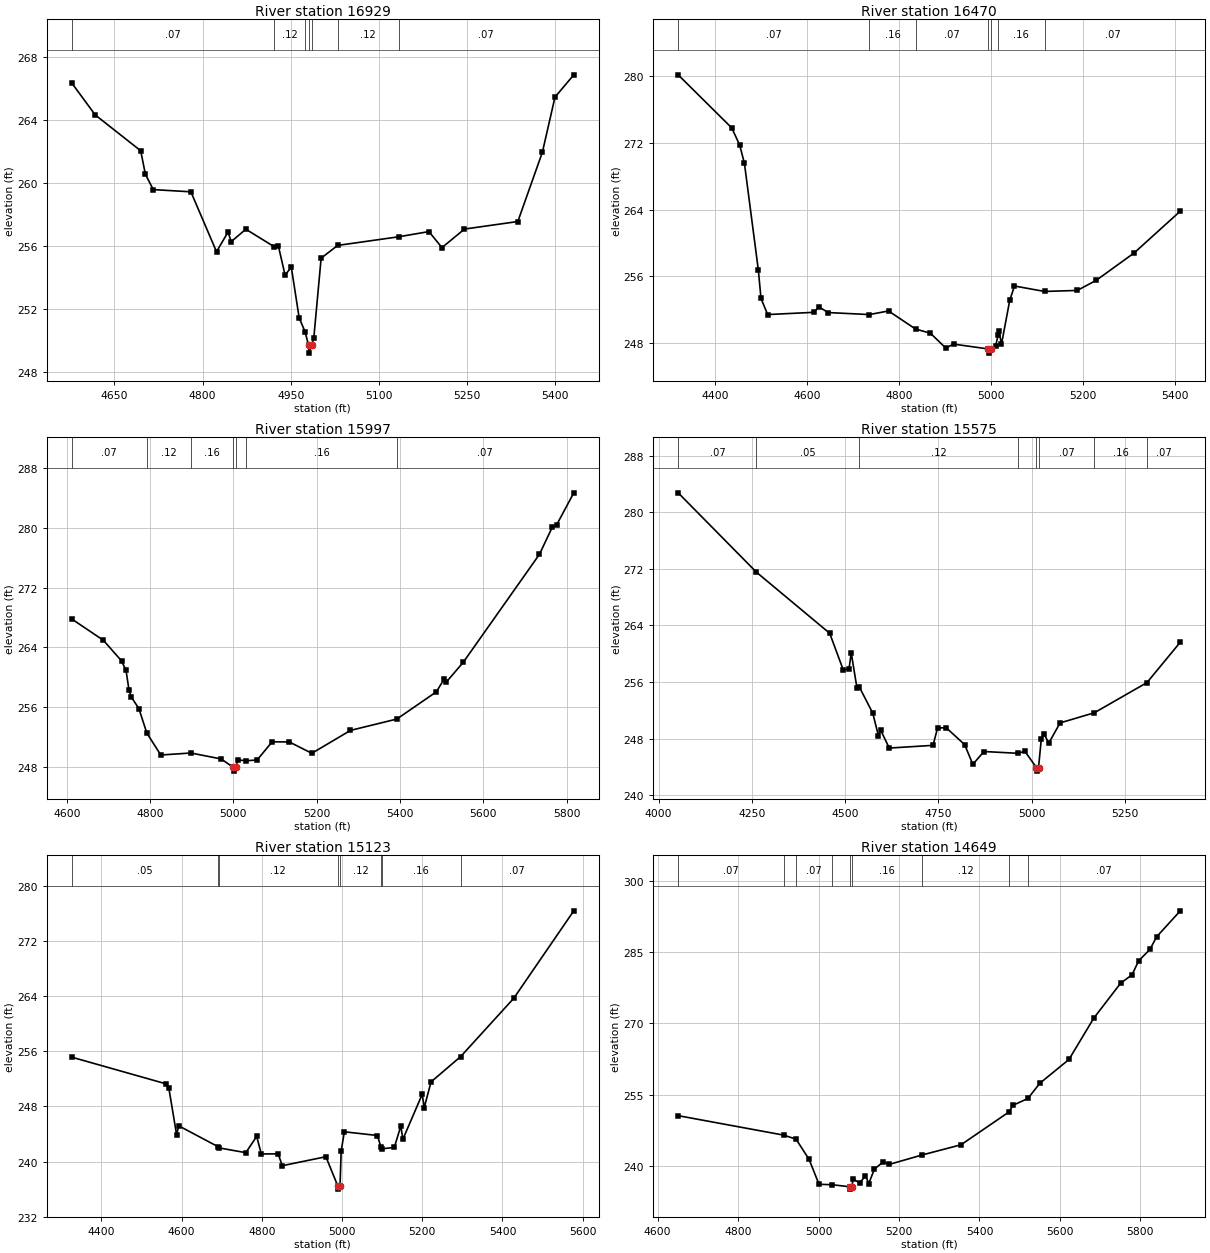
Type RM Length L Ch R = 1,16929,459,459,459
BEGIN DESCRIPTION:
BOGGIE CREEK 3 33.0
END DESCRIPTION:
XS GIS Cut Line= 3
      2479625.01     13630375.00      2479225.00     13630225.00
      2478825.01     13630075.00
#Sta/Elev= 30
  4577.1  266.37  4617.2  264.33  4694.6  262.05  4702.6  260.55  4716.0  259.58
  4780.0  259.44  4823.6  255.63  4843.2  256.88  4848.6  256.27  4873.5  257.06
  4921.3  255.96  4928.7  256.02  4940.2  254.15  4950.9  254.64  4964.3  251.41
  4974.2  250.55  4980.2  249.68  4980.7  249.18  4985.7  249.68  4989.2  250.17
  5001.6  255.22  5029.7  256.03  5133.7  256.58  5185.0  256.91  5207.2  255.89
  5245.5  257.07  5336.3  257.55  5378.1  261.96  5399.5  265.46  5431.5  266.88
#Mann=7,-1,0
  4577.1    0.07       0  4921.3    0.12       0  4974.2    0.16       0
  4980.2    0.07       0  4985.7    0.16       0  5029.7    0.12       0
  5133.7    0.07       0
Bank Sta=4980.2,4985.7
Exp/Cntr=0.3,0.1

Type RM Length L Ch R = 1,16470,473,473,473
BEGIN DESCRIPTION:
BOGGIE CREEK 3 32.0
END DESCRIPTION:
XS GIS Cut Line= 3
      2479997.53     13629977.16      2479325.00     13629875.00
      2478924.95     13629774.99
#Sta/Elev= 30
  4319.7  280.14  4436.3  273.78  4453.7  271.70  4463.9  269.52  4494.2  256.72
  4499.9  253.36  4514.4  251.42  4615.6  251.69  4625.7  252.36  4645.9  251.66
  4735.6  251.42  4777.4  251.85  4836.4  249.68  4868.4  249.19  4902.0  247.41
  4919.0  247.88  4994.6  247.30  4995.1  246.80  5000.3  247.30  5010.2  247.62
  5016.0  248.98  5018.0  249.45  5023.1  247.84  5041.2  253.14  5051.5  254.84
  5116.8  254.19  5188.1  254.31  5229.3  255.52  5311.8  258.80  5412.3  263.81
#Mann=7,-1,0
  4319.7    0.07       0  4735.6    0.16       0  4836.4    0.07       0
  4994.6    0.07       0  5000.3    0.07       0  5016.0    0.16       0
  5116.8    0.07       0
Bank Sta=4994.6,5000.3
Exp/Cntr=0.3,0.1

Type RM Length L Ch R = 1,15997,422,422,422
BEGIN DESCRIPTION:
BOGGIE CREEK 3 31.0
END DESCRIPTION:
XS GIS Cut Line= 3
      2479874.99     13629725.00      2479525.00     13629575.00
      2478725.00     13629375.00
#Sta/Elev= 30
  4611.7  267.81  4687.8  264.95  4731.4  262.19  4742.2  260.93  4749.5  258.23
  4754.9  257.34  4773.1  255.79  4792.2  252.51  4825.7  249.57  4897.9  249.84
  4970.7  249.04  4999.9  247.91  5000.4  247.41  5005.6  247.91  5010.5  248.92
  5030.1  248.80  5056.9  248.90  5093.0  251.34  5134.2  251.32  5188.3  249.80
  5281.1  252.87  5392.3  254.39  5487.3  258.04  5505.3  259.70  5510.4  259.30
  5551.7  261.99  5734.6  276.46  5765.6  280.12  5775.9  280.41  5817.1  284.71
#Mann=7,-1,0
  4611.7    0.07       0  4792.2    0.12       0  4897.9    0.16       0
  4999.9    0.07       0  5005.6    0.16       0  5030.1    0.16       0
  5392.3    0.07       0
Bank Sta=4999.9,5005.6
Exp/Cntr=0.3,0.1

Type RM Length L Ch R = 1,15575,452,452,452
BEGIN DESCRIPTION:
BOGGIE CREEK 3 30.0
END DESCRIPTION:
XS GIS Cut Line= 3
      2480225.04     13629725.02      2479425.00     13629225.00
      2479024.96     13629174.99
#Sta/Elev= 30
  4052.3  282.73  4262.3  271.51  4458.6  262.89  4495.2  257.68  4510.5  257.87
  4516.4  260.11  4531.7  255.18  4538.5  255.25  4574.2  251.60  4589.5  248.36
  4595.4  249.19  4618.4  246.67  4735.7  247.05  4748.1  249.54  4771.7  249.51
  4820.6  247.15  4842.4  244.37  4872.5  246.18  4962.6  245.93  4982.2  246.21
  5013.0  243.91  5013.5  243.41  5018.7  243.91  5026.0  247.89  5033.5  248.67
  5046.1  247.36  5076.4  250.22  5168.5  251.66  5309.5  255.92  5398.9  261.63
#Mann=8,-1,0
  4052.3    0.07       0  4262.3    0.05       0  4538.5    0.12       0
  4962.6    0.07       0  5013.0    0.07       0  5018.7    0.07       0
  5168.5    0.16       0  5309.5    0.07       0
Bank Sta=5013,5018.7
Exp/Cntr=0.3,0.1

Type RM Length L Ch R = 1,15123,474,474,474
BEGIN DESCRIPTION:
BOGGIE CREEK 3 29.0
END DESCRIPTION:
XS GIS Cut Line= 3
      2480075.90     13629079.58      2479425.00     13628875.00
      2478864.95     13628772.76
#Sta/Elev= 30
  4326.1  255.15  4560.5  251.29  4568.1  250.74  4587.7  243.90  4592.9  245.19
  4690.3  242.18  4692.9  241.99  4760.2  241.29  4787.3  243.65  4798.8  241.10
  4840.7  241.12  4851.2  239.40  4959.8  240.70  4989.2  236.50  4989.7  236.00
  4995.1  236.50  4997.9  241.52  5005.8  244.32  5088.3  243.78  5096.7  242.15
  5099.0  241.84  5130.4  242.06  5146.6  245.16  5151.7  243.23  5199.9  249.76
  5205.0  247.84  5221.9  251.56  5295.7  255.23  5428.1  263.69  5577.7  276.38
#Mann=8,-1,0
  4326.1    0.05       0  4690.3    0.07       0  4692.9    0.12       0
  4989.2    0.07       0  4995.1    0.12       0  5096.7    0.07       0
  5099.0    0.16       0  5295.7    0.07       0
Bank Sta=4989.2,4995.1
Exp/Cntr=0.3,0.1

Type RM Length L Ch R = 1,14649,720,720,720
BEGIN DESCRIPTION:
BOGGIE CREEK 3 28.0
END DESCRIPTION:
XS GIS Cut Line= 3
      2479925.00     13628775.00      2479675.00     13628525.00
      2478874.98     13628124.99
#Sta/Elev= 30
  4651.1  250.55  4913.7  246.45  4944.1  245.60  4976.4  241.36  5001.1  236.11
  5034.6  236.01  5077.2  235.59  5077.7  235.09  5083.1  235.59  5085.7  237.27
  5102.5  236.34  5116.5  237.95  5124.8  236.26  5138.8  239.31  5161.2  240.86
  5175.2  240.28  5257.1  242.27  5354.0  244.42  5474.0  251.37  5482.6  252.71
  5520.4  254.17  5549.7  257.35  5622.4  262.38  5683.9  271.06  5750.9  278.44
  5778.9  280.18  5795.7  283.15  5823.6  285.54  5840.4  288.21  5899.1  293.66
#Mann=9,-1,0
  4651.1    0.07       0  4913.7    0.16       0  4944.1    0.07       0
  5034.6    0.16       0  5077.2    0.07       0  5083.1    0.16       0
  5257.1    0.12       0  5474.0    0.16       0  5520.4    0.07       0
Bank Sta=5077.2,5083.1
Exp/Cntr=0.3,0.1

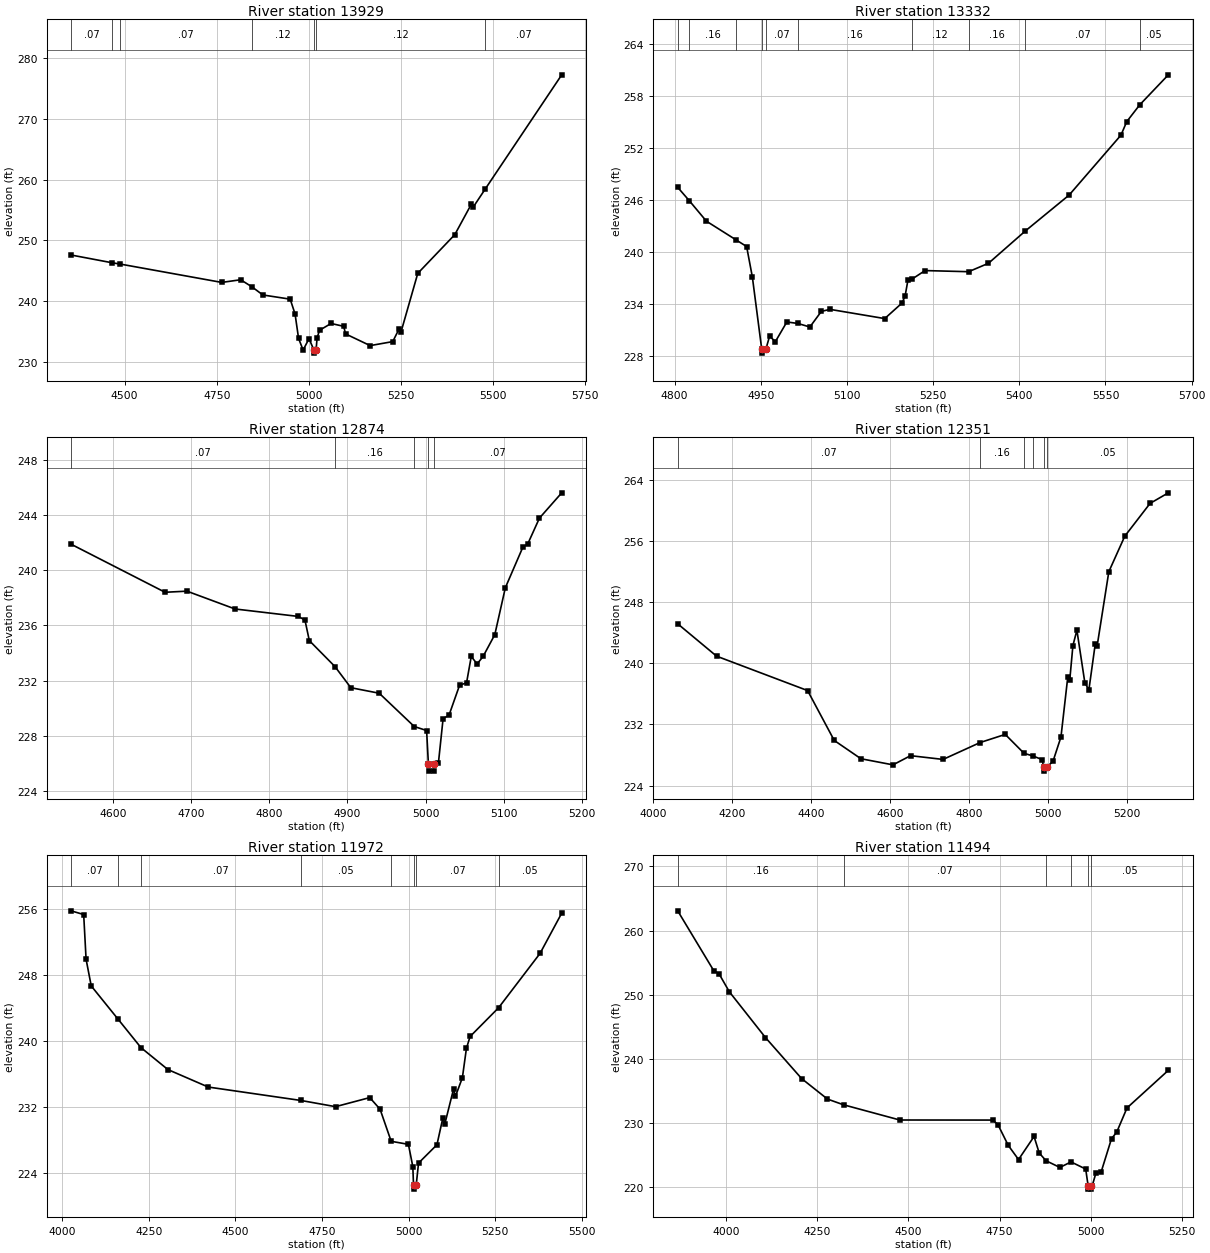
Type RM Length L Ch R = 1,13929,597,597,597
BEGIN DESCRIPTION:
X18313
END DESCRIPTION:
XS GIS Cut Line= 4
      2479899.64     13628603.09      2479791.92     13628142.82
      2479576.50     13628025.32      2478975.96     13627901.29
#Sta/Elev= 30
  4354.6  247.59  4466.8  246.30  4487.5  246.10  4763.4  243.07  4814.8  243.51
  4845.6  242.33  4875.0  241.00  4949.1  240.31  4962.3  237.88  4971.9  233.83
  4984.2  231.92  5000.3  233.80  5013.5  231.91  5014.0  231.41  5019.4  231.91
  5022.1  233.93  5028.8  235.18  5060.1  236.30  5094.3  235.83  5099.4  234.58
  5166.1  232.65  5227.4  233.31  5245.0  235.45  5250.1  234.95  5295.3  244.56
  5395.8  250.95  5440.9  256.00  5446.0  255.51  5477.9  258.43  5685.9  277.30
#Mann=7,-1,0
  4354.6    0.07       0  4466.8    0.16       0  4487.5    0.07       0
  4845.6    0.12       0  5013.5    0.07       0  5019.4    0.12       0
  5477.9    0.07       0
Bank Sta=5013.5,5019.4
Exp/Cntr=0.3,0.1

Type RM Length L Ch R = 1,13332,458,458,458
BEGIN DESCRIPTION:
BOGGIE CREEK 3 27.0
END DESCRIPTION:
XS GIS Cut Line= 3
      2479974.97     13627675.00      2479775.00     13627675.00
      2479122.79     13627725.04
#Sta/Elev= 30
  4805.3  247.47  4825.6  245.92  4855.3  243.57  4906.3  241.44  4925.3  240.65
  4935.3  237.13  4951.5  228.87  4952.0  228.37  4959.0  228.87  4965.3  230.33
  4975.3  229.69  4995.3  231.96  5014.4  231.79  5035.4  231.38  5055.4  233.18
  5070.5  233.41  5165.7  232.35  5195.8  234.14  5201.1  234.93  5206.1  236.78
  5212.8  236.88  5235.9  237.88  5311.7  237.75  5346.3  238.72  5410.6  242.45
  5486.7  246.58  5576.9  253.48  5587.0  255.04  5609.7  256.98  5659.4  260.43
#Mann=10,-1,0
  4805.3    0.07       0  4825.6    0.16       0  4906.3    0.07       0
  4951.5    0.07       0  4959.0    0.07       0  5014.4    0.16       0
  5212.8    0.12       0  5311.7    0.16       0  5410.6    0.07       0
  5609.7    0.05       0
Bank Sta=4951.5,4959
Exp/Cntr=0.3,0.1

Type RM Length L Ch R = 1,12874,523,523,523
BEGIN DESCRIPTION:
BOGGIE CREEK 3 26.0
END DESCRIPTION:
XS GIS Cut Line= 3
      2479825.02     13627274.99      2479425.00     13627475.00
      2479275.01     13627574.99
#Sta/Elev= 30
  4546.6  241.88  4666.8  238.40  4694.8  238.48  4756.3  237.19  4837.3  236.65
  4845.7  236.39  4851.3  234.90  4884.1  233.02  4904.4  231.49  4940.7  231.09
  4985.5  228.68  5001.3  228.39  5003.6  225.95  5004.1  225.45  5010.7  225.45
  5011.2  225.95  5016.4  226.04  5022.4  229.26  5029.9  229.49  5043.4  231.66
  5052.4  231.85  5058.4  233.75  5065.9  233.21  5073.5  233.75  5088.5  235.33
  5102.0  238.73  5124.5  241.68  5130.5  241.88  5145.6  243.77  5174.1  245.60
#Mann=5,-1,0
  4546.6    0.07       0  4884.1    0.16       0  4985.5    0.07       0
  5003.6    0.07       0  5011.2    0.07       0
Bank Sta=5003.6,5011.2
Exp/Cntr=0.3,0.1

Type RM Length L Ch R = 1,12351,379,379,379
BEGIN DESCRIPTION:
BOGGIE CREEK 3 25.0
END DESCRIPTION:
XS GIS Cut Line= 3
      2479975.03     13626874.99      2479178.30     13627264.82
      2478825.83     13627317.03
#Sta/Elev= 30
  4062.1  245.15  4160.6  240.92  4391.3  236.42  4458.8  229.90  4526.4  227.51
  4607.6  226.71  4652.2  227.91  4734.5  227.42  4828.6  229.63  4892.1  230.69
  4939.7  228.22  4962.6  227.87  4986.1  227.38  4989.1  226.39  4989.6  225.89
  4996.7  226.39  5013.1  227.17  5033.3  230.35  5050.6  238.21  5055.6  237.80
  5063.6  242.31  5073.7  244.31  5093.9  237.42  5104.1  236.53  5120.1  242.48
  5125.1  242.30  5154.6  251.96  5195.0  256.60  5259.1  260.89  5305.4  262.27
#Mann=6,-1,0
  4062.1    0.07       0  4828.6    0.16       0  4939.7    0.07       0
  4962.6    0.05       0  4989.1    0.05       0  4996.7    0.05       0
Bank Sta=4989.1,4996.7
Exp/Cntr=0.3,0.1

Type RM Length L Ch R = 1,11972,478,478,478
BEGIN DESCRIPTION:
BOGGIE CREEK 3 24.0
END DESCRIPTION:
XS GIS Cut Line= 3
      2480025.01     13626374.99      2479225.00     13626925.00
      2478806.16     13627075.52
#Sta/Elev= 30
  4025.6  255.76  4062.0  255.31  4068.9  249.89  4083.8  246.65  4160.6  242.65
  4227.3  239.17  4305.0  236.51  4421.4  234.39  4689.2  232.76  4788.8  232.01
  4887.5  233.11  4917.3  231.70  4949.3  227.81  4999.1  227.44  5011.8  224.74
  5013.8  222.51  5014.3  222.01  5021.6  222.51  5028.3  225.17  5081.4  227.39
  5098.7  230.69  5104.0  229.89  5129.4  234.16  5134.7  233.25  5154.8  235.52
  5166.5  239.08  5177.1  240.52  5259.2  244.00  5379.0  250.60  5441.5  255.48
#Mann=8,-1,0
  4025.6    0.07       0  4160.6    0.16       0  4227.3    0.07       0
  4689.2    0.05       0  4949.3    0.07       0  5013.8    0.07       0
  5021.6    0.07       0  5259.2    0.05       0
Bank Sta=5013.8,5021.6
Exp/Cntr=0.3,0.1

Type RM Length L Ch R = 1,11494,420,420,420
BEGIN DESCRIPTION:
BOGGIE CREEK 3 23.0
END DESCRIPTION:
XS GIS Cut Line= 3
      2479824.98     13625725.02      2479025.00     13626525.00
      2478874.98     13626675.02
#Sta/Elev= 30
  3868.4  263.08  3967.4  253.73  3981.5  253.28  4009.8  250.47  4108.8  243.33
  4207.8  236.94  4278.5  233.75  4322.5  232.86  4476.5  230.49  4731.0  230.48
  4745.2  229.78  4773.5  226.54  4801.7  224.33  4844.2  227.92  4858.3  225.35
  4877.1  224.14  4914.9  223.10  4945.4  223.96  4985.6  222.85  4992.3  220.22
  4992.8  219.72  4999.6  219.72  5000.1  220.22  5003.3  220.22  5013.9  222.28
  5028.0  222.41  5056.3  227.59  5070.4  228.58  5098.7  232.37  5211.9  238.23
#Mann=6,-1,0
  3868.4    0.16       0  4322.5    0.07       0  4877.1    0.16       0
  4945.4    0.05       0  4992.3    0.05       0  5000.1    0.05       0
Bank Sta=4992.3,5000.1
Exp/Cntr=0.3,0.1