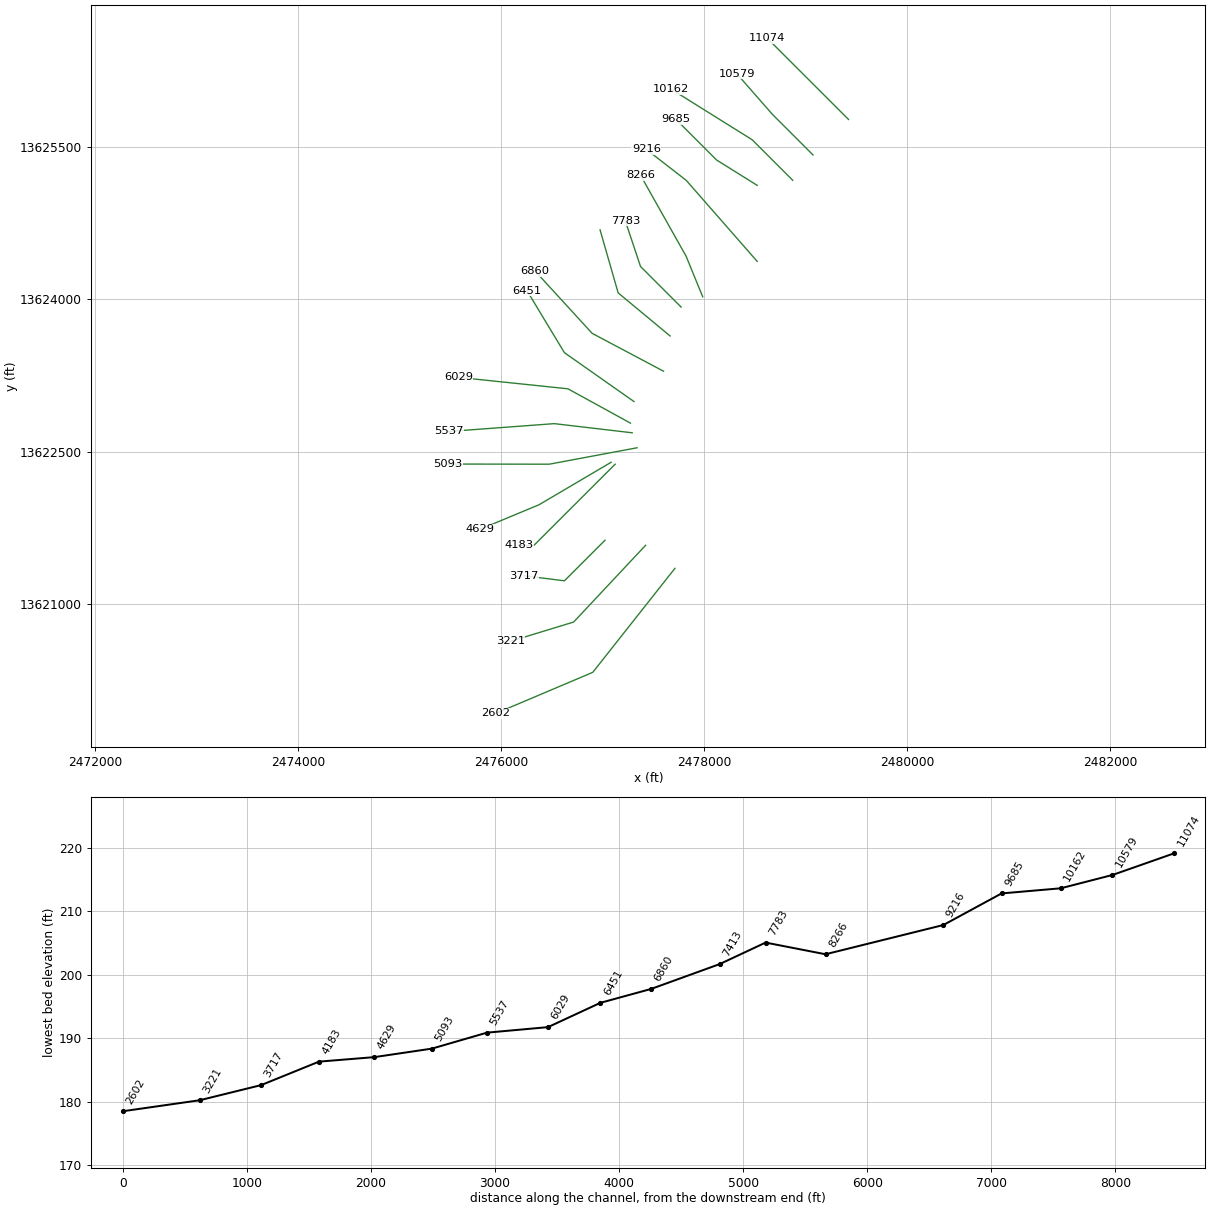
HEC-RAS study BOGGIE CREEK.prj: BOGGIE CREEK Base Level Engineering

--- BOGGIE CREEK.g01 (geometry) --- (continued)

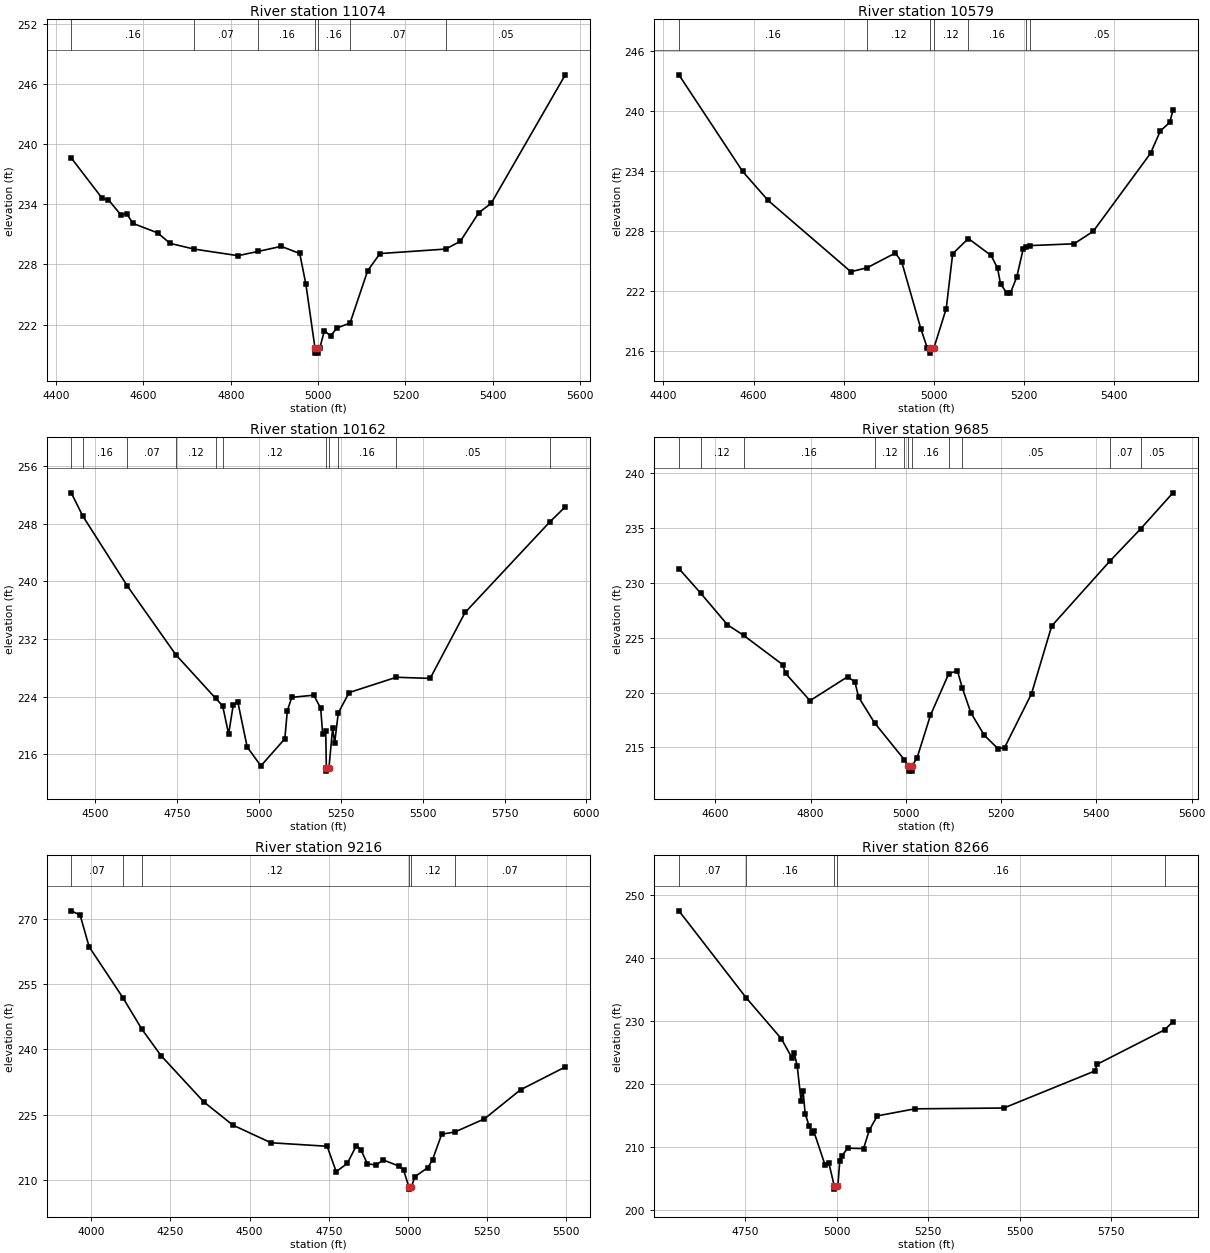
Type RM Length L Ch R = 1,11074,495,495,495
BEGIN DESCRIPTION:
BOGGIE CREEK 3 22.0
END DESCRIPTION:
XS GIS Cut Line= 3
      2479425.01     13625774.99      2479025.00     13626175.00
      2478624.99     13626575.01
#Sta/Elev= 30
  4434.6  238.62  4505.3  234.60  4519.5  234.46  4547.8  232.96  4561.9  233.04
  4576.0  232.09  4632.6  231.14  4660.9  230.10  4715.7  229.53  4816.5  228.87
  4863.2  229.30  4915.4  229.80  4957.9  229.09  4972.0  226.01  4992.8  219.65
  4993.3  219.15  5000.2  219.15  5000.7  219.65  5003.8  219.65  5014.4  221.40
  5028.6  220.85  5042.7  221.65  5073.1  222.15  5113.4  227.37  5141.7  229.08
  5291.9  229.53  5325.6  230.30  5368.0  233.16  5396.3  234.09  5566.0  246.91
#Mann=7,-1,0
  4434.6    0.16       0  4715.7    0.07       0  4863.2    0.16       0
  4992.8    0.07       0  5000.7    0.16       0  5073.1    0.07       0
  5291.9    0.05       0
Bank Sta=4992.8,5000.7
Exp/Cntr=0.3,0.1

Type RM Length L Ch R = 1,10579,417,417,417
BEGIN DESCRIPTION:
BOGGIE CREEK 3 21.0
END DESCRIPTION:
XS GIS Cut Line= 3
      2479075.03     13625424.97      2478675.00     13625825.00
      2478325.02     13626224.98
#Sta/Elev= 30
  4434.3  243.65  4575.8  233.97  4632.3  231.06  4816.2  223.91  4852.3  224.31
  4915.2  225.79  4929.3  224.87  4971.7  218.18  4985.9  216.27  4992.5  216.25
  4993.0  215.75  5000.5  216.25  5028.0  220.21  5042.3  225.71  5077.1  227.24
  5127.7  225.54  5141.9  224.28  5148.6  222.69  5162.8  221.75  5170.4  221.76
  5184.6  223.37  5198.9  226.18  5204.8  226.35  5213.8  226.53  5311.8  226.71
  5354.5  227.96  5481.7  235.78  5503.5  238.02  5524.4  238.88  5531.5  240.10
#Mann=7,-1,0
  4434.3    0.16       0  4852.3    0.12       0  4992.5    0.07       0
  5000.5    0.12       0  5077.1    0.16       0  5204.8    0.07       0
  5213.8    0.05       0
Bank Sta=4992.5,5000.5
Exp/Cntr=0.3,0.1

Type RM Length L Ch R = 1,10162,477,477,477
BEGIN DESCRIPTION:
BOGGIE CREEK 3 20.0
END DESCRIPTION:
XS GIS Cut Line= 3
      2478875.00     13625175.00      2478475.00     13625575.00
      2477674.99     13626075.01
#Sta/Elev= 30
  4426.4  252.31  4461.5  249.10  4597.0  239.42  4745.7  229.83  4867.9  223.74
  4888.9  222.72  4907.2  218.79  4921.4  222.90  4935.5  223.21  4963.8  217.00
  5005.7  214.38  5078.8  218.14  5086.4  222.02  5100.0  223.90  5167.2  224.20
  5188.4  222.39  5194.3  218.85  5203.8  219.23  5205.6  214.15  5206.1  213.65
  5213.7  214.15  5225.0  219.67  5230.9  217.53  5242.1  221.73  5275.1  224.56
  5419.4  226.69  5522.8  226.53  5629.5  235.69  5888.3  248.27  5935.5  250.36
#Mann=11,-1,0
  4426.4    0.07       0  4461.5    0.16       0  4597.0    0.07       0
  4745.7    0.12       0  4867.9    0.07       0  4888.9    0.12       0
  5205.6    0.07       0  5213.7    0.12       0  5242.1    0.16       0
  5419.4    0.05       0  5888.3    0.07       0
Bank Sta=5205.6,5213.7
Exp/Cntr=0.3,0.1

Type RM Length L Ch R = 1,9685,469,469,469
BEGIN DESCRIPTION:
BOGGIE CREEK 3 19.0
END DESCRIPTION:
XS GIS Cut Line= 3
      2478524.99     13625125.01      2478125.00     13625375.00
      2477724.98     13625775.02
#Sta/Elev= 30
  4523.3  231.29  4569.2  229.04  4625.3  226.17  4659.4  225.20  4740.9  222.55
  4747.3  221.74  4798.6  219.26  4877.7  221.44  4893.0  220.96  4900.6  219.58
  4934.1  217.24  4996.7  213.88  5005.0  213.34  5005.5  212.84  5012.7  212.84
  5013.2  213.34  5023.3  214.03  5051.6  217.94  5090.1  221.73  5108.1  221.98
  5118.7  220.38  5136.4  218.15  5164.7  216.10  5193.0  214.90  5207.1  214.98
  5263.7  219.89  5306.1  226.06  5427.6  231.94  5493.1  234.92  5560.7  238.19
#Mann=11,-1,0
  4523.3    0.07       0  4569.2    0.12       0  4659.4    0.16       0
  4934.1    0.12       0  4996.7    0.16       0  5005.0    0.07       0
  5013.2    0.16       0  5090.1    0.12       0  5118.7    0.05       0
  5427.6    0.07       0  5493.1    0.05       0
Bank Sta=5005,5013.2
Exp/Cntr=0.3,0.1

Type RM Length L Ch R = 1,9216,950,950,950
BEGIN DESCRIPTION:
BOGGIE CREEK 3 18.0
END DESCRIPTION:
XS GIS Cut Line= 3
      2478524.98     13624375.02      2477825.00     13625175.00
      2477432.35     13625479.72
#Sta/Elev= 30
  3936.9  271.83  3964.9  270.86  3993.3  263.57  4100.2  251.84  4159.4  244.68
  4220.2  238.57  4355.0  227.94  4447.0  222.59  4567.6  218.52  4745.0  217.71
  4773.5  211.88  4808.6  213.77  4837.1  217.85  4851.3  216.95  4872.2  213.66
  4900.2  213.41  4921.6  214.58  4971.9  213.15  4986.1  212.33  5002.9  208.36
  5003.4  207.86  5011.3  208.36  5021.6  210.70  5063.2  212.82  5077.7  214.61
  5106.7  220.49  5148.1  220.99  5241.6  224.01  5355.6  230.70  5496.9  235.94
#Mann=6,-1,0
  3936.9    0.07       0  4100.2    0.16       0  4159.4    0.12       0
  5002.9    0.07       0  5011.3    0.12       0  5148.1    0.07       0
Bank Sta=5002.9,5011.3
Exp/Cntr=0.3,0.1

Type RM Length L Ch R = 1,8266,483,483,483
BEGIN DESCRIPTION:
BOGGIE CREEK 3 17.0
END DESCRIPTION:
XS GIS Cut Line= 3
      2477987.87     13624025.76      2477825.00     13624425.00
      2477374.98     13625225.03
#Sta/Elev= 30
  4568.9  247.51  4752.5  233.69  4848.9  227.15  4878.4  224.04  4883.8  224.93
  4892.1  222.76  4902.5  217.32  4907.9  218.90  4913.7  215.25  4924.5  213.30
  4931.9  212.11  4937.3  212.43  4967.7  207.14  4978.5  207.38  4993.1  203.75
  4993.6  203.25  5001.6  203.75  5003.0  203.75  5008.1  207.68  5013.8  208.52
  5029.7  209.76  5073.1  209.70  5089.0  212.65  5110.7  214.90  5213.3  216.02
  5456.2  216.15  5704.7  222.04  5711.4  223.12  5895.5  228.59  5918.0  229.88
#Mann=5,-1,0
  4568.9    0.07       0  4752.5    0.16       0  4993.1    0.07       0
  5001.6    0.16       0  5895.5    0.07       0
Bank Sta=4993.1,5001.6
Exp/Cntr=0.3,0.1

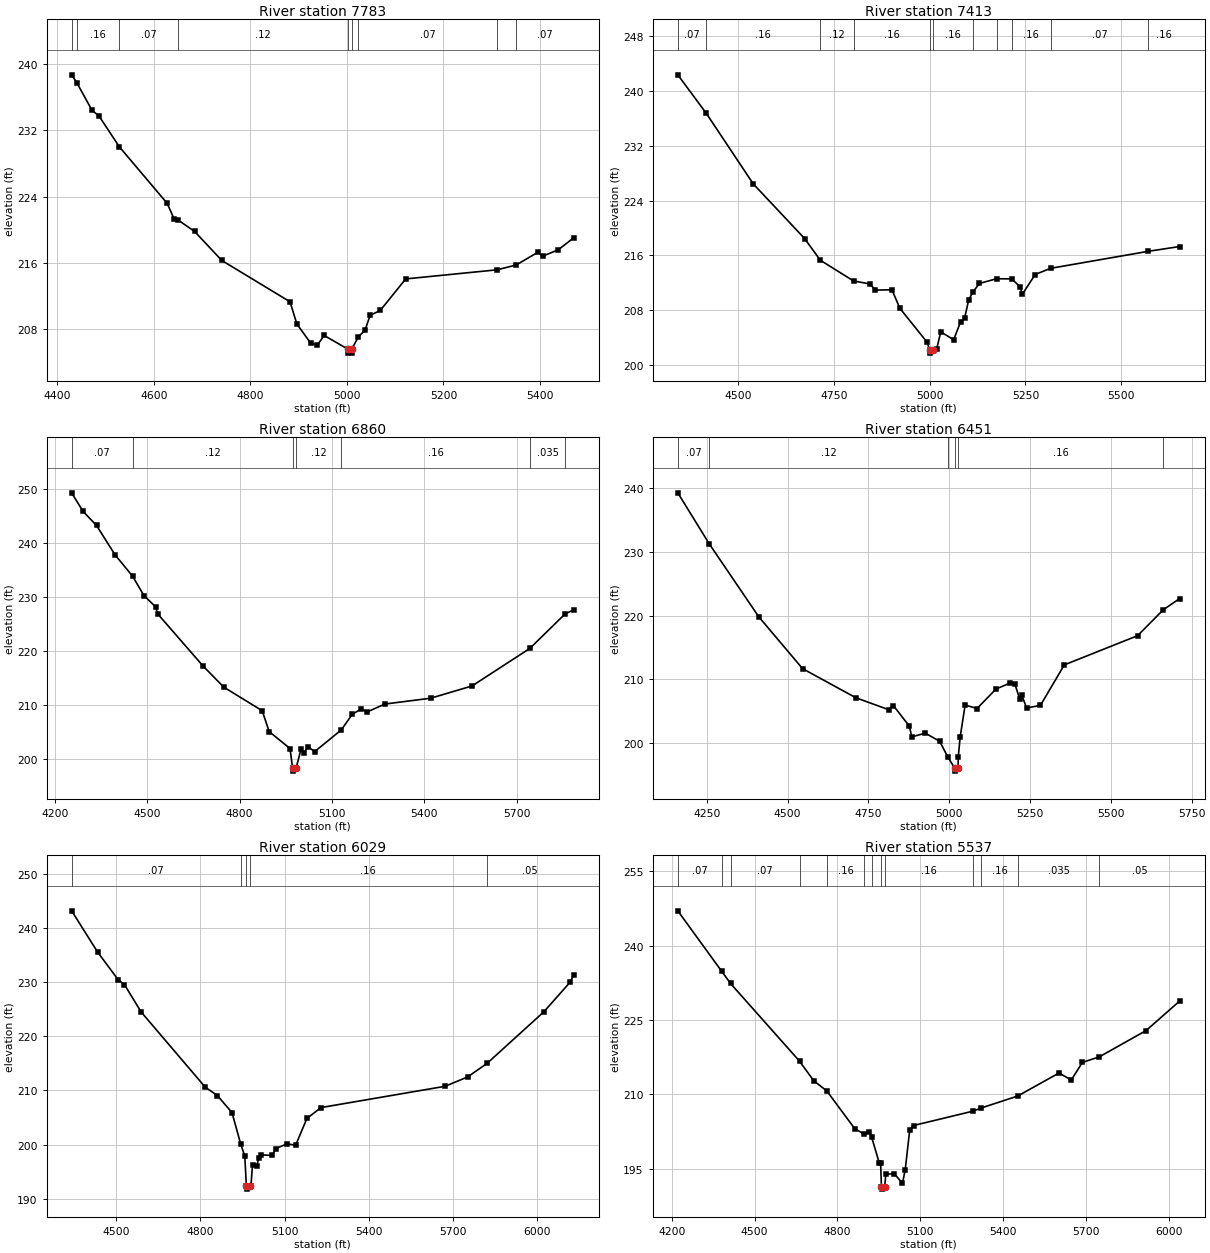
Type RM Length L Ch R = 1,7783,370,370,370
BEGIN DESCRIPTION:
BOGGIE CREEK 3 16.0
END DESCRIPTION:
XS GIS Cut Line= 3
      2477775.00     13623925.00      2477375.00     13624325.00
      2477225.01     13624774.98
#Sta/Elev= 30
  4429.7  238.69  4440.4  237.74  4472.1  234.39  4486.3  233.73  4528.3  230.02
  4627.7  223.17  4641.8  221.32  4650.5  221.15  4684.3  219.79  4740.8  216.28
  4882.2  211.29  4896.4  208.61  4924.7  206.32  4938.8  206.06  4953.0  207.22
  5001.6  205.59  5002.1  205.09  5009.7  205.09  5010.2  205.59  5024.1  207.08
  5037.5  207.83  5048.1  209.65  5069.2  210.24  5121.9  214.05  5311.5  215.15
  5350.7  215.73  5395.9  217.27  5406.5  216.81  5438.1  217.57  5469.7  219.00
#Mann=9,-1,0
  4429.7    0.07       0  4440.4    0.16       0  4528.3    0.07       0
  4650.5    0.12       0  5001.6    0.07       0  5010.2    0.12       0
  5024.1    0.07       0  5311.5    0.16       0  5350.7    0.07       0
Bank Sta=5001.6,5010.2
Exp/Cntr=0.3,0.1

Type RM Length L Ch R = 1,7413,553,553,553
BEGIN DESCRIPTION:
X18314
END DESCRIPTION:
XS GIS Cut Line= 3
      2477666.70     13623639.47      2477154.54     13624064.82
      2476976.59     13624685.46
#Sta/Elev= 30
  4341.8  242.37  4415.9  236.77  4539.0  226.43  4673.4  218.43  4714.1  215.28
  4800.9  212.25  4844.0  211.81  4858.3  210.91  4901.3  210.96  4922.1  208.25
  4993.7  203.26  4999.7  202.20  5000.2  201.70  5008.4  202.20  5018.1  202.28
  5028.9  204.81  5062.6  203.66  5080.6  206.26  5091.0  206.77  5101.6  209.42
  5112.4  210.60  5130.1  211.89  5174.8  212.57  5214.1  212.55  5236.6  211.38
  5241.8  210.28  5275.5  213.19  5315.7  214.09  5571.1  216.58  5653.2  217.28
#Mann=11,-1,0
  4341.8    0.07       0  4415.9    0.16       0  4714.1    0.12       0
  4800.9    0.16       0  4999.7    0.07       0  5008.4    0.16       0
  5112.4    0.07       0  5174.8    0.12       0  5214.1    0.16       0
  5315.7    0.07       0  5571.1    0.16       0
Bank Sta=4999.7,5008.4
Exp/Cntr=0.3,0.1

Type RM Length L Ch R = 1,6860,409,409,409
BEGIN DESCRIPTION:
BOGGIE CREEK 3 15.0
END DESCRIPTION:
XS GIS Cut Line= 3
      2477601.61     13623292.23      2476898.46     13623665.51
      2476335.09     13624280.89
#Sta/Elev= 30
  4254.2  249.35  4291.0  245.93  4335.0  243.30  4395.3  237.86  4452.5  233.88
  4488.9  230.32  4527.2  228.21  4533.4  226.94  4681.1  217.26  4748.5  213.34
  4873.3  208.97  4895.7  205.12  4963.6  201.97  4972.1  198.28  4972.6  197.78
  4983.0  198.28  4999.6  201.89  5008.9  201.10  5021.6  202.33  5043.5  201.39
  5129.8  205.40  5165.7  208.30  5194.0  209.28  5215.0  208.77  5271.7  210.21
  5420.3  211.29  5554.8  213.56  5742.7  220.52  5857.7  226.94  5884.6  227.65
#Mann=7,-1,0
  4254.2    0.07       0  4452.5    0.12       0  4972.1    0.07       0
  4983.0    0.12       0  5129.8    0.16       0  5742.7   0.035       0
  5857.7    0.16       0
Bank Sta=4972.1,4983
Exp/Cntr=0.3,0.1

Type RM Length L Ch R = 1,6451,422,422,422
BEGIN DESCRIPTION:
BOGGIE CREEK 3 14.0
END DESCRIPTION:
XS GIS Cut Line= 3
      2477310.77     13622992.78      2476625.00     13623475.00
      2476256.11     13624086.51
#Sta/Elev= 30
  4160.6  239.29  4258.1  231.26  4411.3  219.81  4546.6  211.68  4711.9  207.10
  4812.9  205.24  4827.7  205.87  4876.7  202.66  4884.4  200.97  4926.2  201.55
  4970.6  200.28  4995.2  197.86  5016.7  196.09  5017.2  195.59  5027.7  196.09
  5028.1  197.81  5034.0  200.93  5049.4  205.97  5086.3  205.42  5144.5  208.47
  5187.2  209.40  5202.8  209.33  5218.3  206.93  5224.1  207.59  5239.6  205.50
  5282.4  205.92  5356.1  212.27  5582.9  216.86  5662.4  220.93  5713.1  222.69
#Mann=6,-1,0
  4160.6    0.07       0  4258.1    0.12       0  4995.2    0.16       0
  5016.7    0.07       0  5027.7    0.16       0  5662.4   0.035       0
Bank Sta=5016.7,5027.7
Exp/Cntr=0.3,0.1

Type RM Length L Ch R = 1,6029,492,492,492
BEGIN DESCRIPTION:
BOGGIE CREEK 3 13.0
END DESCRIPTION:
XS GIS Cut Line= 3
      2477276.09     13622780.08      2476659.75     13623118.64
      2475579.53     13623231.43
#Sta/Elev= 30
  4341.0  243.15  4433.5  235.54  4507.3  230.40  4529.1  229.54  4588.8  224.47
  4817.1  210.60  4860.7  209.03  4912.7  205.89  4943.8  200.07  4958.3  197.84
  4964.0  192.26  4964.5  191.76  4975.6  192.26  4980.1  192.33  4985.8  196.13
  5001.9  196.09  5007.6  197.54  5015.4  198.09  5055.7  197.98  5069.1  199.25
  5109.3  200.13  5139.5  199.86  5179.7  204.81  5230.0  206.82  5672.4  210.75
  5752.8  212.48  5822.0  214.98  6024.8  224.52  6118.2  229.98  6130.3  231.27
#Mann=5,-1,0
  4341.0    0.07       0  4943.8    0.16       0  4964.0    0.07       0
  4975.6    0.16       0  5822.0    0.05       0
Bank Sta=4964,4975.6
Exp/Cntr=0.3,0.1

Type RM Length L Ch R = 1,5537,444,444,444
BEGIN DESCRIPTION:
BOGGIE CREEK 3 12.0
END DESCRIPTION:
XS GIS Cut Line= 3
      2477293.45     13622684.61      2476525.00     13622775.00
      2475483.52     13622697.63
#Sta/Elev= 30
  4222.1  247.06  4381.0  234.87  4413.1  232.40  4663.0  216.72  4713.9  212.81
  4762.4  210.67  4863.7  203.04  4897.2  202.04  4915.3  202.45  4924.2  201.41
  4951.8  196.19  4956.8  196.17  4959.8  191.39  4960.3  190.89  4971.4  191.39
  4975.7  193.88  5005.9  194.02  5036.0  192.07  5046.0  194.83  5062.2  202.82
  5076.1  203.73  5292.2  206.64  5320.4  207.25  5453.7  209.69  5602.9  214.32
  5647.6  212.93  5687.8  216.47  5749.1  217.59  5918.4  222.89  6040.2  228.86
#Mann=13,-1,0
  4222.1    0.07       0  4381.0   0.035       0  4413.1    0.07       0
  4663.0   0.035       0  4762.4    0.16       0  4897.2   0.035       0
  4924.2    0.16       0  4959.8    0.07       0  4971.4    0.16       0
  5292.2    0.12       0  5320.4    0.16       0  5453.7   0.035       0
  5749.1    0.05       0
Bank Sta=4959.8,4971.4
Exp/Cntr=0.3,0.1

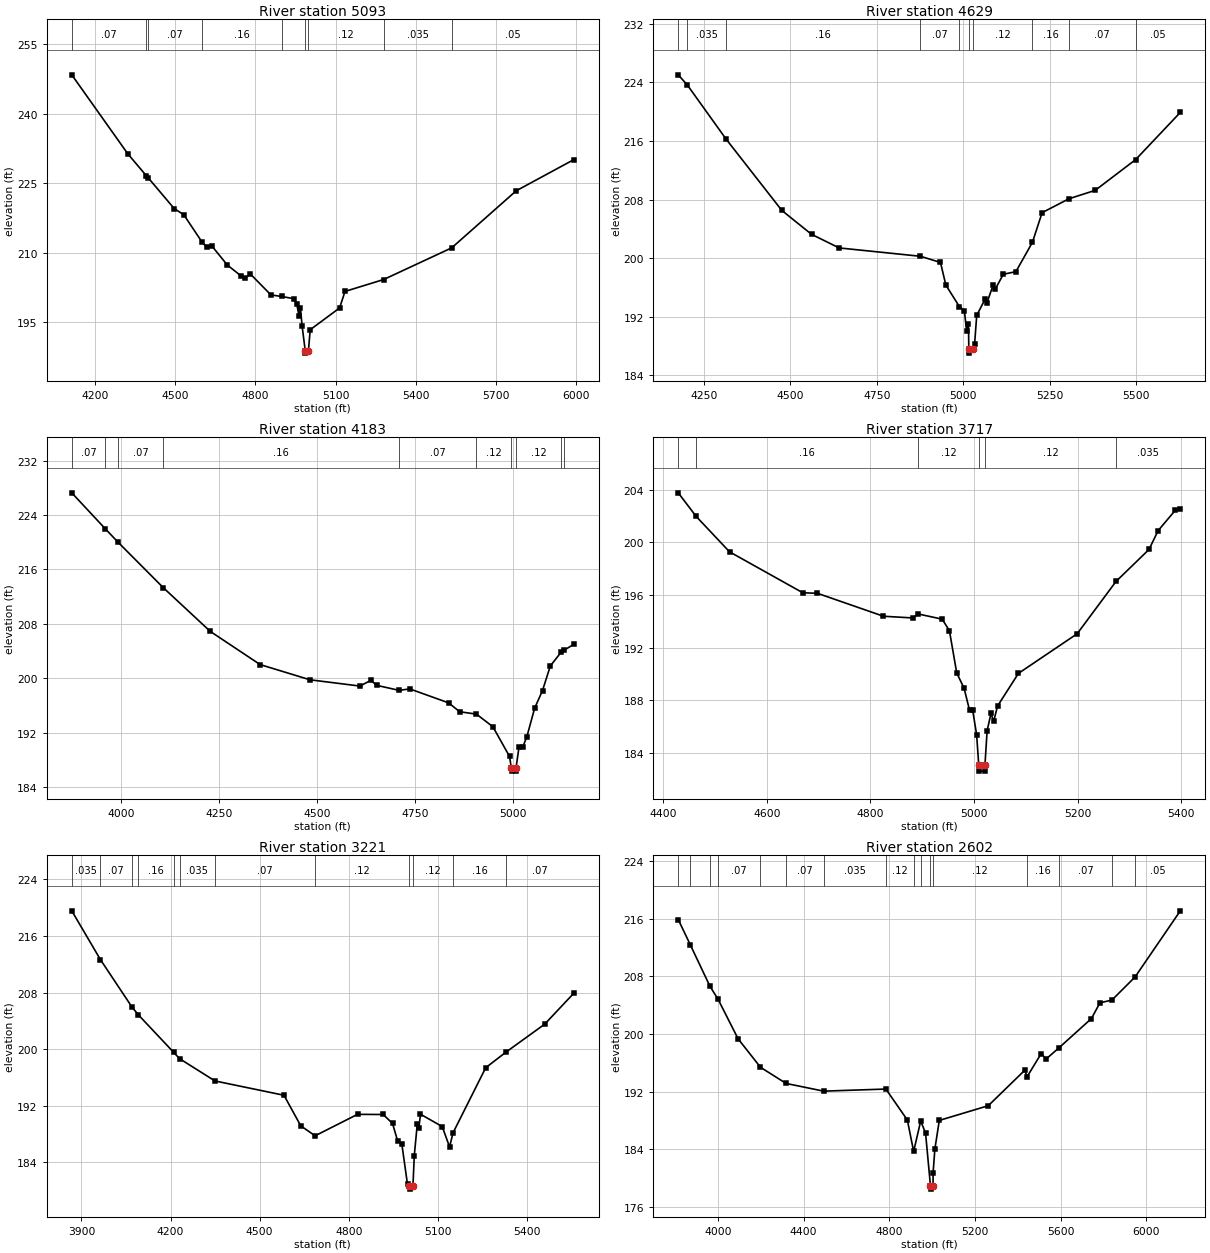
Type RM Length L Ch R = 1,5093,464,464,464
BEGIN DESCRIPTION:
BOGGIE CREEK 3 11.0
END DESCRIPTION:
XS GIS Cut Line= 3
      2477341.13     13622537.03      2476475.00     13622375.00
      2475479.56     13622376.45
#Sta/Elev= 30
  4114.1  248.44  4323.8  231.37  4392.2  226.70  4400.6  226.15  4496.8  219.58
  4532.7  218.25  4599.7  212.45  4618.8  211.22  4637.9  211.49  4695.6  207.38
  4748.3  204.97  4761.3  204.50  4781.6  205.45  4858.6  200.93  4898.4  200.60
  4944.4  200.12  4954.6  199.06  4963.9  196.32  4968.9  198.08  4974.9  194.28
  4986.8  188.87  4987.3  188.37  4998.6  188.87  5005.3  193.42  5115.3  198.13
  5135.3  201.69  5279.5  204.25  5534.1  211.09  5775.3  223.41  5990.7  230.14
#Mann=9,-1,0
  4114.1    0.07       0  4392.2   0.035       0  4400.6    0.07       0
  4599.7    0.16       0  4898.4    0.12       0  4986.8    0.07       0
  4998.6    0.12       0  5279.5   0.035       0  5534.1    0.05       0
Bank Sta=4986.8,4998.6
Exp/Cntr=0.3,0.1

Type RM Length L Ch R = 1,4629,446,446,446
BEGIN DESCRIPTION:
BOGGIE CREEK 3 10.0
END DESCRIPTION:
XS GIS Cut Line= 3
      2477085.13     13622393.83      2476375.00     13621975.00
      2475796.06     13621734.10
#Sta/Elev= 30
  4176.1  225.02  4202.4  223.63  4314.7  216.23  4475.6  206.51  4561.4  203.25
  4641.4  201.39  4876.4  200.25  4934.2  199.41  4949.8  196.32  4988.8  193.39
  5003.3  192.83  5009.8  190.08  5015.2  191.01  5016.2  187.53  5016.7  187.03
  5028.2  187.53  5033.0  188.33  5039.0  192.18  5062.9  194.37  5068.3  193.86
  5086.7  196.35  5092.1  195.73  5116.0  197.80  5152.2  198.15  5200.1  202.16
  5228.0  206.20  5305.5  208.10  5381.5  209.25  5498.5  213.45  5627.6  219.89
#Mann=10,-1,0
  4176.1    0.07       0  4202.4   0.035       0  4314.7    0.16       0
  4876.4    0.07       0  4988.8    0.12       0  5016.2    0.07       0
  5028.2    0.12       0  5200.1    0.16       0  5305.5    0.07       0
  5498.5    0.05       0
Bank Sta=5016.2,5028.2
Exp/Cntr=0.3,0.1

Type RM Length L Ch R = 1,4183,466,466,466
BEGIN DESCRIPTION:
BOGGIE CREEK 3 9.0
END DESCRIPTION:
XS GIS Cut Line= 3
      2477125.00     13622375.00      2476325.00     13621575.00
      2476174.98     13621575.00
#Sta/Elev= 30
  3873.4  227.28  3959.2  221.97  3991.7  220.00  4106.6  213.34  4227.0  206.88
  4354.2  202.00  4481.5  199.76  4608.8  198.84  4637.1  199.69  4651.2  198.95
  4708.7  198.21  4736.1  198.42  4835.1  196.37  4863.4  195.06  4906.2  194.71
  4948.2  192.85  4990.6  188.49  4995.2  186.82  4995.7  186.32  5006.8  186.32
  5007.3  186.82  5014.8  189.84  5024.8  189.93  5034.8  191.37  5054.8  195.59
  5074.8  198.18  5094.8  201.80  5122.2  203.82  5129.9  204.12  5154.8  204.98
#Mann=10,-1,0
  3873.4    0.07       0  3959.2   0.035       0  3991.7    0.07       0
  4106.6    0.16       0  4708.7    0.07       0  4906.2    0.12       0
  4995.2    0.07       0  5007.3    0.12       0  5122.2    0.07       0
  5129.9    0.05       0
Bank Sta=4995.2,5007.3
Exp/Cntr=0.3,0.1

Type RM Length L Ch R = 1,3717,496,496,496
BEGIN DESCRIPTION:
BOGGIE CREEK 3 8.0
END DESCRIPTION:
XS GIS Cut Line= 3
      2477025.03     13621625.03      2476625.00     13621225.00
      2476225.04     13621274.99
#Sta/Elev= 30
  4429.2  203.75  4463.8  201.96  4528.2  199.27  4669.7  196.16  4697.9  196.12
  4825.2  194.38  4881.8  194.25  4892.4  194.55  4938.4  194.16  4952.5  193.28
  4966.6  190.07  4980.8  188.91  4991.4  187.23  4997.4  187.23  5005.0  185.37
  5009.0  183.12  5009.5  182.62  5020.6  182.62  5021.1  183.12  5025.2  185.68
  5032.7  187.01  5037.8  186.39  5045.3  187.56  5085.6  190.04  5199.0  193.05
  5273.9  197.02  5337.6  199.45  5355.2  200.88  5388.0  202.41  5398.0  202.50
#Mann=6,-1,0
  4429.2    0.07       0  4463.8    0.16       0  4892.4    0.12       0
  5009.0    0.07       0  5021.1    0.12       0  5273.9   0.035       0
Bank Sta=5009,5021.1
Exp/Cntr=0.3,0.1

Type RM Length L Ch R = 1,3221,619,619,619
BEGIN DESCRIPTION:
BOGGIE CREEK 3 7.0
END DESCRIPTION:
XS GIS Cut Line= 3
      2477424.98     13621574.98      2476716.17     13620818.29
      2476091.22     13620627.33
#Sta/Elev= 30
  3867.4  219.57  3964.1  212.66  4070.2  205.96  4091.7  204.86  4209.9  199.59
  4230.4  198.67  4349.6  195.52  4581.8  193.50  4638.4  189.17  4686.6  187.77
  4829.4  190.80  4915.9  190.78  4947.3  189.51  4964.9  186.98  4978.6  186.60
  4997.7  180.89  5004.0  180.73  5004.5  180.23  5016.1  180.73  5020.5  184.97
  5030.5  189.37  5035.7  188.82  5041.4  190.82  5114.6  189.07  5139.3  186.20
  5151.1  188.20  5261.0  197.39  5328.7  199.58  5459.6  203.55  5557.7  207.93
#Mann=12,-1,0
  3867.4   0.035       0  3964.1    0.07       0  4070.2   0.035       0
  4091.7    0.16       0  4209.9    0.07       0  4230.4   0.035       0
  4349.6    0.07       0  4686.6    0.12       0  5004.0    0.07       0
  5016.1    0.12       0  5151.1    0.16       0  5328.7    0.07       0
Bank Sta=5004,5016.1
Exp/Cntr=0.3,0.1

Type RM Length L Ch R = 1,2602,684,684,684
BEGIN DESCRIPTION:
X18315
END DESCRIPTION:
XS GIS Cut Line= 3
      2477714.21     13621347.90      2476904.41     13620322.15
      2475949.47     13619917.52
#Sta/Elev= 30
  3814.8  215.89  3870.8  212.41  3962.6  206.65  4001.0  204.82  4094.2  199.35
  4198.8  195.40  4318.2  193.16  4493.7  192.09  4784.3  192.38  4884.5  188.08
  4913.8  183.73  4946.8  187.95  4969.5  186.26  4992.2  179.00  4992.7  178.50
  5004.4  179.00  5004.7  180.76  5012.8  184.04  5033.6  188.03  5262.2  190.07
  5432.7  194.99  5443.5  194.09  5509.1  197.29  5532.8  196.56  5592.0  198.09
  5743.9  202.16  5783.5  204.34  5839.5  204.72  5947.7  207.93  6158.8  217.10
#Mann=16,-1,0
  3814.8   0.035       0  3870.8    0.07       0  3962.6   0.035       0
  4001.0    0.07       0  4198.8   0.035       0  4318.2    0.07       0
  4493.7   0.035       0  4784.3    0.12       0  4913.8    0.16       0
  4946.8    0.12       0  4992.2    0.07       0  5004.4    0.12       0
  5443.5    0.16       0  5592.0    0.07       0  5839.5   0.035       0
  5947.7    0.05       0
Bank Sta=4992.2,5004.4
Exp/Cntr=0.3,0.1