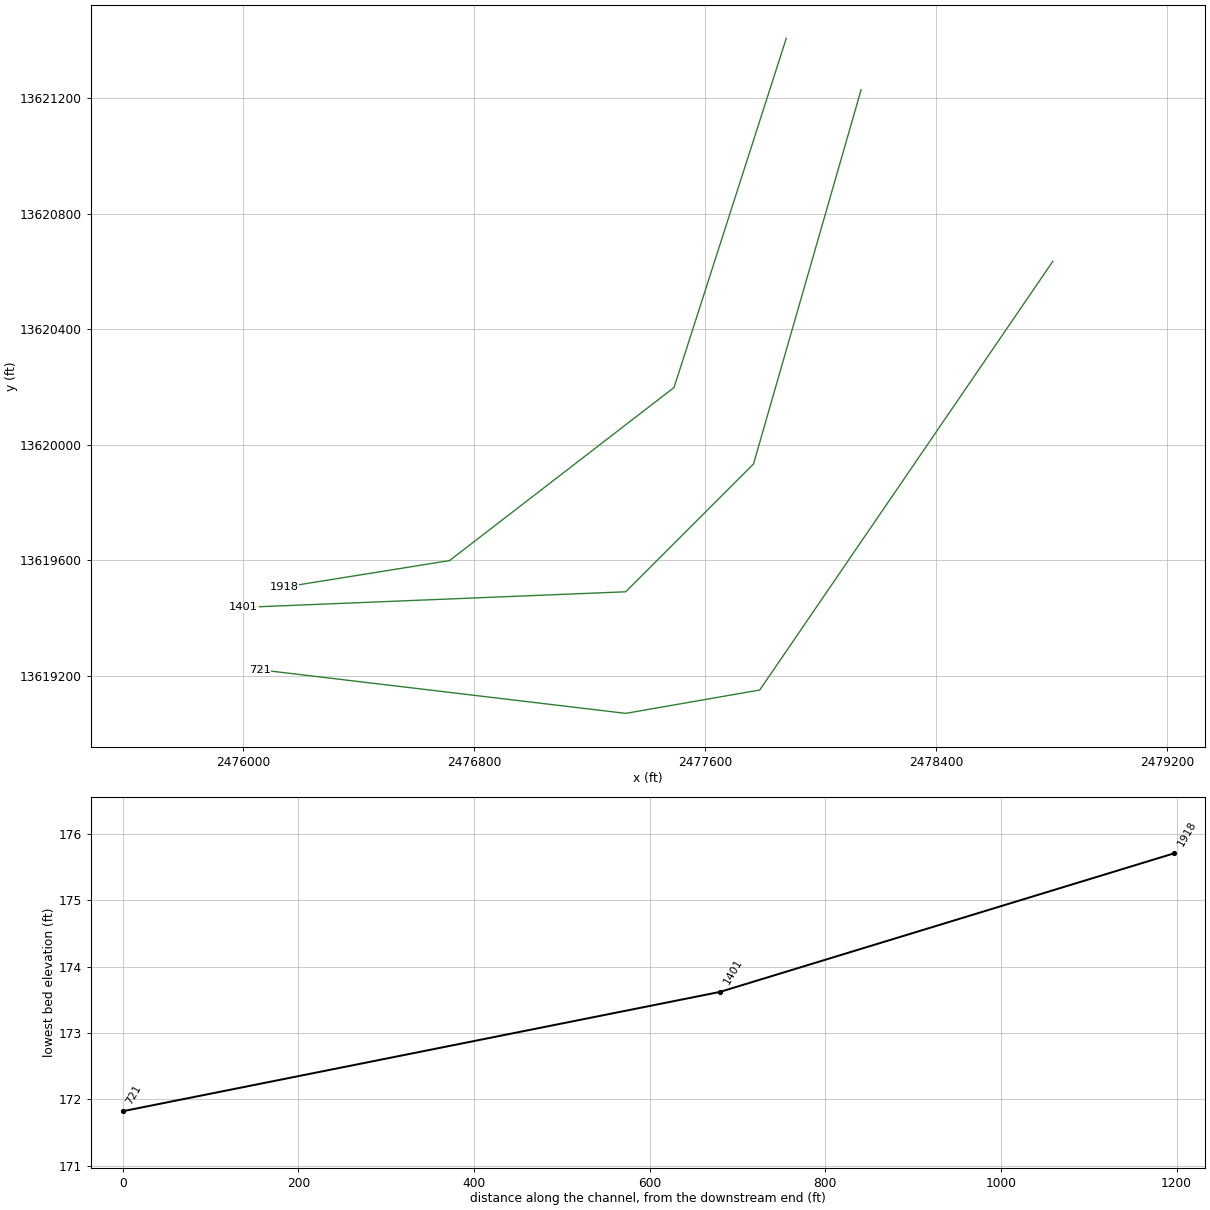
HEC-RAS study BOGGIE CREEK.prj: BOGGIE CREEK Base Level Engineering

--- BOGGIE CREEK.g01 (geometry) --- (continued)

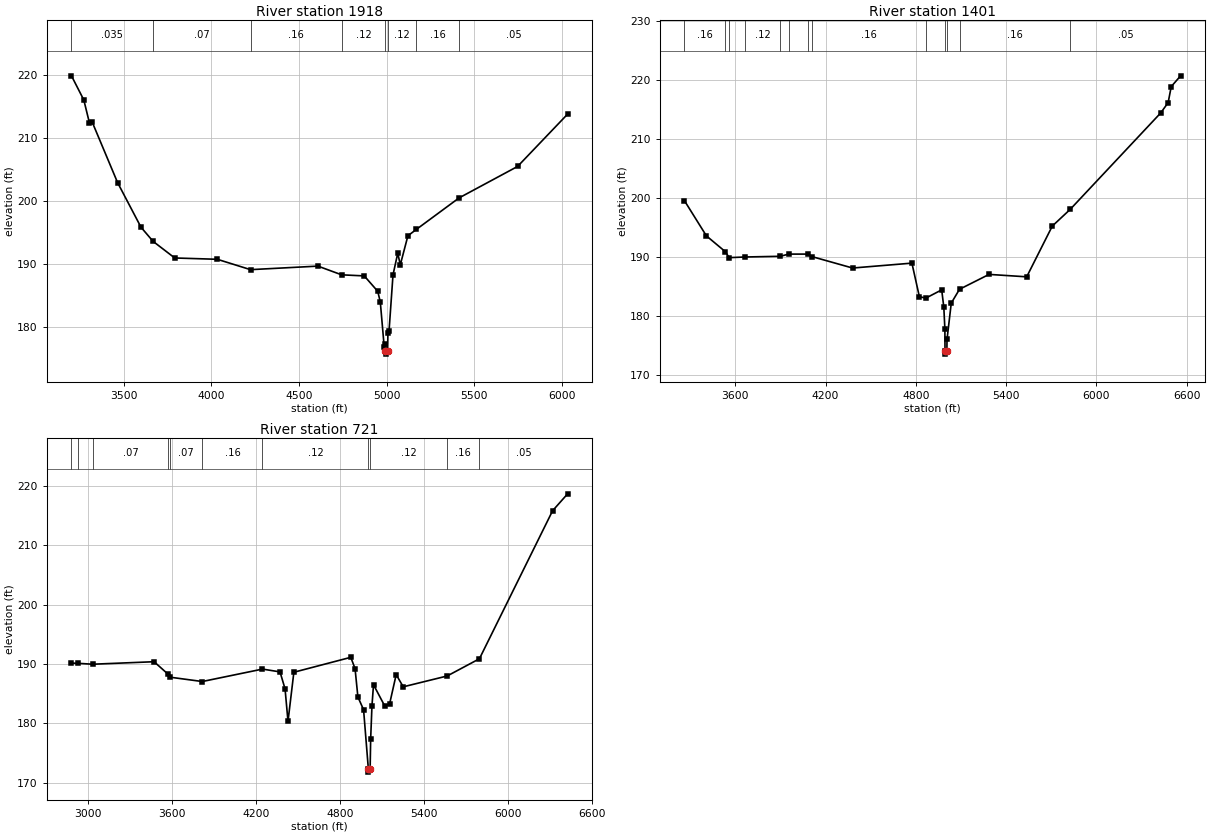
Type RM Length L Ch R = 1,1918,517,517,517
BEGIN DESCRIPTION:
X18316
END DESCRIPTION:
XS GIS Cut Line= 4
      2477881.54     13621407.25      2477492.84     13620197.99
      2476715.46     13619598.76      2476143.20     13619506.98
#Sta/Elev= 30
  3201.5  219.79  3272.0  215.96  3304.1  212.32  3319.4  212.49  3464.6  202.88
  3598.2  195.81  3667.2  193.57  3790.8  190.94  4033.7  190.73  4223.3  189.09
  4607.9  189.65  4743.3  188.27  4872.3  188.10  4949.2  185.66  4963.8  183.97
  4986.4  176.76  4992.8  177.29  4993.1  176.21  4993.6  175.71  5005.5  176.21
  5007.3  179.01  5013.6  179.34  5036.3  188.26  5063.4  191.70  5077.9  189.85
  5121.4  194.46  5169.9  195.47  5413.1  200.45  5747.4  205.44  6032.8  213.73
#Mann=8,-1,0
  3201.5   0.035       0  3667.2    0.07       0  4223.3    0.16       0
  4743.3    0.12       0  4993.1    0.07       0  5005.5    0.12       0
  5169.9    0.16       0  5413.1    0.05       0
Bank Sta=4993.1,5005.5
Exp/Cntr=0.3,0.1

Type RM Length L Ch R = 1,1401,680,680,680
BEGIN DESCRIPTION:
X18317
END DESCRIPTION:
XS GIS Cut Line= 4
      2478140.65     13621229.07      2477768.17     13619933.46
      2477325.49     13619490.79      2476002.82     13619436.80
#Sta/Elev= 30
  3262.4  199.62  3408.3  193.66  3534.6  190.97  3559.4  189.97  3665.5  190.08
  3898.9  190.20  3955.9  190.57  4081.9  190.57  4113.5  190.12  4380.0  188.21
  4774.3  189.04  4823.8  183.36  4866.7  183.11  4972.3  184.51  4986.4  181.56
  4993.5  177.86  4994.3  174.12  4994.8  173.62  5006.7  174.12  5007.6  176.10
  5035.9  182.27  5090.7  184.61  5287.1  187.13  5537.3  186.72  5707.4  195.32
  5826.0  198.14  6428.0  214.49  6477.4  216.24  6498.1  218.96  6560.3  220.78
#Mann=13,-1,0
  3262.4    0.16       0  3534.6   0.035       0  3559.4    0.07       0
  3665.5    0.12       0  3898.9    0.07       0  3955.9    0.12       0
  4081.9    0.07       0  4113.5    0.16       0  4866.7    0.12       0
  4994.3    0.07       0  5006.7    0.12       0  5090.7    0.16       0
  5826.0    0.05       0
Bank Sta=4994.3,5006.7
Exp/Cntr=0.3,0.1

Type RM Length L Ch R = 1,721,0,0,0
BEGIN DESCRIPTION:
X18318
END DESCRIPTION:
XS GIS Cut Line= 4
      2478804.66     13620635.24      2477789.76     13619150.68
      2477325.49     13619069.70      2476058.45     13619220.67
#Sta/Elev= 30
  2882.3  190.16  2929.4  190.12  3034.1  189.97  3472.7  190.39  3573.7  188.27
  3586.0  187.79  3817.1  187.06  4247.2  189.15  4372.6  188.68  4408.6  185.82
  4429.6  180.35  4471.5  188.62  4878.3  191.13  4908.8  189.23  4929.1  184.46
  4969.7  182.32  5004.0  172.32  5004.5  171.82  5016.5  172.32  5020.4  177.44
  5029.6  182.95  5040.7  186.52  5121.9  182.90  5155.9  183.32  5202.7  188.22
  5253.1  186.17  5567.0  187.99  5797.6  190.89  6320.6  215.79  6427.9  218.63
#Mann=11,-1,0
  2882.3    0.07       0  2929.4    0.12       0  3034.1    0.07       0
  3573.7    0.16       0  3586.0    0.07       0  3817.1    0.16       0
  4247.2    0.12       0  5004.0    0.07       0  5016.5    0.12       0
  5567.0    0.16       0  5797.6    0.05       0
Bank Sta=5004,5016.5
Exp/Cntr=0.3,0.1

Chan Stop Cuts=-1