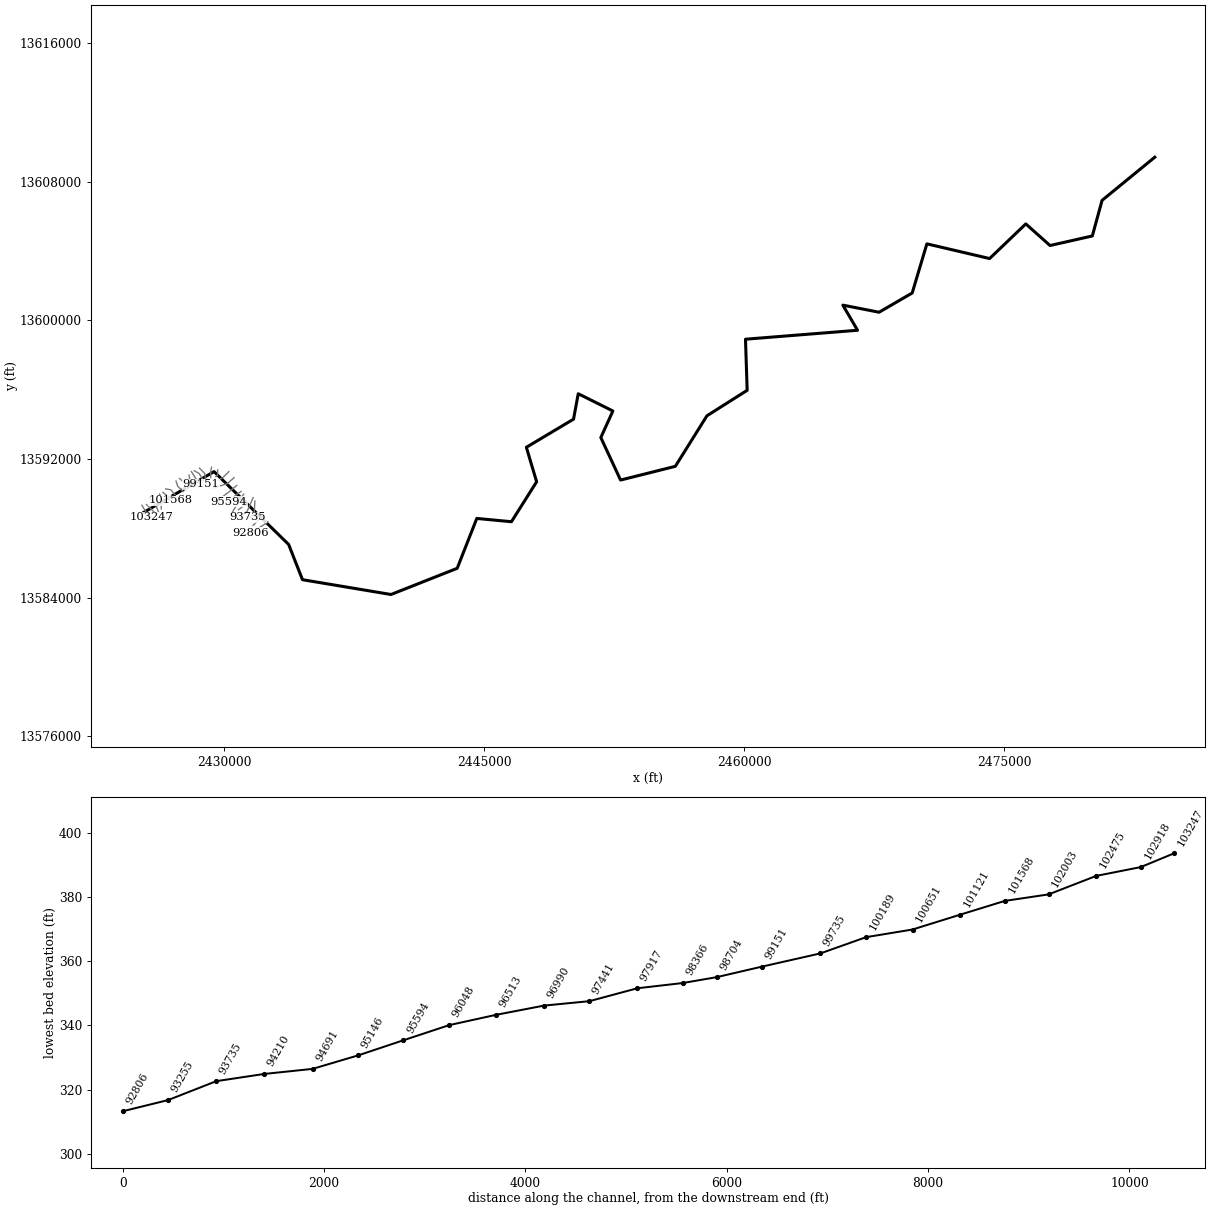
--- CLEAR CREEK.prj (project) ---

Proj Title=CLEAR CREEK Base Level Engineering
Current Plan=p01
Default Exp/Contr=0.3,0.1
English Units
Geom File=g01
Flow File=f01
Plan File=p01
Y Axis Title=Elevation
X Axis Title(PF)=Main Channel Distance
X Axis Title(XS)=Station
BEGIN DESCRIPTION:
CLEAR CREEK
END DESCRIPTION:
DSS Export Rating Curves= 0
DSS Export Rating Curve Sorted= 0
DSS Export Volume Flow Curves= 0
DXF OffsetX= 0
DXF OffsetY= 0
DXF ScaleX= 1
DXF ScaleY= 10

--- CLEAR CREEK.p01 (plan) ---

Plan Title=Multiple Run
Program Version=4.10
Short Identifier=Multiple
Geom File=g01
Flow File=f01
Subcritical Flow
K Sum by GR= 0
Std Step Tol= 0.01
Critical Tol= 0.01
Num of Std Step Trials= 20
Max Error Tol= 0.3
Flow Tol Ratio= 0.001
Split Flow NTrial= 30
Split Flow Tol= 0.02
Split Flow Ratio= 0.02
Log Output Level= 0
Friction Slope Method= 1
Unsteady Friction Slope Method= 2
Unsteady Bridges Friction Slope Method= 1
Parabolic Critical Depth
Global Vel Dist= 1 , 1 , 1
Global Log Level= 0
CheckData=True
Encroach Param=-1 ,0,0, 0
BEGIN DESCRIPTION:
Multiple Run
END DESCRIPTION:
Computation Interval=1HOUR
Output Interval=1HOUR
Run HTab= 0
Run UNet= 0
Run PostProcess= 0
Run WQNet= 0
UNET Theta= 1
UNET Theta Warmup= 1
UNET ZTol= 0.02
UNET ZSATol= 0.05
UNET MxIter= 20
UNET MaxInSteps= 0
UNET DtIC= 0
UNET DtMin= 0
UNET MaxCRTS= 20
UNET WFStab= 2
UNET SFStab= 1
UNET WFX= 1
UNET SFX= 1
UNET DSS MLevel= 4
UNET DZMax Abort= 100
UNET Convert EG Bridges= 0
UNET Use Existing IB Tables=-1
UNET Froude Reduction=False
UNET Froude Limit= 1
UNET Froude Power= 10
UNET Time Slicing=0,0, 5
UNET Junction Losses=0
Instantaneous Interval=1HOUR
Write IC File= 0
Write IC File at Sim End=0
Echo Input=False
Echo Parameters=False
Echo Output=False
Write Detailed= 0
WQ AD Non Conservative
WQ ULTIMATE=-1
WQ Max Comp Step=1HOUR
WQ Output Interval=15MIN
WQ Output Selected Increments= 0
WQ Output face flow=0
WQ Output face velocity=0
WQ Output face area=0
WQ Output face dispersion=0
WQ Output cell volume=0
WQ Output cell surface area=0
WQ Output cell continuity=0
WQ Output cumulative cell continuity=0
WQ Output face conc=0
WQ Output face dconc_dx=0
WQ Output face courant=0
WQ Output face peclet=0
WQ Output face adv mass=0
WQ Output face disp mass=0
WQ Output cell mass=0
WQ Output cell source sink temp=0
WQ Output cell source sink nsm=0
WQ Output MaxMinRange=-1
WQ Daily Max Min Mean=-1
WQ Daily Range=0
WQ Daily Time=0
WQ Create Restart=0
WQ Fixed Restart=0
WQ System Summary=0
WQ Use Fixed Temperature=0
Sorting and Armoring Iterations= 10
XS Update Threshold= 0.02
Hydraulics Update Threshold= 0.02
Energy Slope Method= 1
Volume Change Method= 0
XS Weighting Method= 0
Number of US Weighted Cross Sections= 1
Number of DS Weighted Cross Sections= 1
Upstream XS Weight=0.25
Main XS Weight=0.5
Downstream XS Weight=0.25
Number of DS XS's Weighted with US Boundary= 1
Upstream Boundary Weight= 1
Weight of XSs Associated with US Boundary= 0
Number of US XS's Weighted with DS Boundary= 1
Downstream Boundary Weight= 0.5
Weight of XSs Associated with DS Boundary= 0.5
Sediment Output Level= 4
Mass or Volume Output= 0
Output Increment Type= 1
Profile and TS Output Increment= 10
XS Output Flag= 0
XS Output Increment= 10
Disregard all LS=0
Disregard all Conn=0
Disregard all Breaches=0
Disregard all Pumps=0

--- CLEAR CREEK.f01 (steady flow) ---

Flow Title=Multiple
Program Version=4.10
Number of Profiles= 7
Profile Names=10-year,25-year,50-year,1pct_min,100-year,1pct_plu,500-year
River Rch & RM=CLEAR CREEK,Reach-1         ,103247
     549     645     854     549    1096    2187    1786
River Rch & RM=CLEAR CREEK,Reach-1         ,100651
     643    1041    1402     914    1824    3639    3059
River Rch & RM=CLEAR CREEK,Reach-1         ,96513
     914    1510    2060    1360    2714    5415    4667
River Rch & RM=CLEAR CREEK,Reach-1         ,91415
    2400    4131    5791    3915    7810   15584   14094
River Rch & RM=CLEAR CREEK,Reach-1         ,82017
    3365    5874    8315    5670   11312   22571   20773
River Rch & RM=CLEAR CREEK,Reach-1         ,79853
    4126    7208   10208    6958   13882   27698   25467
River Rch & RM=CLEAR CREEK,Reach-1         ,77633
    4340    7580   10733    7312   14589   29108   26737
River Rch & RM=CLEAR CREEK,Reach-1         ,71569
    4490    7857   11139    7598   15160   30249   27856
River Rch & RM=CLEAR CREEK,Reach-1         ,69935
    4484    7824   11071    7535   15035   29999   27506
River Rch & RM=CLEAR CREEK,Reach-1         ,63742
    5710    9694   13462    8974   17905   35726   31387
River Rch & RM=CLEAR CREEK,Reach-1         ,59083
    5988   10201   14201    9489   18933   37777   33350
River Rch & RM=CLEAR CREEK,Reach-1         ,52450
    6549   11185   15599   10442   20834   41569   36821
River Rch & RM=CLEAR CREEK,Reach-1         ,43678
    6570   11218   15643   10469   20889   41678   36904
River Rch & RM=CLEAR CREEK,Reach-1         ,42259
    7121   12196   17044   11431   22808   45508   40464
River Rch & RM=CLEAR CREEK,Reach-1         ,40855
    7206   12340   17242   11562   23069   46030   40912
River Rch & RM=CLEAR CREEK,Reach-1         ,34446
    7741   13272   18561   12457   24855   49591   44144
River Rch & RM=CLEAR CREEK,Reach-1         ,26730
    7882   13525   18925   12708   25356   50591   45083
River Rch & RM=CLEAR CREEK,Reach-1         ,24654
    8374   14393   20166   13557   27049   53970   48202
River Rch & RM=CLEAR CREEK,Reach-1         ,21927
    8566   14741   20669   13906   27747   55362   49525
River Rch & RM=CLEAR CREEK,Reach-1         ,16397
    8521   14642   20511   13786   27507   54884   48998
River Rch & RM=CLEAR CREEK,Reach-1         ,12049
    8523   14635   20489   13764   27462   54794   48860
River Rch & RM=CLEAR CREEK,Reach-1         ,8515
    9258   16008   22521   15204   30337   60529   54514
Boundary for River Rch & Prof#=CLEAR CREEK,Reach-1         , 1
Up Type= 0
Dn Type= 3
Dn Slope=0.001
Boundary for River Rch & Prof#=CLEAR CREEK,Reach-1         , 2
Up Type= 0
Dn Type= 3
Dn Slope=0.001
Boundary for River Rch & Prof#=CLEAR CREEK,Reach-1         , 3
Up Type= 0
Dn Type= 3
Dn Slope=0.001
Boundary for River Rch & Prof#=CLEAR CREEK,Reach-1         , 4
Up Type= 0
Dn Type= 3
Dn Slope=0.001
Boundary for River Rch & Prof#=CLEAR CREEK,Reach-1         , 5
Up Type= 0
Dn Type= 3
Dn Slope=0.001
Boundary for River Rch & Prof#=CLEAR CREEK,Reach-1         , 6
Up Type= 0
Dn Type= 3
Dn Slope=0.001
Boundary for River Rch & Prof#=CLEAR CREEK,Reach-1         , 7
Up Type= 0
Dn Type= 3
Dn Slope=0.001
DSS Import GetInterval= 0
DSS Import GetPeak= 0
DSS Import FillOption= 0

--- CLEAR CREEK.g01 (geometry) ---

Geom Title=Existing Conditions
Program Version=4.10

River Reach=CLEAR CREEK     ,Reach-1
Reach XY= 30
        2425375.       13588925.      2429419.15     13591272.94
      2433719.75     13587069.56      2434518.83     13585032.86
       2439623.5     13584178.61      2443442.14     13585691.27
      2444572.55     13588569.53      2446569.71     13588380.48
      2448023.81      13590685.5      2447430.45     13592677.47
       2450152.3     13594301.53      2450422.66     13595769.28
      2452421.48     13594773.54      2451725.52     13593240.22
       2452865.3     13590785.76      2456023.28     13591578.34
       2457844.7     13594495.13      2460165.99     13595967.98
      2460068.79      13598917.2      2466531.95     13599434.19
      2465685.43     13600884.79        2467775.       13600475.
      2469684.71      13601585.7      2470530.93     13604422.77
        2474150.     13603574.58       2476235.5     13605573.81
      2477635.48     13604325.93      2480073.45     13604878.75
      2480635.76     13606934.68        2483675.       13609425.

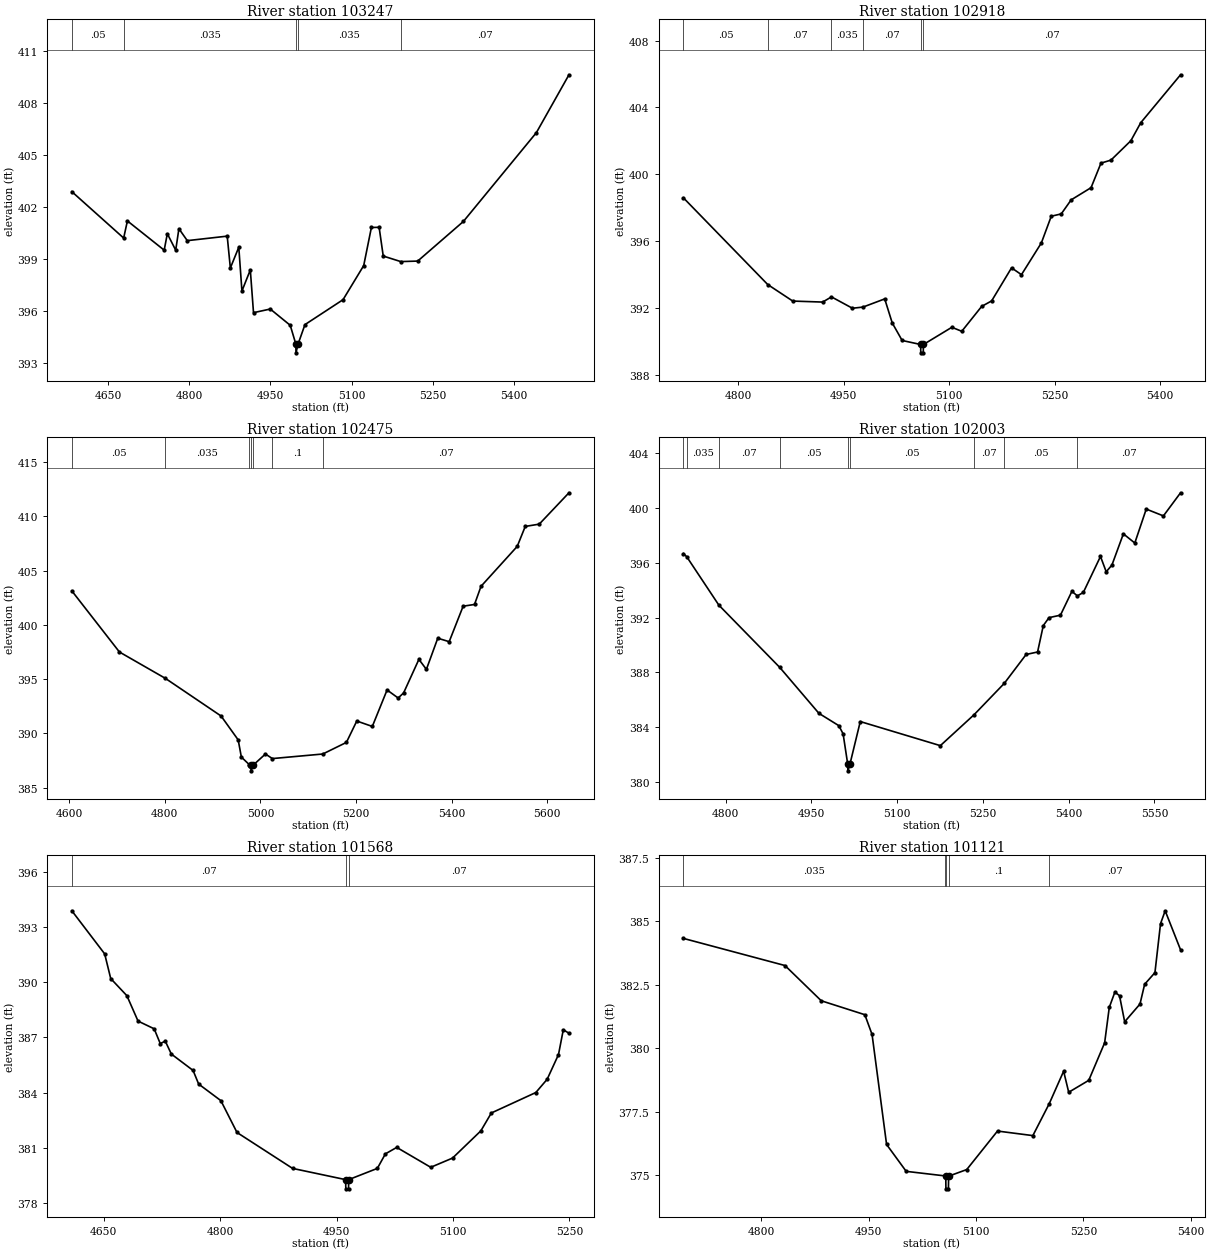
Type RM Length L Ch R = 1 ,103247  ,329,329,329
BEGIN DESCRIPTION:
X18475
END DESCRIPTION:
XS GIS Cut Line= 3
       2425259.1     13589331.44      2425516.45     13588903.97
      2425834.37      13588629.6
#Sta/Elev= 30
  4582.8  402.87  4678.6  400.19  4685.5  401.18  4753.5  399.49  4759.3  400.44
  4774.8  399.49  4780.7  400.73  4796.2  400.04    4870   400.3  4875.8  398.46
  4891.4  399.66  4897.2  397.13  4912.7  398.35  4918.6  395.88  4949.6  396.09
  4986.5  395.15  4996.9  394.06  4997.1  393.56  5000.9  394.06  5013.7  395.19
  5084.1  396.63  5122.3   398.6  5136.5   400.8  5150.8  400.81  5158.4  399.15
  5190.8  398.83  5222.1  398.86  5306.6  401.15  5441.5  406.28  5501.7  409.62
#Mann= 5 ,-1 , 0
  4582.8     .05       0  4678.6    .035       0  4996.9    .035       0
  5000.9    .035       0  5190.8     .07       0
Bank Sta=4996.9,5000.9
XS Rating Curve= 0 ,0
Exp/Cntr=0.3,0.1

Type RM Length L Ch R = 1 ,102918  ,443,443,443
BEGIN DESCRIPTION:
CLEAR CREEK 133.0
END DESCRIPTION:
XS GIS Cut Line= 3
      2425525.02     13589374.98        2425725.       13589175.
      2426025.02     13588874.98
#Sta/Elev= 30
    4722  398.58  4841.9  393.39  4877.5   392.4    4920  392.34  4932.6  392.65
  4962.4  391.97  4977.4  392.04  5008.3  392.53    5019  391.09  5033.1  390.04
  5059.4   389.8  5059.6   389.3  5063.1   389.3  5063.4   389.8  5103.8  390.83
  5117.9  390.59  5146.2  392.08  5160.4  392.41  5188.7  394.39  5202.8  393.98
  5231.1  395.88  5245.2  397.48  5259.4  397.62  5273.5  398.46  5301.8  399.19
  5315.9  400.66  5330.1  400.84  5358.4     402  5372.5  403.08  5429.1  405.95
#Mann= 6 ,-1 , 0
    4722     .05       0  4841.9     .07       0  4932.6    .035       0
  4977.4     .07       0  5059.4     .05       0  5063.4     .07       0
Bank Sta=5059.4,5063.4
XS Rating Curve= 0 ,0
Exp/Cntr=0.3,0.1

Type RM Length L Ch R = 1 ,102475  ,472,472,472
BEGIN DESCRIPTION:
CLEAR CREEK 132.0
END DESCRIPTION:
XS GIS Cut Line= 3
      2425674.97     13589775.02        2425975.       13589525.
      2426224.98     13588925.04
#Sta/Elev= 30
  4605.3  403.13  4704.9   397.5  4801.1  395.07  4917.7   391.6  4953.5   389.4
  4960.1  387.82  4976.5  387.13  4980.2  387.05  4980.4  386.55  4984.2  387.05
  5010.5   388.1    5025  387.68  5130.5   388.1    5180  389.17  5201.7  391.14
  5234.2  390.64  5265.1     394  5288.3  393.26  5299.7  393.73  5331.7  396.82
  5347.4   395.9  5371.2  398.77  5395.1  398.45  5424.3  401.72  5448.1  401.88
  5461.7  403.55  5537.5  407.23  5554.3  409.07  5583.6  409.28  5645.8  412.17
#Mann= 7 ,-1 , 0
  4605.3     .05       0  4801.1    .035       0  4976.5     .07       0
  4980.2     .05       0  4984.2     .07       0    5025      .1       0
  5130.5     .07       0
Bank Sta=4980.2,4984.2
XS Rating Curve= 0 ,0
Exp/Cntr=0.3,0.1

Type RM Length L Ch R = 1 ,102003  ,435,435,435
BEGIN DESCRIPTION:
CLEAR CREEK 131.0
END DESCRIPTION:
XS GIS Cut Line= 3
      2426275.01     13589974.99        2426375.       13589725.
        2426375.     13589125.04
#Sta/Elev= 30
  4726.4  396.67  4732.3  396.43  4788.4   392.9  4894.7  388.36  4963.3     385
  4998.1   384.1  5005.6   383.5  5013.6   381.3  5013.9   380.8  5017.6   381.3
  5035.6   384.4  5175.6  382.64  5234.6   384.9  5287.4  387.19  5325.6   389.3
  5345.6  389.48  5355.6  391.41  5365.6  391.99  5385.6  392.17  5405.6  393.91
  5415.2  393.58  5425.6  393.83  5455.6  396.46  5465.6  395.34  5475.6  395.83
  5495.6  398.11  5515.6  397.44  5535.6  399.92  5565.6  399.42  5595.6  401.11
#Mann= 9 ,-1 , 0
  4726.4     .05       0  4732.3    .035       0  4788.4     .07       0
  4894.7     .05       0  5013.6     .05       0  5017.6     .05       0
  5234.6     .07       0  5287.4     .05       0  5415.2     .07       0
Bank Sta=5013.6,5017.6
XS Rating Curve= 0 ,0
Exp/Cntr=0.3,0.1

Type RM Length L Ch R = 1 ,101568  ,447,447,447
BEGIN DESCRIPTION:
CLEAR CREEK 130.0
END DESCRIPTION:
XS GIS Cut Line= 3
      2426475.01     13590074.99        2426775.       13589825.
        2426925.       13589625.
#Sta/Elev= 30
    4609  393.87  4651.3  391.53  4659.1  390.19  4679.9  389.26  4694.3  387.88
  4715.1  387.46  4722.9  386.66  4729.4  386.79  4737.2  386.09  4765.2   385.2
  4772.4  384.46    4801  383.56  4821.8  381.83  4893.4  379.88  4961.7  379.27
    4962  378.77  4965.5  378.77  4965.7  379.27  5002.6  379.88    5013  380.67
  5027.6  381.02  5071.4  379.94  5099.5  380.44    5136  381.92  5149.5  382.89
  5206.8     384  5221.4  384.72    5236  386.06  5242.2  387.41  5249.5  387.22
#Mann= 3 ,-1 , 0
    4609     .07       0  4961.7     .05       0  4965.7     .07       0
Bank Sta=4961.7,4965.7
XS Rating Curve= 0 ,0
Exp/Cntr=0.3,0.1

Type RM Length L Ch R = 1 ,101121  ,470,470,470
BEGIN DESCRIPTION:
CLEAR CREEK 129.0
END DESCRIPTION:
XS GIS Cut Line= 3
        2426625.       13590275.        2426925.       13590225.
      2427175.03     13589924.97
#Sta/Elev= 30
    4691  384.33  4832.9  383.26  4883.6  381.87  4944.5  381.32  4954.6  380.54
  4974.9   376.2  5002.3  375.14  5056.6  374.96  5057.6  374.95  5057.8  374.45
  5061.3  374.45  5061.6  374.95  5086.9  375.21  5129.9  376.73  5179.3  376.55
  5202.2  377.81  5222.3  379.09  5229.4  378.26  5257.4  378.73  5279.6  380.21
  5286.1  381.61  5293.9  382.21  5300.4  382.07  5307.6  381.04    5329  381.74
  5335.5  382.52  5349.9  382.98  5357.7  384.91  5364.2  385.42  5385.7  383.88
#Mann= 5 ,-1 , 0
    4691    .035       0  5056.6      .1       0  5057.6    .035       0
  5061.6      .1       0  5202.2     .07       0
Bank Sta=5057.6,5061.6
XS Rating Curve= 0 ,0
Exp/Cntr=0.3,0.1

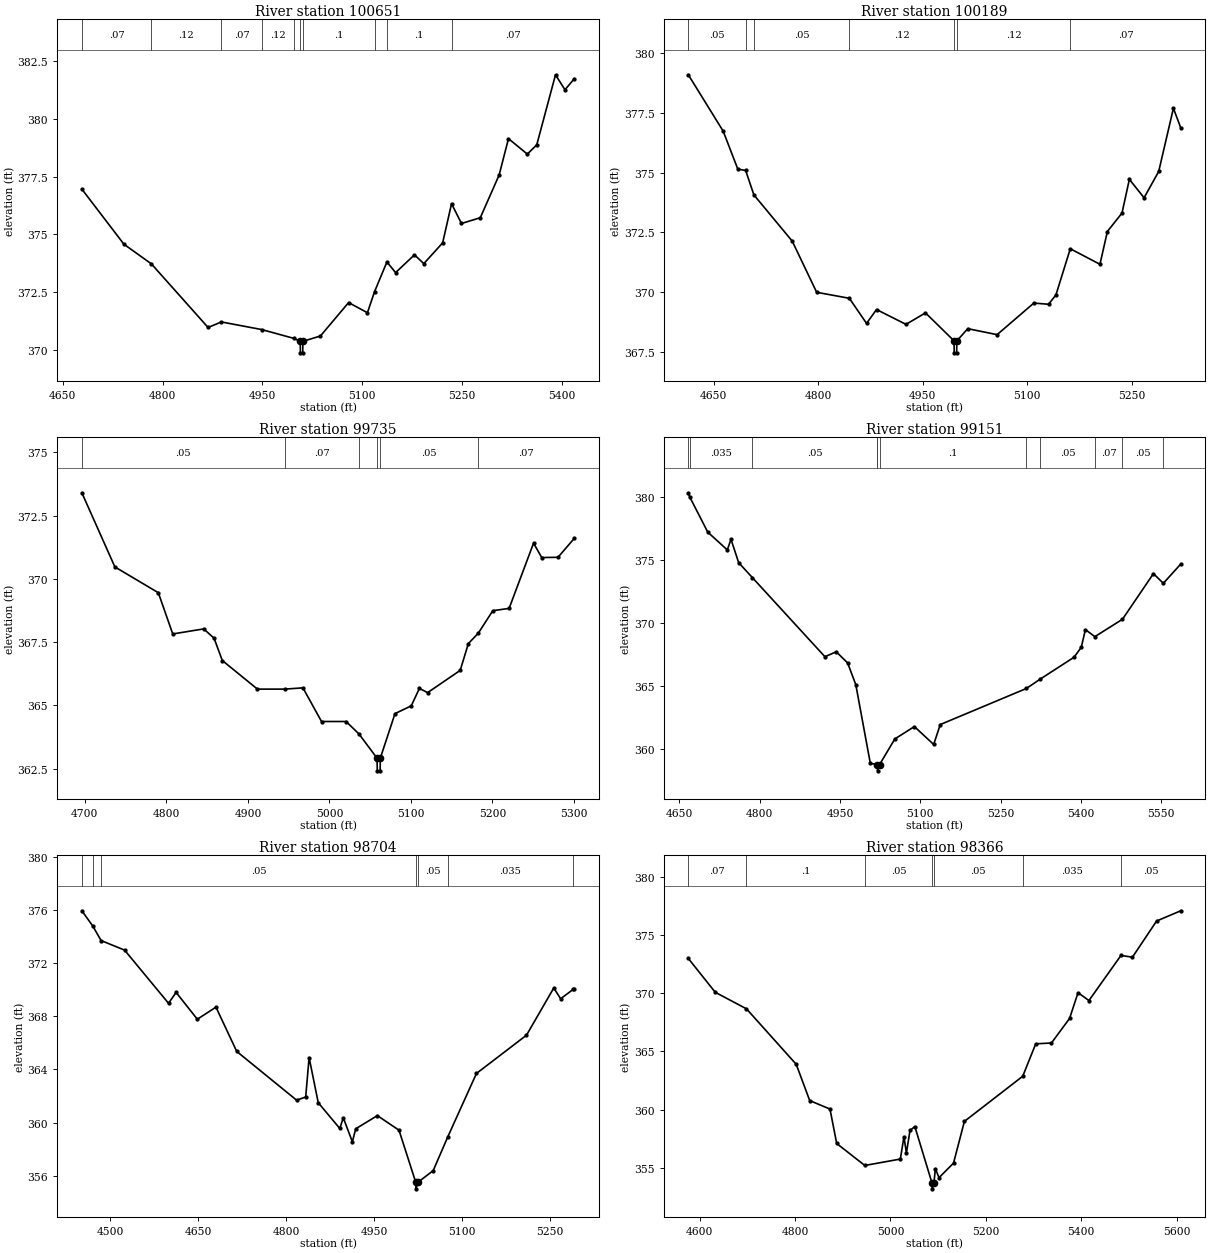
Type RM Length L Ch R = 1 ,100651  ,462,462,462
BEGIN DESCRIPTION:
CLEAR CREEK 128.0
END DESCRIPTION:
XS GIS Cut Line= 3
      2427224.99     13590725.03        2427325.       13590425.
      2427624.99     13590125.01
#Sta/Elev= 30
  4678.7  376.96    4742  374.57  4783.2  373.72  4868.5  370.96  4888.5   371.2
  4949.1  370.87  4997.1  370.49  5007.1  370.36  5007.3  369.86  5010.8  369.86
  5011.1  370.36  5037.4  370.59  5079.8  372.04  5108.1   371.6  5118.9  372.52
  5137.4   373.8  5150.5  373.34  5178.8  374.11  5192.9  373.73  5221.2  374.63
  5234.6  376.33  5249.5  375.47  5277.8  375.72  5306.1  377.57  5320.2  379.15
  5348.5  378.48  5362.7  378.88  5390.9  381.92  5405.1  381.27  5419.2  381.75
#Mann= 10 ,-1 , 0
  4678.7     .07       0  4783.2     .12       0  4888.5     .07       0
  4949.1     .12       0  4997.1      .1       0  5007.1     .05       0
  5011.1      .1       0  5118.9     .07       0  5137.4      .1       0
  5234.6     .07       0
Bank Sta=5007.1,5011.1
XS Rating Curve= 0 ,0
Exp/Cntr=0.3,0.1

Type RM Length L Ch R = 1 ,100189  ,454,454,454
BEGIN DESCRIPTION:
CLEAR CREEK 127.0
END DESCRIPTION:
XS GIS Cut Line= 3
      2427424.98     13590875.01        2427725.       13590625.
      2427825.01     13590324.97
#Sta/Elev= 30
  4613.5  379.09  4663.6  376.73  4684.5  375.15  4695.8  375.09  4707.6  374.07
  4762.6  372.14  4797.7     370  4844.6  369.75  4869.3   368.7  4883.6  369.28
  4925.9  368.66  4953.9  369.14  4994.9  367.97  4995.1  367.47  4998.6  367.47
  4998.9  367.97  5014.6  368.48  5056.7  368.23  5109.4  369.55  5130.5   369.5
  5141.1  369.89  5161.7  371.82  5204.3  371.17  5214.9  372.54  5235.9  373.31
  5246.5  374.72  5267.6  373.95  5288.6  375.05  5309.7  377.69  5320.3  376.87
#Mann= 7 ,-1 , 0
  4613.5     .05       0  4695.8     .07       0  4707.6     .05       0
  4844.6     .12       0  4994.9     .05       0  4998.9     .12       0
  5161.7     .07       0
Bank Sta=4994.9,4998.9
XS Rating Curve= 0 ,0
Exp/Cntr=0.3,0.1

Type RM Length L Ch R = 1 ,99735   ,584,584,584
BEGIN DESCRIPTION:
CLEAR CREEK 126.0
END DESCRIPTION:
XS GIS Cut Line= 3
        2427975.     13591074.98        2428025.       13590775.
        2428025.     13590475.01
#Sta/Elev= 30
  4696.3   373.4  4736.8  370.47  4790.1  369.45  4807.8  367.82  4845.8  368.02
  4858.5  367.65  4868.6  366.77  4911.7  365.64  4945.1  365.64  4967.5  365.69
  4990.3  364.36  5020.4  364.36  5036.2  363.87  5058.4  362.91  5058.7  362.41
  5062.2  362.41  5062.4  362.91  5080.4  364.67  5100.4  364.98  5110.4  365.67
  5120.4   365.5  5160.4  366.38  5170.4  367.44  5182.6  367.85  5200.4  368.74
  5220.4  368.83  5250.4  371.41  5260.4  370.84  5280.4  370.85  5300.4   371.6
#Mann= 6 ,-1 , 0
  4696.3     .05       0  4945.1     .07       0  5036.2     .05       0
  5058.4     .05       0  5062.4     .05       0  5182.6     .07       0
Bank Sta=5058.4,5062.4
XS Rating Curve= 0 ,0
Exp/Cntr=0.3,0.1

Type RM Length L Ch R = 1 ,99151   ,447,447,447
BEGIN DESCRIPTION:
CLEAR CREEK 125.0
END DESCRIPTION:
XS GIS Cut Line= 3
      2428111.64     13591272.38      2428373.36       13590858.
      2428656.86     13590535.24
#Sta/Elev= 30
  4666.7  380.32  4669.2     380    4703   377.2  4739.5  375.79  4746.4  376.63
  4760.7  374.78  4786.2   373.6  4921.8  367.32    4943  367.71  4964.2  366.83
  4979.5   365.1  5006.6  358.86  5019.7  358.77  5019.9  358.77  5020.1  358.27
  5023.9  358.77  5052.4   360.8  5088.9  361.78  5124.9  360.36  5137.2  361.94
    5298   364.8  5323.4  365.53  5387.1  367.28  5400.6  368.07  5408.2  369.47
  5425.9  368.91  5477.5  370.29  5535.3  373.91  5553.8  373.14  5586.4  374.67
#Mann= 11 ,-1 , 0
  4666.7     .05       0  4669.2    .035       0  4786.2     .05       0
  5019.7      .1       0  5019.9     .05       0  5023.9      .1       0
    5298     .07       0  5323.4     .05       0  5425.9     .07       0
  5477.5     .05       0  5553.8    .035       0
Bank Sta=5019.9,5023.9
XS Rating Curve= 0 ,0
Exp/Cntr=0.3,0.1

Type RM Length L Ch R = 1 ,98704   ,338,338,338
BEGIN DESCRIPTION:
CLEAR CREEK 124.0
END DESCRIPTION:
XS GIS Cut Line= 3
      2428275.03     13591324.98      2428560.91     13591163.32
      2428825.03     13590724.96
#Sta/Elev= 30
  4451.2  375.93  4469.9  374.78    4484  373.69  4524.1  372.97  4599.1  368.97
    4612  369.79  4648.2  367.77    4680  368.68  4715.4  365.35  4817.6  361.68
  4833.1  361.92  4838.9  364.89  4854.5  361.49  4891.3  359.55  4897.2  360.36
  4912.7  358.55  4918.5  359.53  4955.4  360.52  4992.3  359.42  5020.8  355.51
  5021.1  355.01  5024.8  355.51  5050.6  356.38  5075.5  358.92  5124.4  363.69
  5209.8  366.57  5256.3  370.12  5268.1  369.31  5289.2  370.01  5291.4  370.01
#Mann= 7 ,-1 , 0
  4451.2     .05       0  4469.9    .035       0    4484     .05       0
  5020.8     .05       0  5024.8     .05       0  5075.5    .035       0
  5289.2     .05       0
Bank Sta=5020.8,5024.8
XS Rating Curve= 0 ,0
Exp/Cntr=0.3,0.1

Type RM Length L Ch R = 1 ,98366   ,449,449,449
BEGIN DESCRIPTION:
CLEAR CREEK 123.0
END DESCRIPTION:
XS GIS Cut Line= 3
      2428575.02     13591474.98        2428875.       13591175.
        2428975.     13590575.01
#Sta/Elev= 30
  4576.3  372.99  4632.8  370.08  4698.2  368.66  4802.5  363.89  4830.8  360.77
  4873.3  360.04  4887.4  357.08  4946.3  355.19  5020.8  355.74  5028.4  357.66
  5033.5  356.27  5041.1   358.2  5051.2  358.54  5087.2  353.68  5087.5  353.18
  5091.2  353.68  5094.3  354.91  5101.9  354.14  5132.3  355.39  5155.1  358.98
  5277.4  362.86  5304.7  365.65  5337.6  365.72  5375.6  367.83  5393.4  370.05
  5416.2  369.37  5483.4  373.25  5507.4   373.1  5558.1  376.21  5608.8  377.09
#Mann= 7 ,-1 , 0
  4576.3     .07       0  4698.2      .1       0  4946.3     .05       0
  5087.2     .05       0  5091.2     .05       0  5277.4    .035       0
  5483.4     .05       0
Bank Sta=5087.2,5091.2
XS Rating Curve= 0 ,0
Exp/Cntr=0.3,0.1

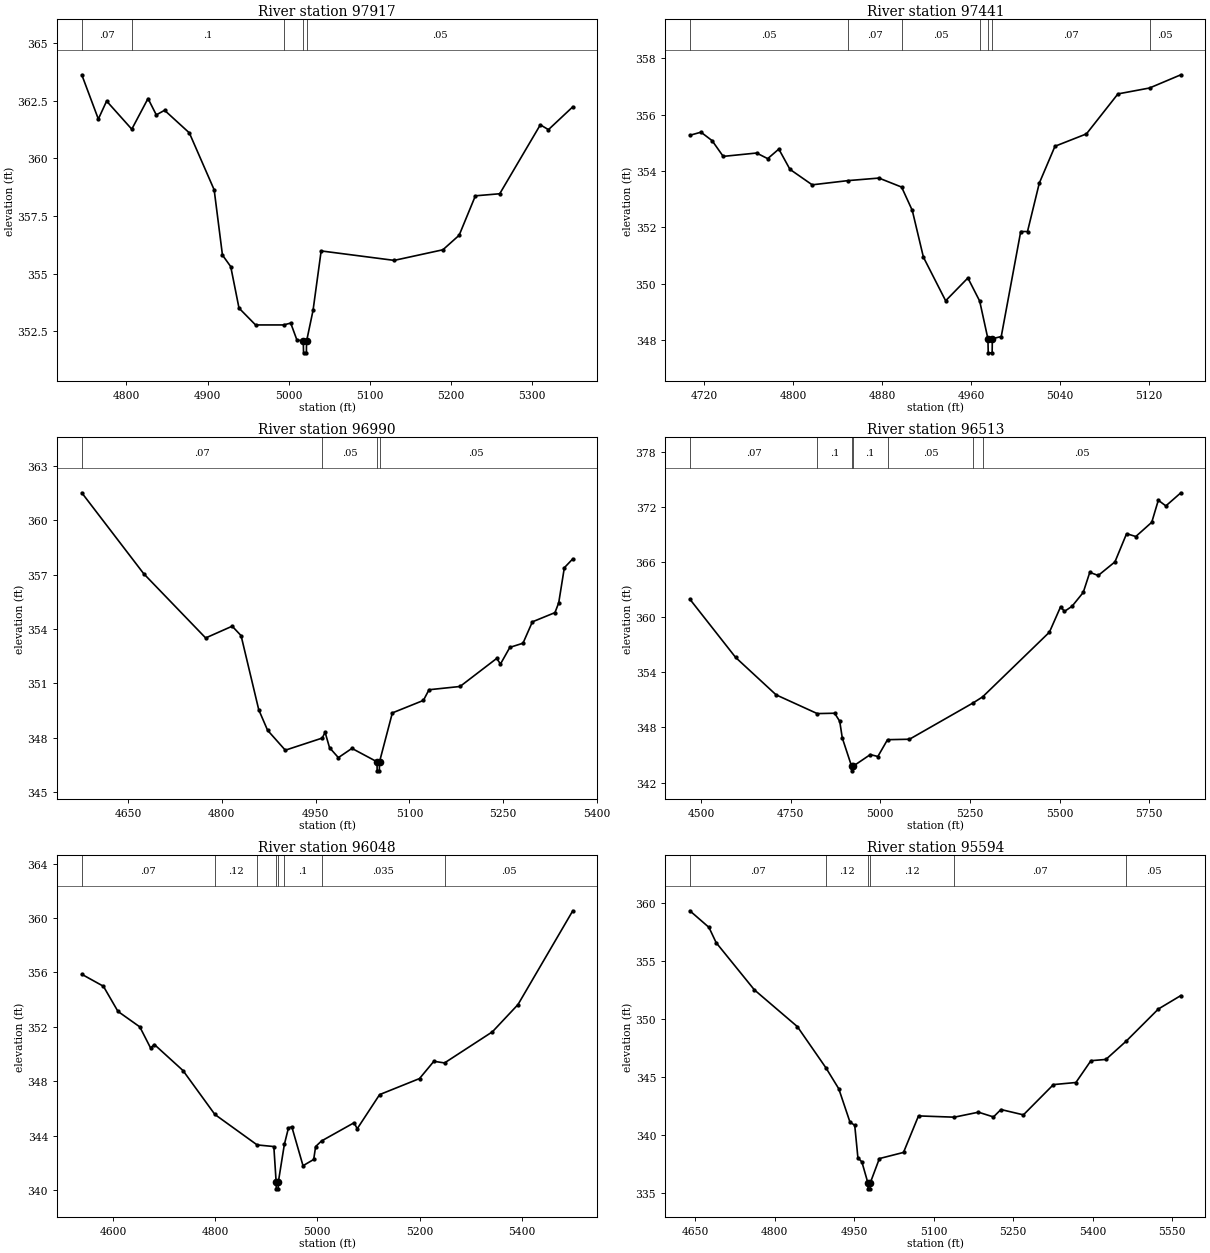
Type RM Length L Ch R = 1 ,97917   ,476,476,476
BEGIN DESCRIPTION:
CLEAR CREEK 122.0
END DESCRIPTION:
XS GIS Cut Line= 3
      2429274.99     13591524.97        2429225.       13591275.
        2429225.     13590925.03
#Sta/Elev= 30
    4745  363.62  4765.4   361.7  4775.6  362.48  4806.6  361.26  4826.6  362.59
  4836.8  361.88    4847  362.08  4877.5   361.1  4908.1  358.63  4918.3   355.8
  4928.5   355.3  4938.7   353.5  4959.1  352.77  4993.6  352.77  5002.4  352.85
  5009.9  352.13  5017.9  352.06  5018.2  351.56  5021.7  351.56  5021.9  352.06
  5029.9   353.4  5039.9  355.98  5129.9  355.57  5189.9  356.03  5209.9  356.66
  5229.9  358.37  5259.9  358.46  5309.9  361.45  5319.9  361.24  5349.9  362.23
#Mann= 5 ,-1 , 0
    4745     .07       0  4806.6      .1       0  4993.6     .05       0
  5017.9     .05       0  5021.9     .05       0
Bank Sta=5017.9,5021.9
XS Rating Curve= 0 ,0
Exp/Cntr=0.3,0.1

Type RM Length L Ch R = 1 ,97441   ,451,451,451
BEGIN DESCRIPTION:
CLEAR CREEK 121.0
END DESCRIPTION:
XS GIS Cut Line= 3
        2429625.     13591375.03        2429625.       13591075.
      2429524.97     13590974.97
#Sta/Elev= 30
  4707.3  355.27  4717.3  355.38  4727.3  355.08  4737.3  354.52  4767.3  354.64
  4777.3  354.44  4787.3  354.78  4797.3  354.06  4817.3  353.51  4849.6  353.66
  4877.3  353.75  4897.7  353.43  4907.3   352.6  4917.3  350.94  4937.3  349.39
  4957.3   350.2  4967.9  349.38  4975.3  348.04  4975.6  347.54  4979.1  347.54
  4979.3  348.04  4987.3  348.12  5004.8  351.85  5010.9  351.85  5021.5  353.57
  5035.6  354.88  5063.9  355.32  5092.2  356.74  5120.6  356.95  5148.8  357.42
#Mann= 7 ,-1 , 0
  4707.3     .05       0  4849.6     .07       0  4897.7     .05       0
  4967.9     .07       0  4975.3     .05       0  4979.3     .07       0
  5120.6     .05       0
Bank Sta=4975.3,4979.3
XS Rating Curve= 0 ,0
Exp/Cntr=0.3,0.1

Type RM Length L Ch R = 1 ,96990   ,477,477,477
BEGIN DESCRIPTION:
CLEAR CREEK 120.0
END DESCRIPTION:
XS GIS Cut Line= 3
      2430275.02     13591275.02        2429975.       13590975.
      2429675.03     13590775.02
#Sta/Elev= 30
  4576.3  361.52  4675.3  357.05  4774.3   353.5  4816.7  354.15  4830.9  353.63
  4859.2  349.53  4873.3   348.4  4901.6   347.3  4960.6  347.97  4965.2  348.29
  4972.3  347.44  4986.4  346.89  5008.1   347.4  5048.2  346.66  5048.4  346.16
  5051.9  346.16  5052.2  346.66  5072.7  349.36  5122.3  350.05  5131.3  350.64
  5180.9  350.82  5239.5  352.37  5245.5  352.06  5260.5  352.98  5281.5  353.21
  5296.5  354.39  5332.6   354.9  5338.6  355.44  5347.6  357.38  5361.1  357.87
#Mann= 4 ,-1 , 0
  4576.3     .07       0  4960.6     .05       0  5048.2     .05       0
  5052.2     .05       0
Bank Sta=5048.2,5052.2
XS Rating Curve= 0 ,0
Exp/Cntr=0.3,0.1

Type RM Length L Ch R = 1 ,96513   ,465,465,465
BEGIN DESCRIPTION:
CLEAR CREEK 119.0
END DESCRIPTION:
XS GIS Cut Line= 3
      2430575.02     13590925.01        2430175.       13590575.
      2429374.98     13590324.99
#Sta/Elev= 30
  4468.7  361.96  4596.4  355.62  4709.3  351.55  4824.1  349.51  4872.6  349.55
  4886.8  348.67  4893.9  346.86  4919.9  343.78  4920.2  343.28    4924  343.78
  4972.2  345.05  4993.1  344.84  5020.1  346.67  5081.4  346.72  5259.6  350.69
  5285.4  351.33  5471.7  358.37  5503.1  361.15  5513.6  360.63  5534.6  361.18
    5566  362.69  5584.3  364.88  5607.9  364.54  5654.5  366.02    5687  369.09
  5712.7  368.78  5757.2  370.33  5775.5  372.73  5796.5  372.11  5838.4  373.54
#Mann= 7 ,-1 , 0
  4468.7     .07       0  4824.1      .1       0  4919.9     .05       0
    4924      .1       0  5020.1     .05       0  5259.6     .07       0
  5285.4     .05       0
Bank Sta=4919.9,4924
XS Rating Curve= 0 ,0
Exp/Cntr=0.3,0.1

Type RM Length L Ch R = 1 ,96048   ,454,454,454
BEGIN DESCRIPTION:
CLEAR CREEK 118.0
END DESCRIPTION:
XS GIS Cut Line= 3
      2430725.02     13590475.01        2430375.       13590175.
        2429975.       13589875.
#Sta/Elev= 30
    4539  355.86  4581.3  354.98  4609.8  353.13  4652.6  351.99  4673.5  350.45
  4681.2  350.69  4737.1  348.78  4799.5  345.55  4882.2  343.31  4914.9  343.19
  4919.4  340.58  4919.7  340.08  4923.4  340.08  4923.7  340.58  4935.5  343.35
  4943.5  344.56  4950.1  344.64    4972  341.78  4992.9  342.24  4996.7  343.19
  5008.2   343.6  5071.9  344.94  5078.1   344.5  5121.9  347.01    5200  348.19
  5228.1  349.46    5249  349.34  5342.7  351.63  5392.7  353.63    5500  360.53
#Mann= 8 ,-1 , 0
    4539     .07       0  4799.5     .12       0  4882.2    .035       0
  4919.4     .05       0  4923.7    .035       0  4935.5      .1       0
  5008.2    .035       0    5249     .05       0
Bank Sta=4919.4,4923.7
XS Rating Curve= 0 ,0
Exp/Cntr=0.3,0.1

Type RM Length L Ch R = 1 ,95594   ,448,448,448
BEGIN DESCRIPTION:
CLEAR CREEK 117.0
END DESCRIPTION:
XS GIS Cut Line= 3
        2430975.       13590125.        2430675.       13589925.
      2430275.02     13589525.02
#Sta/Elev= 30
  4640.2  359.35  4676.2  357.92  4689.8   356.6  4761.9  352.53    4843  349.36
  4896.8  345.81  4921.1     344  4942.2  341.13  4951.2  340.85  4957.2  338.05
  4964.7  337.69  4976.1  335.87  4976.4  335.37  4980.1  335.37  4980.4  335.87
  4997.7  337.98  5043.2  338.51  5071.5  341.66    5139  341.55  5184.6  341.98
  5212.9  341.57    5227  342.21  5269.4  341.75    5326  344.36  5368.4  344.54
  5396.7  346.42    5425  346.53  5463.1   348.1    5524  350.88  5566.4  352.04
#Mann= 6 ,-1 , 0
  4640.2     .07       0  4896.8     .12       0  4976.1     .05       0
  4980.4     .12       0    5139     .07       0  5463.1     .05       0
Bank Sta=4976.1,4980.4
XS Rating Curve= 0 ,0
Exp/Cntr=0.3,0.1

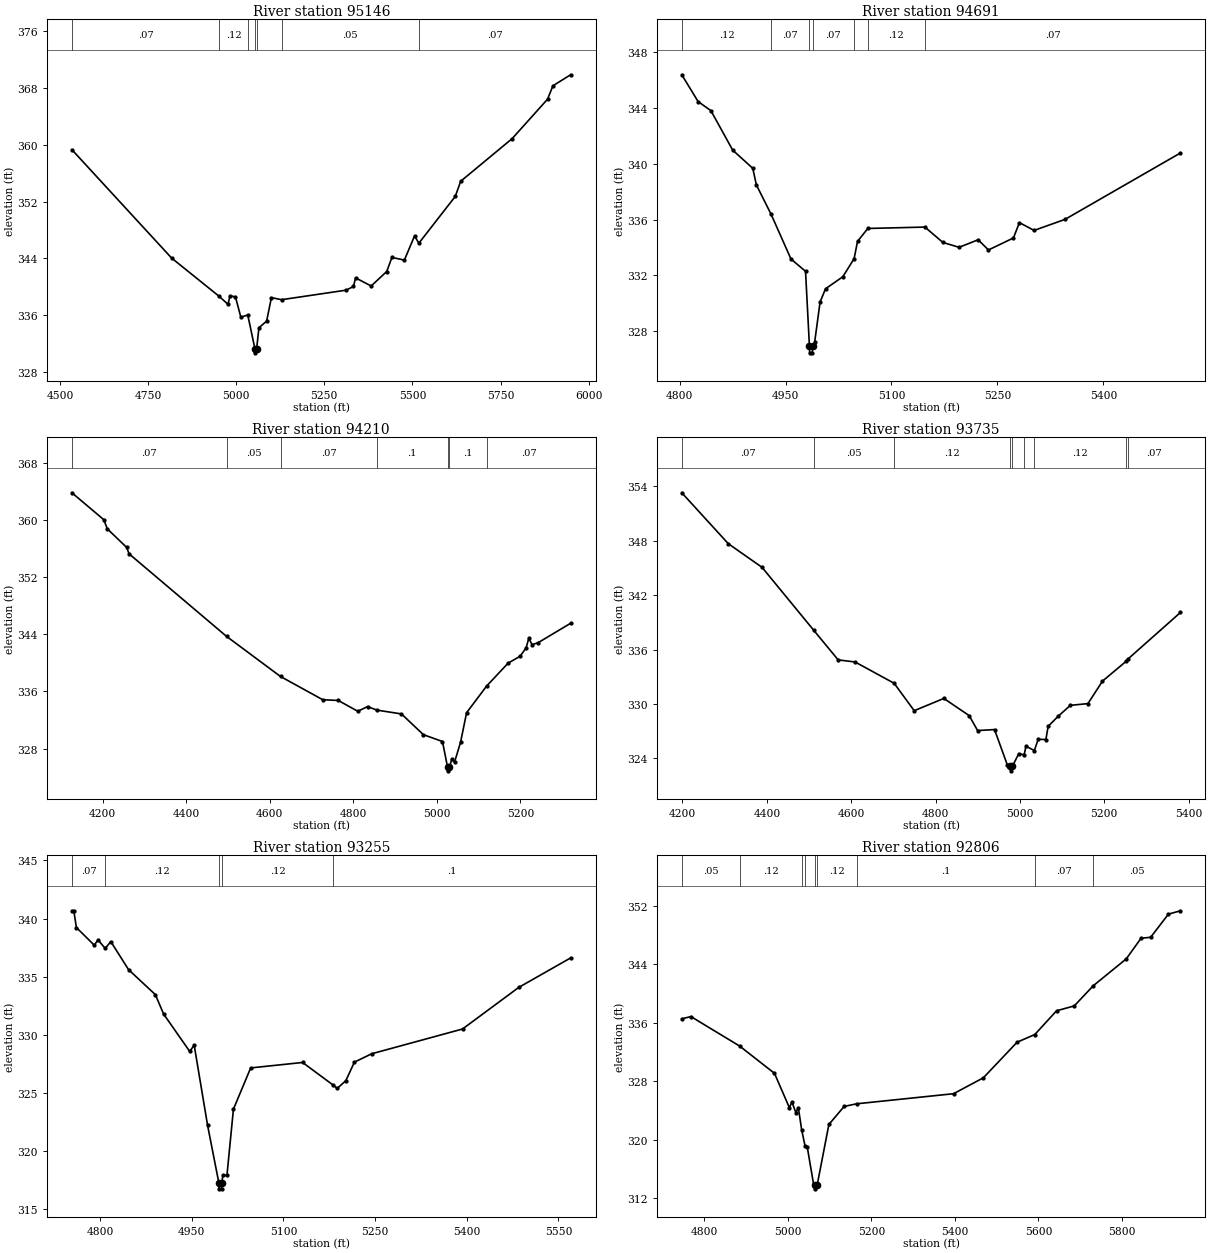
Type RM Length L Ch R = 1 ,95146   ,455,455,455
BEGIN DESCRIPTION:
CLEAR CREEK 116.0
END DESCRIPTION:
XS GIS Cut Line= 3
      2431125.02     13589975.03        2430875.       13589575.
      2430375.02     13588775.02
#Sta/Elev= 30
  4533.8  359.31  4816.9  344.03  4951.7  338.64  4976.6  337.52  4982.5  338.72
  4997.9  338.56  5013.2   335.7  5032.8  336.02  5053.4  331.18  5053.7  330.68
  5057.8  331.18  5064.5  334.21  5086.3  335.15  5099.9  338.46  5128.7  338.17
  5311.5  339.51  5332.8  340.03  5338.7  341.25  5382.9   340.1  5427.1  342.14
  5441.9  344.13  5477.2  343.75  5506.1  347.16  5518.3  346.13  5621.7  352.73
    5637  354.86  5783.2  360.88  5883.5  366.43  5898.8  368.32  5948.9  369.87
#Mann= 7 ,-1 , 0
  4533.8     .07       0  4951.7     .12       0  5032.8     .07       0
  5053.4     .05       0  5057.8     .07       0  5128.7     .05       0
  5518.3     .07       0
Bank Sta=5053.4,5057.8
XS Rating Curve= 0 ,0
Exp/Cntr=0.3,0.1

Type RM Length L Ch R = 1 ,94691   ,481,481,481
BEGIN DESCRIPTION:
CLEAR CREEK 115.0
END DESCRIPTION:
XS GIS Cut Line= 3
      2431274.99     13589574.95        2431225.       13589375.
      2430825.01       13589075.
#Sta/Elev= 30
  4803.1  346.37  4826.2  344.45  4844.3   343.8  4875.2  340.97  4903.6  339.67
  4908.7  338.48  4929.6  336.37  4957.7  333.17  4978.3  332.29  4983.8  326.95
  4984.1  326.45  4987.9  326.45  4988.2  326.95  4991.2  327.21  4998.9  330.09
  5006.6  331.04  5031.1   331.9  5047.1   333.2  5051.9  334.43  5066.5  335.36
  5147.3  335.46  5172.7  334.36  5195.7  334.01  5222.7  334.55  5237.3  333.82
  5272.7  334.68  5281.1  335.78  5301.9  335.22  5345.7  336.01  5509.2  340.77
#Mann= 7 ,-1 , 0
  4803.1     .12       0  4929.6     .07       0  4983.8     .05       0
  4988.2     .07       0  5047.1      .1       0  5066.5     .12       0
  5147.3     .07       0
Bank Sta=4983.8,4988.2
XS Rating Curve= 0 ,0
Exp/Cntr=0.3,0.1

Type RM Length L Ch R = 1 ,94210   ,475,475,475
BEGIN DESCRIPTION:
CLEAR CREEK 114.0
END DESCRIPTION:
XS GIS Cut Line= 3
        2431675.     13589775.01        2431325.       13588975.
      2431074.98     13588774.99
#Sta/Elev= 30
  4126.5  363.86  4202.9  360.08  4211.1  358.81  4257.5   356.2  4263.3   355.3
  4496.6  343.72  4625.7   338.1  4726.8  334.84  4763.9  334.74  4810.7  333.22
    4834  333.88    4856  333.39  4915.1  332.85  4967.4  329.95  5013.3  328.98
  5025.5  325.37  5025.8  324.87    5030  325.37  5035.7  326.53  5042.1  326.08
  5056.6  328.88    5071  333.02  5118.8  336.75  5170.2  339.96    5199  340.94
  5213.4   342.1  5219.8  343.45  5227.8  342.56  5242.2  342.84  5319.9  345.56
#Mann= 7 ,-1 , 0
  4126.5     .07       0  4496.6     .05       0  4625.7     .07       0
    4856      .1       0  5025.5     .05       0    5030      .1       0
  5118.8     .07       0
Bank Sta=5025.5,5030
XS Rating Curve= 0 ,0
Exp/Cntr=0.3,0.1

Type RM Length L Ch R = 1 ,93735   ,480,480,480
BEGIN DESCRIPTION:
CLEAR CREEK 113.0
END DESCRIPTION:
XS GIS Cut Line= 3
        2431775.     13589574.96        2431725.       13588775.
      2431375.01       13588625.
#Sta/Elev= 30
  4198.4  353.28  4308.6  347.67  4388.7  345.06  4510.9  338.14  4569.1  334.86
  4609.2  334.63  4701.9  332.28  4749.4  329.26  4819.6  330.61  4879.7  328.72
  4899.7  327.07  4939.8  327.18  4969.9  323.32  4977.6  323.13  4977.9  322.63
  4982.2  323.13  4997.4  324.53    5010  324.39  5014.4  325.34  5034.2  324.87
  5043.4  326.11  5061.6  326.08    5067  327.54  5090.6  328.64  5119.6  329.85
  5161.3  330.04  5195.8  332.52    5252  334.71  5256.5  334.97  5380.7  340.09
#Mann= 9 ,-1 , 0
  4198.4     .07       0  4510.9     .05       0  4701.9     .12       0
  4977.6     .05       0  4982.2     .12       0    5010      .1       0
  5034.2     .12       0    5252      .1       0  5256.5     .07       0
Bank Sta=4977.6,4982.2
XS Rating Curve= 0 ,0
Exp/Cntr=0.3,0.1

Type RM Length L Ch R = 1 ,93255   ,449,449,449
BEGIN DESCRIPTION:
CLEAR CREEK 112.0
END DESCRIPTION:
XS GIS Cut Line= 3
      2432275.01     13588725.01        2432075.       13588575.
        2431675.       13588175.
#Sta/Elev= 30
  4754.1  340.67  4757.2  340.67  4761.4  339.23  4790.6  337.71  4796.8  338.16
  4808.6  337.43  4817.7  338.02  4846.8   335.6  4890.6  333.45  4904.1  331.78
  4946.8  328.56  4954.1   329.1    4976   322.2  4994.5  317.23  4994.8  316.73
  4998.8  316.73  4999.2  317.23    5001  317.89  5007.7  317.89  5018.3  323.59
  5046.5  327.14  5131.4  327.61  5181.5  325.66    5188  325.37  5202.1  326.04
  5216.2  327.64  5244.5  328.36    5393  330.49  5484.9  334.07  5569.8  336.61
#Mann= 5 ,-1 , 0
  4754.1     .07       0  4808.6     .12       0  4994.5     .05       0
  4999.2     .12       0  5181.5      .1       0
Bank Sta=4994.5,4999.2
XS Rating Curve= 0 ,0
Exp/Cntr=0.3,0.1

Type RM Length L Ch R = 1 ,92806   ,466,466,466
BEGIN DESCRIPTION:
CLEAR CREEK 111.0
END DESCRIPTION:
XS GIS Cut Line= 3
      2432524.98     13588374.98        2432325.       13588225.
      2431524.97     13587724.98
#Sta/Elev= 30
  4746.4  336.53  4768.2  336.84  4884.9   332.8  4968.2  329.07    5004  324.35
  5009.9  325.17  5019.4  323.68  5025.3  324.37  5033.2  321.36  5041.3  319.14
  5046.5  319.03  5061.8  313.88  5065.2  313.76  5065.6  313.26  5070.3  313.76
  5098.4  322.07  5134.9  324.54  5164.9   324.9  5396.7  326.28  5468.1  328.46
  5548.8  333.33  5591.2  334.38  5643.2  337.63  5685.6   338.3  5731.1  341.06
  5810.1  344.74  5845.4  347.56  5868.4  347.69  5910.9  350.86  5939.8  351.32
#Mann= 9 ,-1 , 0
  4746.4     .05       0  4884.9     .12       0  5033.2     .07       0
  5041.3     .12       0  5065.2     .05       0  5070.3     .12       0
  5164.9      .1       0  5591.2     .07       0  5731.1     .05       0
Bank Sta=5065.2,5070.3
XS Rating Curve= 0 ,0
Exp/Cntr=0.3,0.1