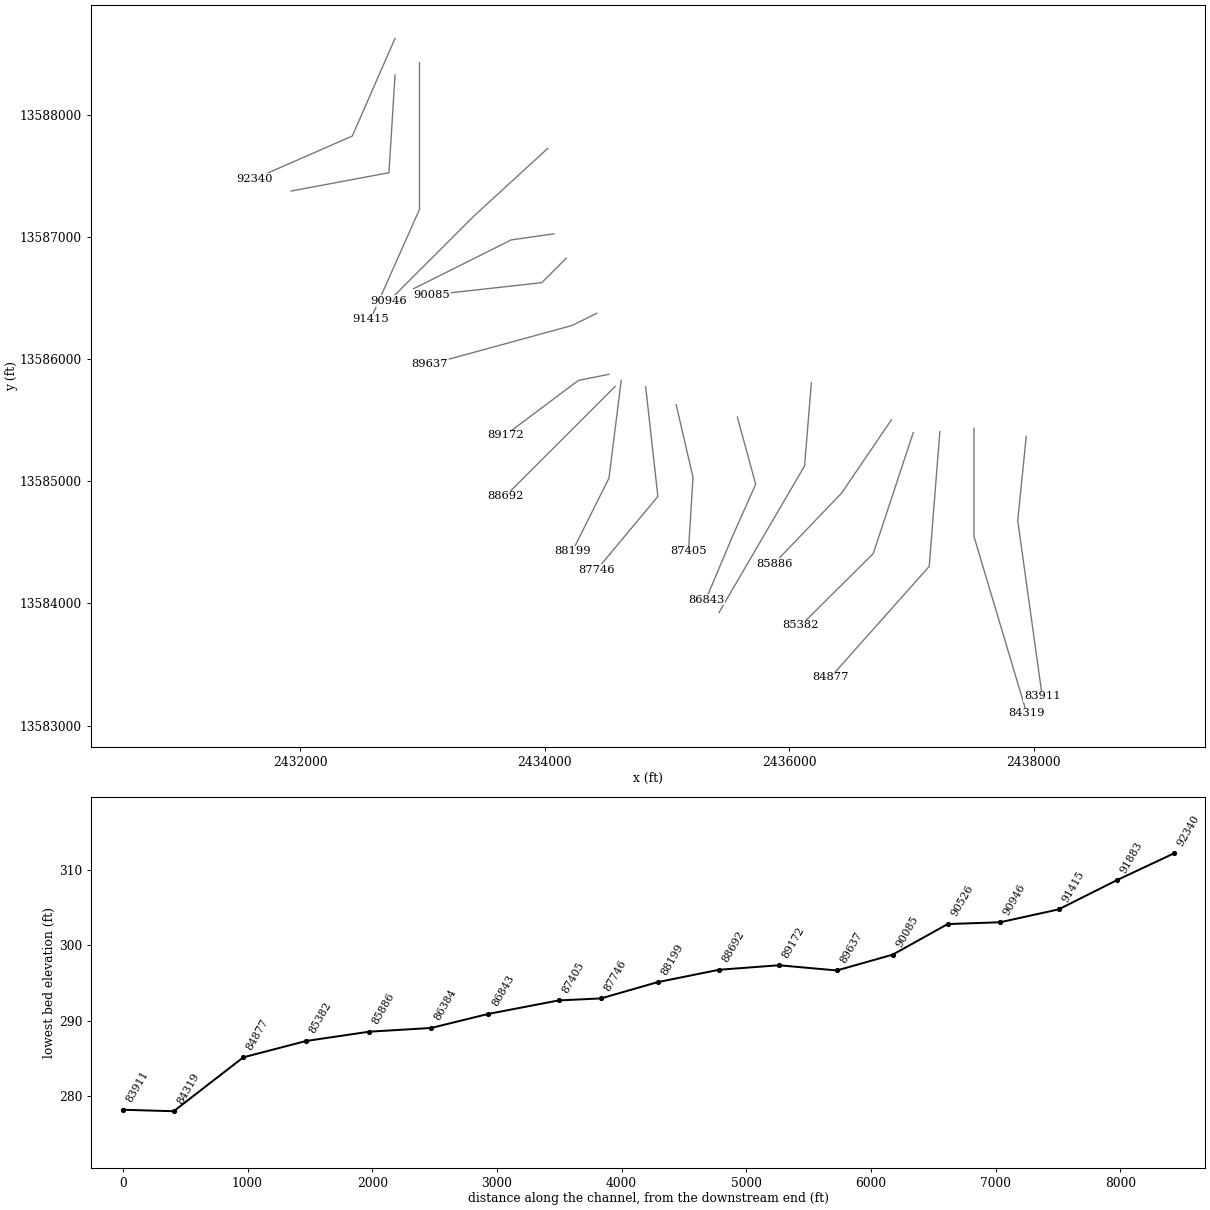
HEC-RAS study CLEAR CREEK.prj: CLEAR CREEK Base Level Engineering

--- CLEAR CREEK.g01 (geometry) --- (continued)

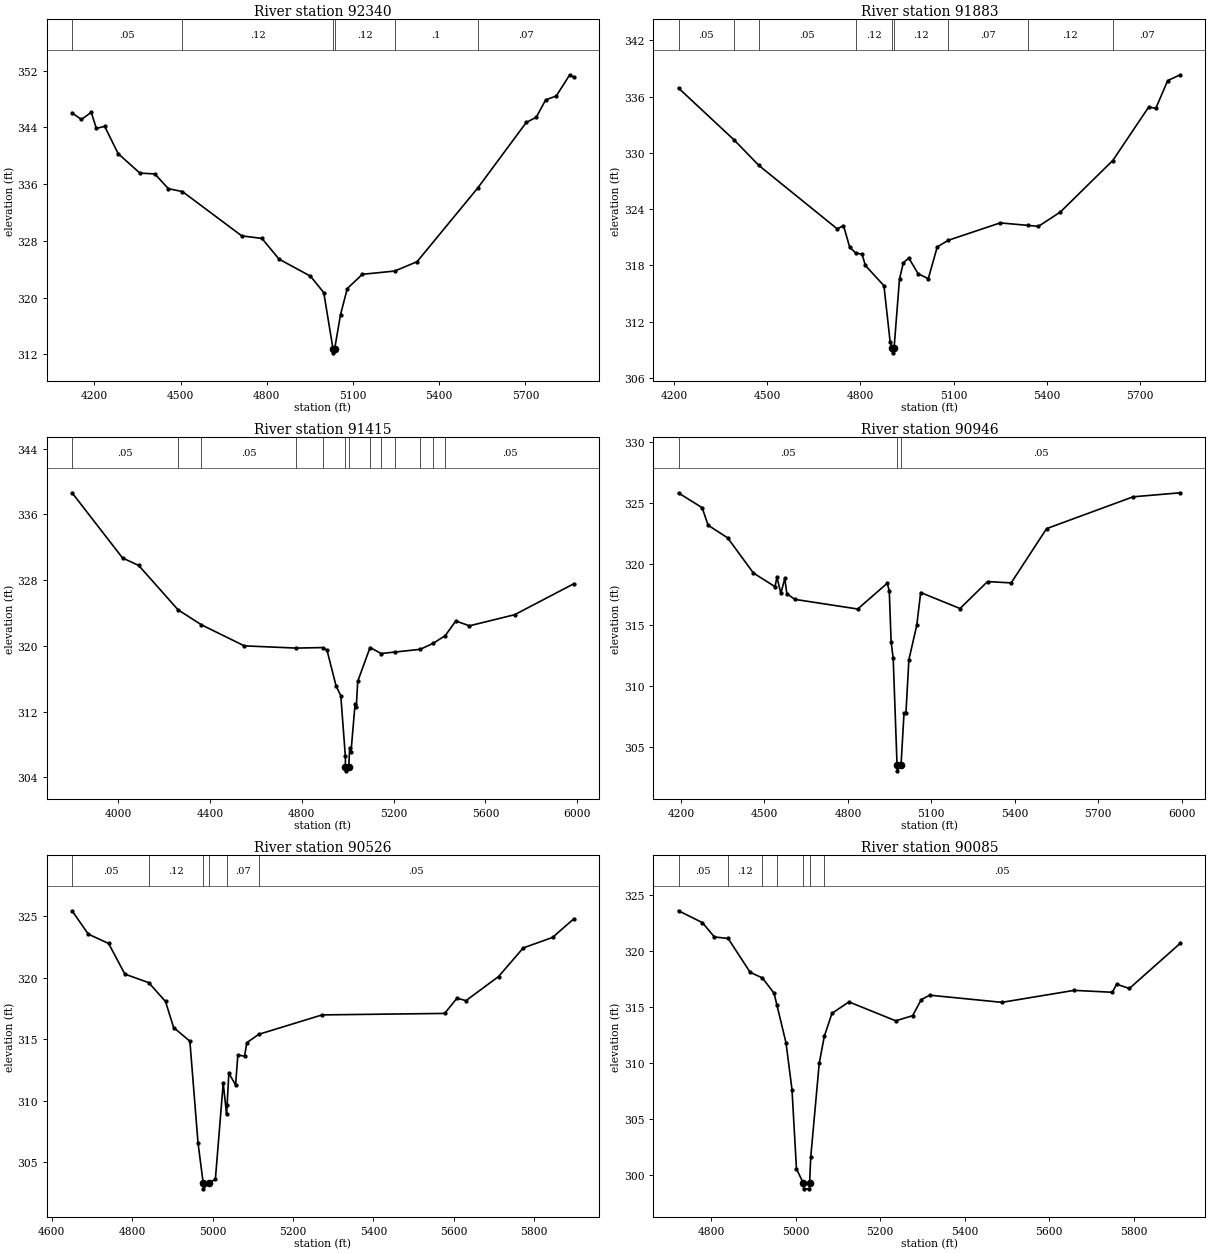
Type RM Length L Ch R = 1 ,92340   ,457,457,457
BEGIN DESCRIPTION:
CLEAR CREEK 110.0
END DESCRIPTION:
XS GIS Cut Line= 3
        2432775.     13588625.01        2432425.       13587825.
      2431625.03     13587475.01
#Sta/Elev= 30
  4122.2  346.05  4154.6  345.13  4188.9  346.13  4206.8  343.87  4235.7  344.16
  4282.4  340.32  4358.1  337.57  4410.3  337.45  4457.1  335.38  4506.5  334.96
  4712.8  328.72    4783  328.36  4842.6  325.44  4951.8  323.04  4998.2  320.72
  5030.6  312.73    5031  312.23  5035.8  312.73  5056.6  317.63    5080  321.29
  5132.3   323.3  5245.3  323.76  5322.9  325.08  5534.3  335.48    5703  344.71
  5737.7  345.44  5770.4  347.89  5807.4  348.44  5854.2  351.43  5868.6   351.1
#Mann= 6 ,-1 , 0
  4122.2     .05       0  4506.5     .12       0  5030.6     .05       0
  5035.8     .12       0  5245.3      .1       0  5534.3     .07       0
Bank Sta=5030.6,5035.8
XS Rating Curve= 0 ,0
Exp/Cntr=0.3,0.1

Type RM Length L Ch R = 1 ,91883   ,468,468,468
BEGIN DESCRIPTION:
CLEAR CREEK 109.0
END DESCRIPTION:
XS GIS Cut Line= 3
        2432775.     13588324.98        2432725.       13587525.
      2431924.98       13587375.
#Sta/Elev= 30
  4214.3  336.91  4393.2  331.38  4472.9  328.66  4725.3  321.89  4745.3  322.25
  4765.4  319.93  4785.1  319.31  4805.4  319.19  4815.5     318  4875.6  315.83
  4895.6  309.82    4903  309.17  4903.4  308.67  4908.2  309.17  4925.7  316.55
  4938.2  318.29  4955.7  318.78  4985.8   317.1  5018.4  316.58  5047.2  319.97
    5083  320.68  5249.8  322.53    5338  322.27  5372.8  322.16  5443.2  323.68
  5612.2  329.18    5728  334.89  5750.9  334.75  5789.1  337.71  5829.8  338.33
#Mann= 9 ,-1 , 0
  4214.3     .05       0  4393.2     .12       0  4472.9     .05       0
  4785.1     .12       0    4903     .05       0  4908.2     .12       0
    5083     .07       0    5338     .12       0  5612.2     .07       0
Bank Sta=4903,4908.2
XS Rating Curve= 0 ,0
Exp/Cntr=0.3,0.1

Type RM Length L Ch R = 1 ,91415   ,469,469,469
BEGIN DESCRIPTION:
CLEAR CREEK 108.0
END DESCRIPTION:
XS GIS Cut Line= 3
        2432975.     13588425.01        2432975.       13587225.
        2432575.     13586324.99
#Sta/Elev= 30
    3800  338.62    4020  330.68    4090  329.78  4261.7  324.37  4363.4  322.55
    4550  319.99  4774.9  319.72  4890.9  319.78    4910  319.46    4950  315.07
    4970  313.94    4990  306.53  4990.3  305.28  4990.8  304.78  5004.7  305.28
  5008.9  307.61  5014.4  307.03  5032.2   312.9  5037.6  312.57  5043.8  315.67
  5097.5  319.79  5145.6  319.06  5206.8  319.24    5316  319.57  5373.1  320.31
  5425.2  321.24  5470.6  323.02  5530.1  322.43    5727  323.78  5984.9  327.55
#Mann= 13 ,-1 , 0
    3800     .05       0  4261.7     .12       0  4363.4     .05       0
  4774.9     .07       0  4890.9      .1       0  4990.3     .05       0
  5004.7      .1       0  5097.5     .07       0  5145.6      .1       0
  5206.8     .07       0    5316     .05       0  5373.1     .07       0
  5425.2     .05       0
Bank Sta=4990.3,5004.7
XS Rating Curve= 0 ,0
Exp/Cntr=0.3,0.1

Type RM Length L Ch R = 1 ,90946   ,420,420,420
BEGIN DESCRIPTION:
CLEAR CREEK 107.0
END DESCRIPTION:
XS GIS Cut Line= 3
      2434025.01     13587725.01        2433425.       13587175.
      2432725.01     13586475.01
#Sta/Elev= 30
  4191.2  325.85    4276  324.65  4297.6  323.21  4367.9  322.17  4460.4  319.29
  4538.1  318.17  4544.9  318.95    4559  317.62  4573.2  318.85  4580.6   317.6
    4609  317.13  4835.3  316.34  4941.3  318.45  4948.7  317.85  4955.5  313.62
  4962.9   312.3  4976.7  303.57  4977.2  303.07  4991.1  303.57  5001.8   307.8
  5008.7   307.8  5019.3  312.19  5047.6     315  5061.7  317.69  5203.2  316.38
  5302.1  318.59    5387  318.48  5514.3  322.93  5825.4  325.54  5995.1  325.87
#Mann= 3 ,-1 , 0
  4191.2     .05       0  4976.7     .05       0  4991.1     .05       0
Bank Sta=4976.7,4991.1
XS Rating Curve= 0 ,0
Exp/Cntr=0.3,0.1

Type RM Length L Ch R = 1 ,90526   ,441,441,441
BEGIN DESCRIPTION:
CLEAR CREEK 106.0
END DESCRIPTION:
XS GIS Cut Line= 3
      2434075.02       13587025.        2433725.       13586975.
        2432925.       13586575.
#Sta/Elev= 30
  4650.6  325.45    4691  323.55  4741.5  322.79  4781.9   320.3  4841.4   319.6
    4883  318.07  4903.2  315.95  4943.6  314.84  4963.8  306.58  4976.6  303.33
  4977.1  302.83  4991.3  303.33    5007   303.6  5026.5  311.43  5034.9  308.89
  5036.2  309.67  5040.5  312.24  5057.3  311.28  5062.9  313.72  5079.6  313.62
  5085.2  314.72  5114.9   315.4  5272.5  316.98  5577.2   317.1  5607.9  318.34
  5630.3  318.14  5711.3   320.1  5772.8  322.43  5845.5  323.28  5898.6   324.8
#Mann= 6 ,-1 , 0
  4650.6     .05       0  4841.4     .12       0  4976.6     .05       0
  4991.3     .12       0  5036.2     .07       0  5114.9     .05       0
Bank Sta=4976.6,4991.3
XS Rating Curve= 0 ,0
Exp/Cntr=0.3,0.1

Type RM Length L Ch R = 1 ,90085   ,448,448,448
BEGIN DESCRIPTION:
CLEAR CREEK 105.0
END DESCRIPTION:
XS GIS Cut Line= 3
      2434175.03     13586825.03        2433975.       13586625.
      2433075.02       13586525.
#Sta/Elev= 30
  4722.2   323.6  4778.8  322.54  4807.1  321.26  4839.6  321.13  4891.9   318.1
  4920.9   317.6  4948.5  316.23  4955.2  315.18  4976.8  311.79  4990.9  307.63
  5001.5  300.54  5017.9  299.26  5018.4  298.76  5032.1  298.76  5032.6  299.26
  5035.3   301.6  5055.4  309.97  5067.4  312.38  5085.6  314.44  5125.8  315.46
  5236.5  313.77  5276.7  314.23  5296.9  315.66    5317  316.06    5488  315.42
  5659.1  316.49  5749.6  316.32  5759.7  317.04  5789.9  316.66  5910.6   320.7
#Mann= 7 ,-1 , 0
  4722.2     .05       0  4839.6     .12       0  4920.9     .05       0
  4955.2     .12       0  5017.9     .05       0  5032.6     .12       0
  5067.4     .05       0
Bank Sta=5017.9,5032.6
XS Rating Curve= 0 ,0
Exp/Cntr=0.3,0.1

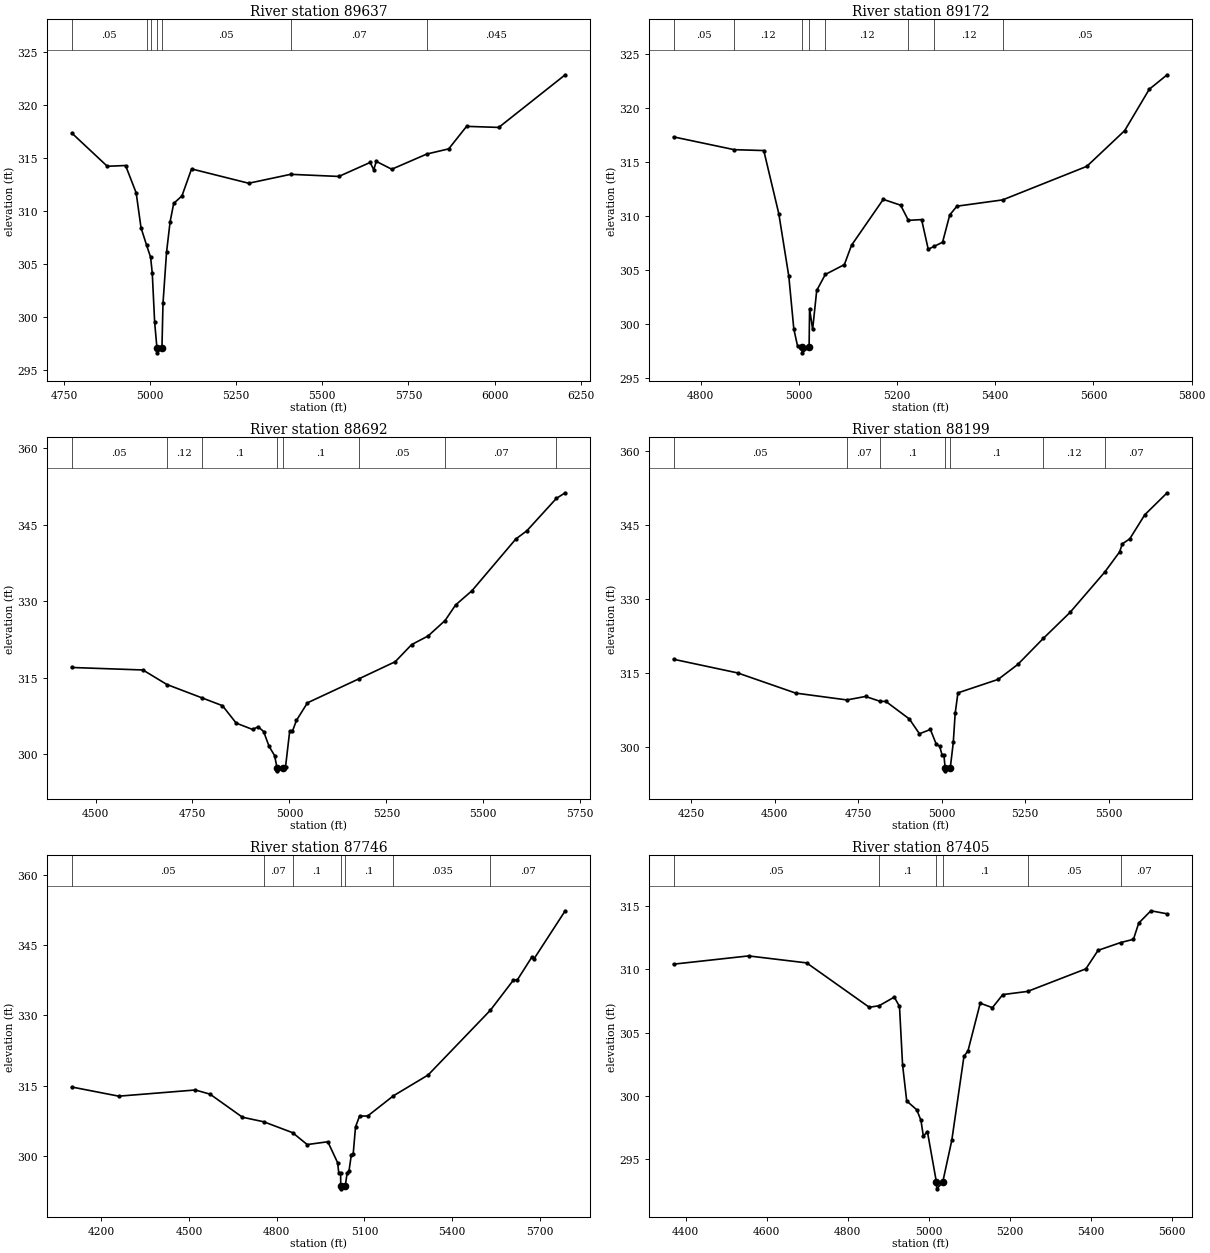
Type RM Length L Ch R = 1 ,89637   ,465,465,465
BEGIN DESCRIPTION:
CLEAR CREEK 104.0
END DESCRIPTION:
XS GIS Cut Line= 3
      2434425.02     13586375.01        2434225.       13586275.
      2433058.94     13585955.78
#Sta/Elev= 30
  4772.4  317.38  4875.8  314.24  4928.9  314.31  4959.7  311.73  4973.7  308.45
  4990.1  306.78  5001.6  305.66  5006.4  304.16  5013.3  299.54  5019.8  297.16
  5020.3  296.66  5034.5  297.16  5037.5  301.31  5047.8  306.14  5058.2  309.02
  5068.6  310.74  5092.6  311.45  5120.4  313.99  5286.3  312.64    5408  313.48
  5547.9  313.28  5638.8   314.6  5649.2  313.91  5656.6   314.7  5701.5  313.96
  5803.1  315.39  5866.9  315.88  5918.7     318  6012.1   317.9    6205  322.86
#Mann= 7 ,-1 , 0
  4772.4     .05       0  4990.1     .12       0  5001.6     .05       0
  5019.8     .05       0  5034.5     .05       0    5408     .07       0
  5803.1    .045       0
Bank Sta=5019.8,5034.5
XS Rating Curve= 0 ,0
Exp/Cntr=0.3,0.1

Type RM Length L Ch R = 1 ,89172   ,480,480,480
BEGIN DESCRIPTION:
CLEAR CREEK 103.0
END DESCRIPTION:
XS GIS Cut Line= 3
      2434525.03     13585875.01        2434275.       13585825.
      2433674.98     13585374.99
#Sta/Elev= 30
  4745.1   317.3  4868.6  316.12  4928.7  316.04  4959.3  310.21  4979.7  304.42
  4989.9  299.55  4997.5  297.98  5006.3  297.85  5006.8  297.35    5021  297.85
    5022  301.43  5028.2  299.51  5036.5  303.11    5054  304.59  5092.8   305.5
  5107.4  307.29    5172  311.53  5207.4  310.99  5223.2  309.59  5250.1  309.66
  5263.6  306.92  5276.2   307.2  5292.8  307.57  5307.4  310.09    5322   310.9
  5415.1  311.48  5586.5  314.58  5663.6  317.88  5713.6   321.7  5750.1  323.04
#Mann= 8 ,-1 , 0
  4745.1     .05       0  4868.6     .12       0  5006.3     .05       0
    5021     .12       0    5054     .12       0  5223.2      .1       0
  5276.2     .12       0  5415.1     .05       0
Bank Sta=5006.3,5021
XS Rating Curve= 0 ,0
Exp/Cntr=0.3,0.1

Type RM Length L Ch R = 1 ,88692   ,493,493,493
BEGIN DESCRIPTION:
CLEAR CREEK 102.0
END DESCRIPTION:
XS GIS Cut Line= 3
        2434575.       13585775.        2434175.       13585375.
        2433675.       13584875.
#Sta/Elev= 30
  4438.5  317.02  4622.3  316.53  4684.1  313.68  4774.3  311.07  4827.4  309.53
  4862.8  306.11  4905.2  304.86  4919.3   305.4  4933.5  304.46  4947.6  301.55
  4961.8  299.74  4968.4  297.25  4968.9  296.75  4983.5  297.25    4990  297.48
  5000.7   304.5  5007.7   304.5  5018.3  306.66  5046.6  310.09    5180  314.82
  5272.9  318.15  5315.3  321.51  5357.7   323.2  5401.5  326.23  5428.5  329.27
  5470.9  332.08    5584  342.22  5612.3  343.82  5688.5  350.18  5711.3  351.28
#Mann= 8 ,-1 , 0
  4438.5     .05       0  4684.1     .12       0  4774.3      .1       0
  4968.4     .05       0  4983.5      .1       0    5180     .05       0
  5401.5     .07       0  5688.5    .035       0
Bank Sta=4968.4,4983.5
XS Rating Curve= 0 ,0
Exp/Cntr=0.3,0.1

Type RM Length L Ch R = 1 ,88199   ,453,453,453
BEGIN DESCRIPTION:
CLEAR CREEK 101.0
END DESCRIPTION:
XS GIS Cut Line= 3
        2434625.       13585825.        2434525.       13585025.
      2434225.02     13584425.04
#Sta/Elev= 30
  4197.9  317.76  4389.4  314.99  4563.2  310.89  4716.6   309.5  4772.3  310.21
  4816.3  309.21  4832.8  309.21  4903.3  305.64  4933.6  302.63  4966.3   303.5
    4984   300.5    4994   300.1  5001.6  298.25  5006.9  298.25  5010.6   295.6
  5011.1   295.1  5025.7   295.6  5034.9  300.89  5040.5  306.77  5048.8  310.94
    5169  313.67  5227.7   316.7  5304.1  321.99  5384.3  327.28    5488  335.46
  5532.4  339.55  5540.8  341.21  5563.1  342.23  5607.9  347.11  5674.9  351.58
#Mann= 7 ,-1 , 0
  4197.9     .05       0  4716.6     .07       0  4816.3      .1       0
  5010.6     .05       0  5025.7      .1       0  5304.1     .12       0
    5488     .07       0
Bank Sta=5010.6,5025.7
XS Rating Curve= 0 ,0
Exp/Cntr=0.3,0.1

Type RM Length L Ch R = 1 ,87746   ,341,341,341
BEGIN DESCRIPTION:
CLEAR CREEK 100.0
END DESCRIPTION:
XS GIS Cut Line= 3
        2434825.     13585775.03        2434925.       13584875.
      2434424.99     13584274.99
#Sta/Elev= 30
  4099.3   314.7  4260.3  312.74  4521.9  314.06  4572.2  313.17  4682.9  308.24
  4755.5  307.27  4854.3  304.94  4904.2   302.4  4974.7     303  5008.1  298.53
    5012   296.4  5018.5  296.34  5018.7  293.44  5019.2  292.94  5033.9  293.44
  5040.7   296.3  5047.2  296.83    5055  300.21  5061.5  300.48  5069.3  306.16
    5083  308.48    5111  308.51  5198.9  312.82  5317.3  317.26  5530.3  331.11
  5608.2  337.49  5622.5   337.6    5672  342.47  5679.8  342.13  5785.9  352.35
#Mann= 7 ,-1 , 0
  4099.3     .05       0  4755.5     .07       0  4854.3      .1       0
  5018.7     .05       0  5033.9      .1       0  5198.9    .035       0
  5530.3     .07       0
Bank Sta=5018.7,5033.9
XS Rating Curve= 0 ,0
Exp/Cntr=0.3,0.1

Type RM Length L Ch R = 1 ,87405   ,562,562,562
BEGIN DESCRIPTION:
CLEAR CREEK 99.0
END DESCRIPTION:
XS GIS Cut Line= 3
      2435075.01     13585624.95      2435212.48     13585030.79
        2435175.     13584425.01
#Sta/Elev= 30
  4370.6  310.39  4555.3  311.04  4698.6  310.49    4853  306.99  4877.3  307.11
  4914.6  307.79  4927.5  307.06  4935.1  302.45  4945.3   299.6  4970.2   298.9
  4980.5  298.06  4986.3  296.82  4996.3  297.19  5018.7  293.17  5019.2  292.67
  5033.9  293.17  5056.4  296.49  5086.4  303.11  5096.5  303.57  5126.5  307.31
  5156.6  306.96  5182.1  307.99  5243.3  308.24    5387  310.02  5417.1  311.48
  5472.4  312.09  5504.3  312.35  5517.3  313.63  5547.3   314.6  5587.4  314.36
#Mann= 6 ,-1 , 0
  4370.6     .05       0  4877.3      .1       0  5018.7     .05       0
  5033.9      .1       0  5243.3     .05       0  5472.4     .07       0
Bank Sta=5018.7,5033.9
XS Rating Curve= 0 ,0
Exp/Cntr=0.3,0.1

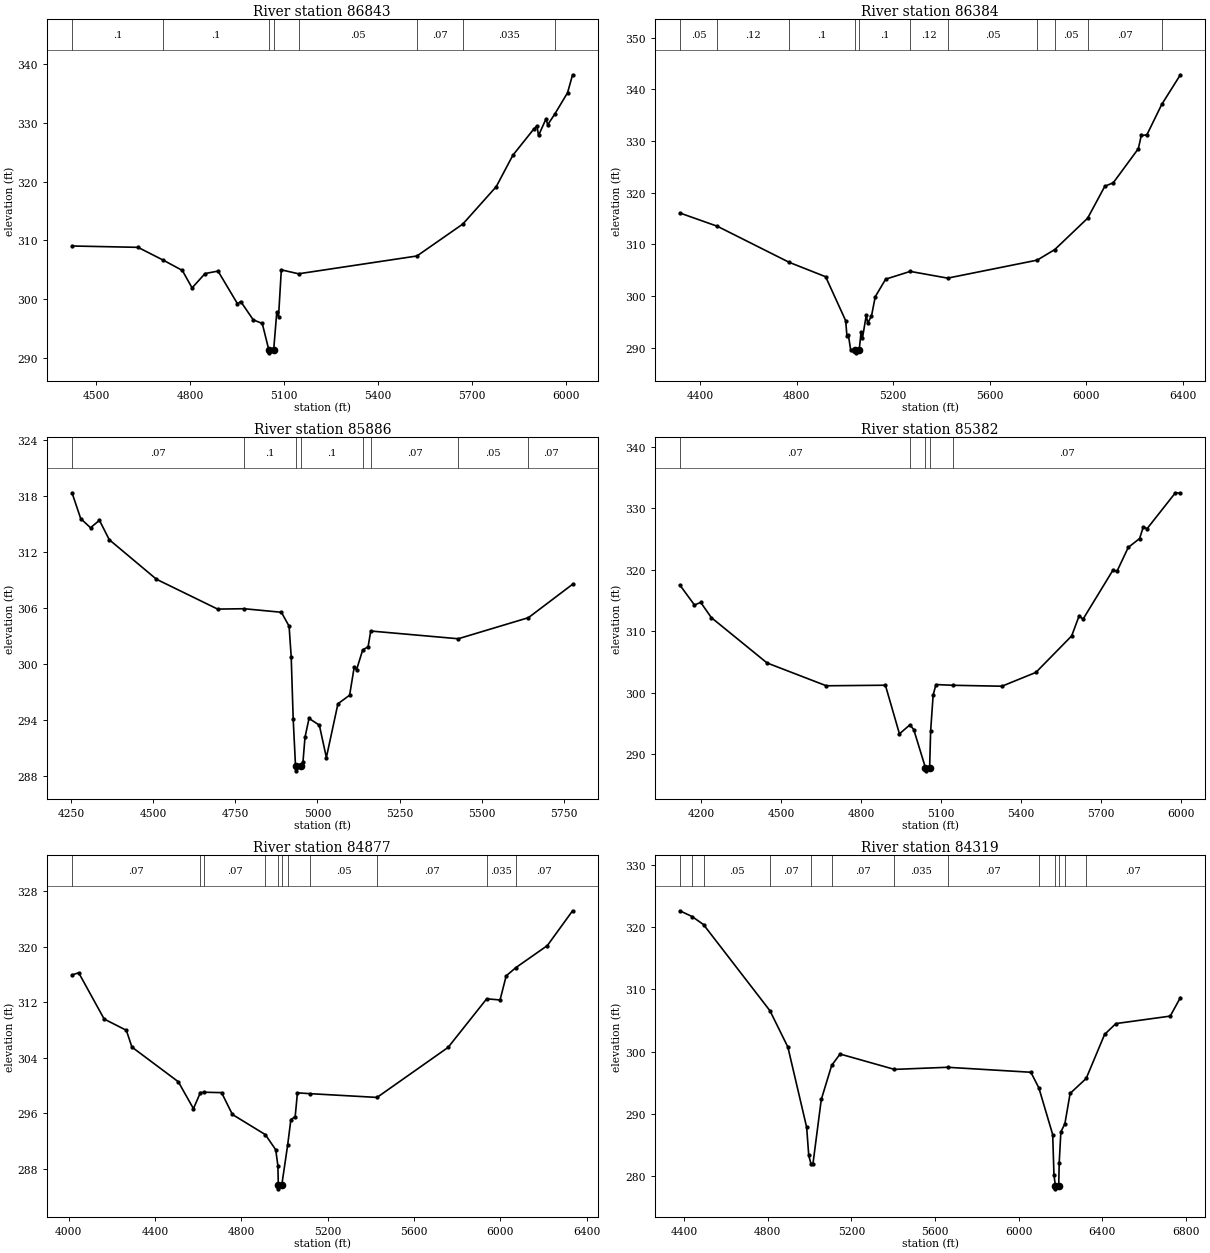
Type RM Length L Ch R = 1 ,86843   ,459,459,459
BEGIN DESCRIPTION:
CLEAR CREEK 98.0
END DESCRIPTION:
XS GIS Cut Line= 4
        2435575.     13585525.01        2435725.       13584975.
      2435535.84     13584549.39       2435317.7      13584030.2
#Sta/Elev= 30
  4423.4  309.06  4634.2  308.83  4715.6  306.63  4775.8   304.9  4806.9  301.93
  4848.4  304.37  4889.8  304.79    4952  299.23  4962.4  299.61  5002.4  296.49
  5031.1  295.88  5052.1  291.38  5052.6  290.88  5067.6  291.38  5077.6  297.87
  5083.1  297.01    5092     305  5147.1  304.33  5525.3  307.36  5671.9   312.8
  5778.6  319.16  5831.6   324.5  5897.9  328.92  5908.3  329.49  5913.7  327.86
  5937.4  330.68  5942.9  329.68  5965.8  331.53  6006.3  335.13  6022.4  338.19
#Mann= 8 ,-1 , 0
  4423.4      .1       0  4715.6      .1       0  5052.1     .05       0
  5067.6      .1       0  5147.1     .05       0  5525.3     .07       0
  5671.9    .035       0  5965.8     .07       0
Bank Sta=5052.1,5067.6
XS Rating Curve= 0 ,0
Exp/Cntr=0.3,0.1

Type RM Length L Ch R = 1 ,86384   ,498,498,498
BEGIN DESCRIPTION:
CLEAR CREEK 97.0
END DESCRIPTION:
XS GIS Cut Line= 3
      2436180.77     13585807.14        2436125.       13585125.
      2435424.98     13583924.97
#Sta/Elev= 30
  4315.8  316.06  4471.4  313.49  4768.7  306.52  4919.9  303.73  5003.1  295.21
  5008.1  292.26  5013.9   292.5  5023.4  289.65  5043.3  289.51  5043.8  289.01
  5058.8  289.51  5066.8  293.04  5072.6   291.9  5088.3  296.31  5094.1  294.76
  5109.8  296.12  5125.5  299.87  5168.5  303.26  5270.4  304.76  5425.3  303.46
  5796.2  306.94  5869.3  308.99  6005.3  315.05  6076.5  321.23  6111.6  321.91
  6215.4   328.5  6227.4  331.05  6250.5  331.16  6312.4  337.07  6389.5  342.79
#Mann= 11 ,-1 , 0
  4315.8     .05       0  4471.4     .12       0  4768.7      .1       0
  5043.3     .05       0  5058.8      .1       0  5270.4     .12       0
  5425.3     .05       0  5796.2     .07       0  5869.3     .05       0
  6005.3     .07       0  6312.4    .035       0
Bank Sta=5043.3,5058.8
XS Rating Curve= 0 ,0
Exp/Cntr=0.3,0.1

Type RM Length L Ch R = 1 ,85886   ,504,504,504
BEGIN DESCRIPTION:
CLEAR CREEK 96.0
END DESCRIPTION:
XS GIS Cut Line= 3
        2436835.     13585501.82      2436429.39      13584904.3
      2435875.01     13584325.01
#Sta/Elev= 30
  4252.9  318.32  4279.4  315.55  4309.3  314.57  4336.4  315.37  4366.3  313.29
    4510  309.05  4696.3  305.85  4776.7  305.89  4890.3  305.51  4913.8  304.02
  4920.2  300.75  4926.3  294.06  4933.4  289.01  4933.9  288.51  4949.1  289.01
  4956.2  289.51  4962.2   292.1  4974.5  294.13  5005.9  293.41  5027.3  289.94
  5062.5   295.7  5098.1  296.62  5112.2  299.67  5119.1  299.34  5137.8  301.46
  5154.4  301.82  5162.4   303.5  5428.8  302.67  5642.4  304.93  5776.9  308.51
#Mann= 8 ,-1 , 0
  4252.9     .07       0  4776.7      .1       0  4933.4     .05       0
  4949.1      .1       0  5137.8     .12       0  5162.4     .07       0
  5428.8     .05       0  5642.4     .07       0
Bank Sta=4933.4,4949.1
XS Rating Curve= 0 ,0
Exp/Cntr=0.3,0.1

Type RM Length L Ch R = 1 ,85382   ,505,505,505
BEGIN DESCRIPTION:
X18474
END DESCRIPTION:
XS GIS Cut Line= 3
      2437013.84     13585397.12      2436686.73     13584407.07
       2436094.4      13583819.1
#Sta/Elev= 30
  4120.4   317.5  4175.3  314.25    4199  314.66  4238.5   312.2  4447.6  304.82
  4669.8  301.11  4891.4   301.2  4944.1  293.29  4983.3  294.76  4997.7  293.99
  5041.6  287.78  5042.1  287.28  5057.3  287.78  5061.1  293.77  5070.5  299.61
    5081  301.31  5144.2  301.19  5328.4  301.04  5455.7  303.28    5590  309.22
  5618.3  312.52  5632.5  311.93  5745.6  319.97  5759.7   319.7  5802.2  323.61
  5844.6  325.04  5858.7  326.95  5872.9  326.66    5979  332.49  5997.7  332.44
#Mann= 5 ,-1 , 0
  4120.4     .07       0  4983.3      .1       0  5041.6     .05       0
  5057.3      .1       0  5144.2     .07       0
Bank Sta=5041.6,5057.3
XS Rating Curve= 0 ,0
Exp/Cntr=0.3,0.1

Type RM Length L Ch R = 1 ,84877   ,558,558,558
BEGIN DESCRIPTION:
CLEAR CREEK 95.0
END DESCRIPTION:
XS GIS Cut Line= 3
      2437231.94     13585405.93       2437144.7     13584302.39
      2436338.88     13583396.39
#Sta/Elev= 30
  4015.7  315.94  4046.7  316.25  4164.7  309.58  4267.4  307.96  4293.3  305.54
  4508.2  300.54  4578.4  296.66  4610.5  298.97  4626.7  299.03  4708.8  298.97
  4758.9  295.82  4911.4  292.92  4959.6  290.74  4969.6  288.46  4971.7   285.6
  4972.2   285.1  4987.5   285.6    5015  291.42  5029.8  295.08  5049.8  295.51
  5060.2  298.94  5119.9  298.82  5429.1  298.28  5758.3  305.49  5937.3   312.5
  5999.1  312.33  6027.6  315.81  6072.6     317  6218.2  320.17  6335.2  325.19
#Mann= 11 ,-1 , 0
  4015.7     .07       0  4610.5     .12       0  4626.7     .07       0
  4911.4      .1       0  4971.7     .05       0  4987.5      .1       0
    5015     .07       0  5119.9     .05       0  5429.1     .07       0
  5937.3    .035       0  6072.6     .07       0
Bank Sta=4971.7,4987.5
XS Rating Curve= 0 ,0
Exp/Cntr=0.3,0.1

Type RM Length L Ch R = 1 ,84319   ,408,408,408
BEGIN DESCRIPTION:
CLEAR CREEK 94.0
END DESCRIPTION:
XS GIS Cut Line= 3
      2437511.09     13585432.11      2437511.09     13584546.64
      2437942.68     13583099.29
#Sta/Elev= 30
  4378.7  322.65  4437.8  321.72  4492.2  320.43    4810  306.58  4895.8  300.74
  4985.8  287.83  4995.8  283.31  5007.1  281.86  5015.8  281.91  5055.8   292.3
  5105.6  297.79  5145.8  299.61    5406  297.14  5659.9  297.48  6058.9  296.68
  6097.2  294.16  6163.3  286.66  6169.4  280.18  6176.2  278.43  6176.7  277.93
  6192.1  278.43  6194.6  282.16  6202.5   287.1  6221.6  288.38  6246.8  293.28
  6323.6  295.68  6411.9  302.77  6465.9  304.51  6725.9  305.71  6774.5  308.69
#Mann= 13 ,-1 , 0
  4378.7     .05       0  4437.8    .035       0  4492.2     .05       0
    4810     .07       0  5007.1     .12       0  5105.6     .07       0
    5406    .035       0  5659.9     .07       0  6097.2     .12       0
  6176.2     .05       0  6192.1     .12       0  6221.6    .035       0
  6323.6     .07       0
Bank Sta=6176.2,6192.1
XS Rating Curve= 0 ,0
Exp/Cntr=0.3,0.1

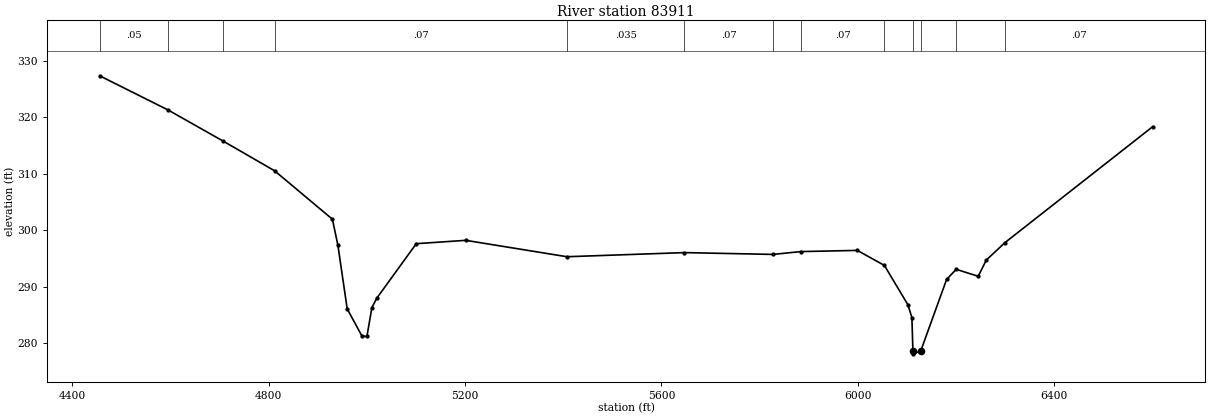
Type RM Length L Ch R = 1 ,83911   ,439,439,439
BEGIN DESCRIPTION:
CLEAR CREEK 93.0
END DESCRIPTION:
XS GIS Cut Line= 3
      2437938.53     13585366.67      2437868.74     13584677.49
      2438069.25      13583239.1
#Sta/Elev= 30
  4455.7  327.35    4595   321.3  4706.4  315.83  4812.1  310.53  4929.8  301.96
  4941.1  297.31  4959.9   286.1  4990.1  281.26  5000.1   281.2  5010.2  286.31
  5020.2  287.98  5100.6  297.63  5201.4  298.22  5407.5  295.32  5646.7  296.05
    5827  295.73  5883.7  296.23    5999  296.44  6054.1  293.78  6102.1   286.8
  6110.1  284.54  6112.2  278.63  6112.7  278.13  6128.1  278.63  6180.8   291.3
  6200.3  293.09  6245.2  291.86  6261.6  294.72  6299.4   297.8  6600.7  318.35
#Mann= 13 ,-1 , 0
  4455.7     .05       0    4595    .035       0  4706.4     .05       0
  4812.1     .07       0  5407.5    .035       0  5646.7     .07       0
    5827     .05       0  5883.7     .07       0  6054.1     .12       0
  6112.2     .05       0  6128.1     .12       0  6200.3    .035       0
  6299.4     .07       0
Bank Sta=6112.2,6128.1
XS Rating Curve= 0 ,0
Exp/Cntr=0.3,0.1