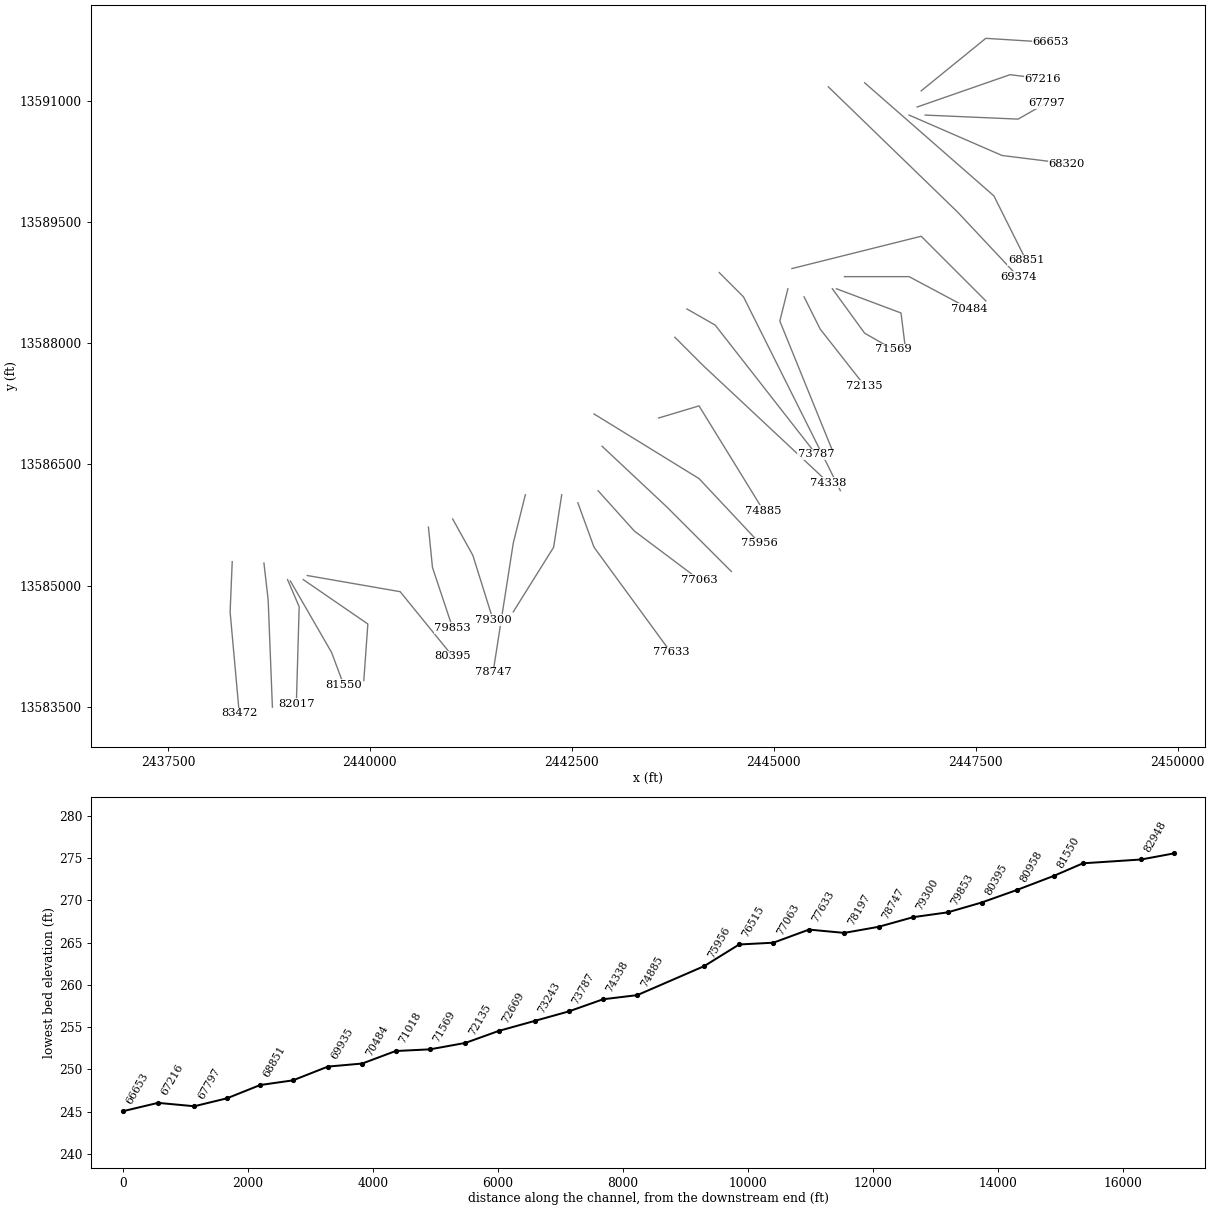
HEC-RAS study CLEAR CREEK.prj: CLEAR CREEK Base Level Engineering

--- CLEAR CREEK.g01 (geometry) --- (continued)

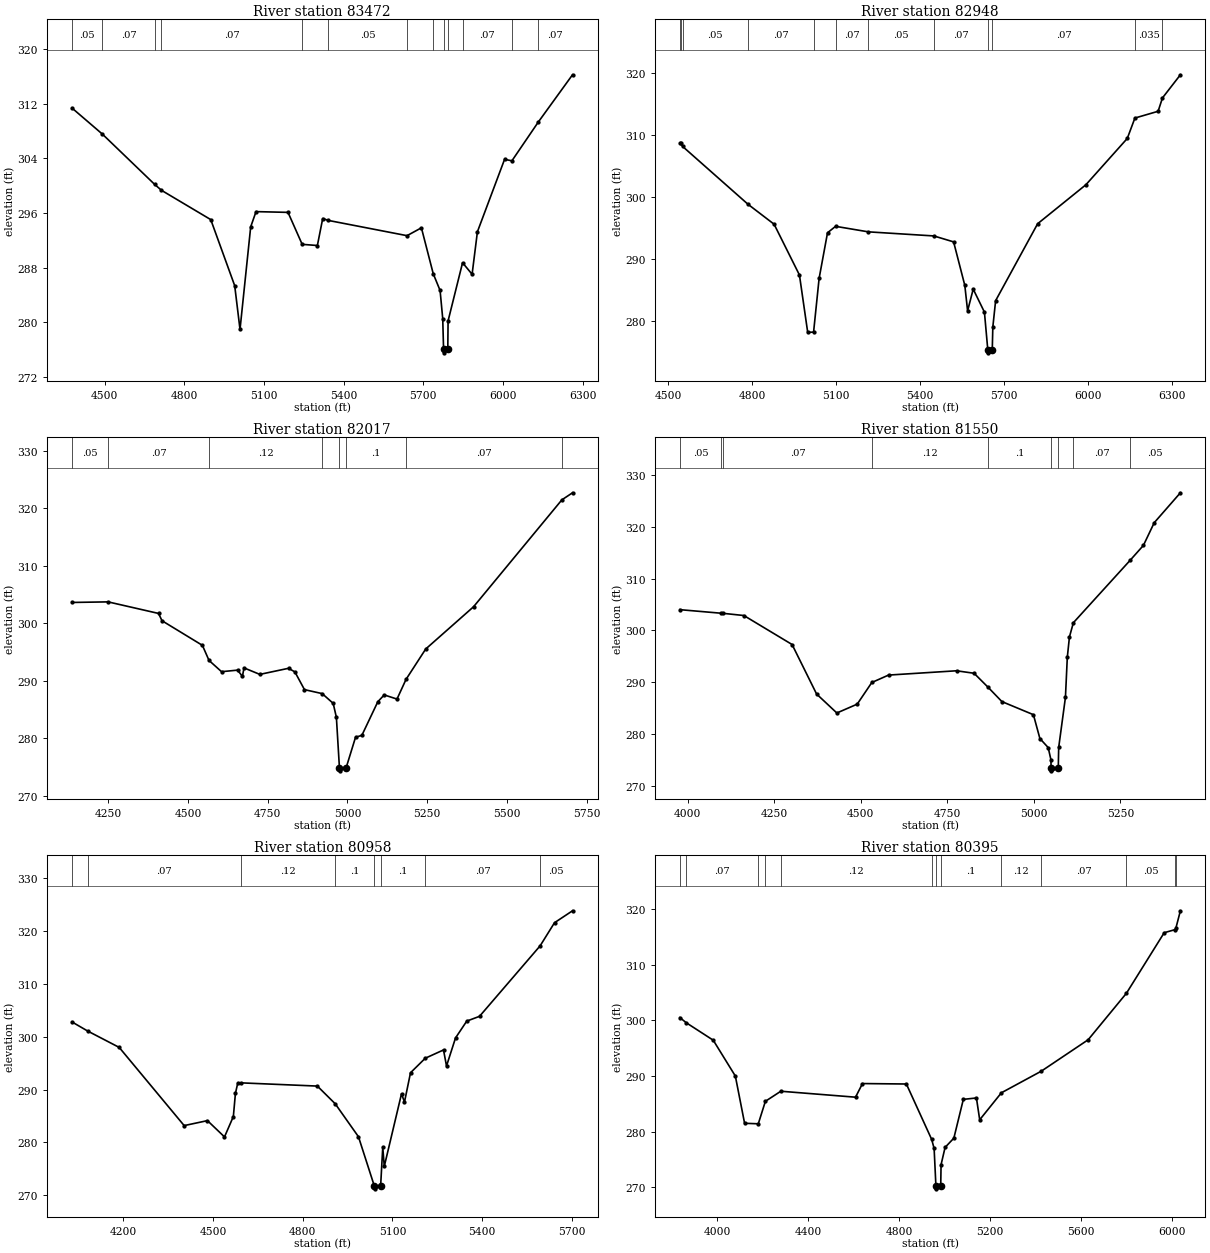
Type RM Length L Ch R = 1 ,83472   ,524,524,524
BEGIN DESCRIPTION:
CLEAR CREEK 92.0
END DESCRIPTION:
XS GIS Cut Line= 3
      2438296.19     13585296.83      2438270.02     13584673.13
      2438383.29     13583418.48
#Sta/Elev= 30
  4377.5  311.37    4492  307.55  4688.2  300.21  4714.3  299.33  4899.8  295.04
  4989.9  285.37  5009.9  278.97  5050.1  293.98  5070.2  296.21  5190.6   296.1
  5243.9  291.42  5301.1  291.25  5321.2   295.2  5342.6  294.92  5638.6  292.69
  5692.7  293.84  5737.3  287.11    5763  284.67    5773  280.53  5776.1  276.04
  5776.6  275.54    5792  276.04  5793.1  280.21  5847.6  288.73  5883.5  287.04
  5903.5  293.26  6005.7  303.86  6033.4  303.65  6132.1  309.29  6261.5  316.24
#Mann= 13 ,-1 , 0
  4377.5     .05       0    4492     .07       0  4688.2     .05       0
  4714.3     .07       0  5243.9    .035       0  5342.6     .05       0
  5638.6     .07       0  5737.3     .12       0  5776.1     .05       0
    5792     .12       0  5847.6     .07       0  6033.4    .035       0
  6132.1     .07       0
Bank Sta=5776.1,5792
XS Rating Curve= 0 ,0
Exp/Cntr=0.3,0.1

Type RM Length L Ch R = 1 ,82948   ,931,931,931
BEGIN DESCRIPTION:
CLEAR CREEK 91.0
END DESCRIPTION:
XS GIS Cut Line= 3
      2438688.74     13585279.38      2438741.08     13584821.43
      2438793.42      13583495.5
#Sta/Elev= 30
  4542.2  308.65  4544.7  308.65  4552.2  308.11  4785.8  298.78  4878.8  295.57
  4969.3  287.38  4998.8  278.13  5019.8  278.16  5039.6  286.84  5069.6  294.19
  5098.4  295.23  5215.3  294.34  5449.4  293.68    5520  292.72    5560  285.71
    5570  281.59    5590   285.1  5630.1  281.39  5642.1  275.32  5642.6  274.82
  5658.1  275.32  5660.1  278.99  5670.1  283.24  5820.2  295.65  5992.6  301.94
  6140.4  309.41  6167.6   312.7  6250.5  313.79  6266.1  315.95  6330.1  319.68
#Mann= 12 ,-1 , 0
  4542.2     .05       0  4544.7     .07       0  4552.2     .05       0
  4785.8     .07       0  5019.8     .12       0  5098.4     .07       0
  5215.3     .05       0  5449.4     .07       0  5642.1     .05       0
  5658.1     .07       0  6167.6    .035       0  6266.1     .07       0
Bank Sta=5642.1,5658.1
XS Rating Curve= 0 ,0
Exp/Cntr=0.3,0.1

Type RM Length L Ch R = 1 ,82017   ,467,467,467
BEGIN DESCRIPTION:
CLEAR CREEK 90.0
END DESCRIPTION:
XS GIS Cut Line= 3
      2438980.96     13585074.44      2439124.91     13584738.56
      2439090.01      13583534.7
#Sta/Elev= 30
  4136.1  303.65  4249.2  303.75  4407.5  301.74  4418.4  300.47  4545.1  296.19
  4565.8  293.57  4605.1  291.61  4655.2  291.88  4670.6   290.8  4675.6  292.27
  4725.2  291.14  4815.2   292.2  4835.2  291.57  4865.2  288.49  4920.7   287.8
  4955.3   286.1  4965.3  283.67  4974.9  274.87  4975.4  274.37  4995.7  274.87
  5025.3   280.2  5045.3  280.55  5095.3  286.39  5115.3  287.57  5155.4  286.85
  5183.7  290.27  5245.4  295.55  5395.5   302.9  5672.5  321.49  5705.9  322.72
#Mann= 8 ,-1 , 0
  4136.1     .05       0  4249.2     .07       0  4565.8     .12       0
  4920.7      .1       0  4974.9     .05       0  4995.7      .1       0
  5183.7     .07       0  5672.5    .035       0
Bank Sta=4974.9,4995.7
XS Rating Curve= 0 ,0
Exp/Cntr=0.3,0.1

Type RM Length L Ch R = 1 ,81550   ,592,592,592
BEGIN DESCRIPTION:
CLEAR CREEK 89.0
END DESCRIPTION:
XS GIS Cut Line= 3
      2439015.85       13585057.        2439525.       13584175.
        2439675.     13583775.01
#Sta/Elev= 30
  3977.4     304  4097.1  303.31  4102.6  303.29  4162.2  302.87  4301.5  297.27
  4372.3  287.71  4430.8  284.05  4489.6  285.76  4531.8  289.94  4580.1  291.37
  4776.4   292.2  4827.1  291.72  4867.8     289  4907.5  286.25  4998.5  283.72
  5017.2  279.12  5041.2  277.37  5049.2  274.98  5049.5  273.38    5050  272.88
  5070.3  273.38  5071.5  277.39    5091  287.07  5096.4  294.81  5102.6  298.75
  5113.9  301.48  5277.7  313.52  5316.2  316.41  5347.4  320.79    5423  326.57
#Mann= 9 ,-1 , 0
  3977.4     .05       0  4097.1    .035       0  4102.6     .07       0
  4531.8     .12       0  4867.8      .1       0  5049.5     .05       0
  5070.3      .1       0  5113.9     .07       0  5277.7     .05       0
Bank Sta=5049.5,5070.3
XS Rating Curve= 0 ,0
Exp/Cntr=0.3,0.1

Type RM Length L Ch R = 1 ,80958   ,563,563,563
BEGIN DESCRIPTION:
CLEAR CREEK 88.0
END DESCRIPTION:
XS GIS Cut Line= 3
      2439175.03     13585074.98        2439975.       13584525.
        2439925.     13583824.97
#Sta/Elev= 30
  4029.2   302.8  4081.2  301.09  4186.9  297.98    4404  283.18  4481.8  284.12
  4538.8  281.04  4568.4   284.9  4575.3  289.28  4583.3  291.27  4593.8  291.27
  4849.1  290.66  4908.8  287.31  4986.5  281.07  5039.7  271.71  5040.2  271.21
  5060.5  271.71  5067.7   279.1  5072.7  275.45  5130.3  289.19  5140.3  287.65
  5160.4  293.18  5209.7  295.93  5270.7   297.5  5280.7  294.46  5310.8  299.77
  5348.4  302.96    5391  303.86  5593.5   317.2  5641.6  321.58  5701.8  323.84
#Mann= 8 ,-1 , 0
  4029.2    .035       0  4081.2     .07       0  4593.8     .12       0
  4908.8      .1       0  5039.7     .05       0  5060.5      .1       0
  5209.7     .07       0  5593.5     .05       0
Bank Sta=5039.7,5060.5
XS Rating Curve= 0 ,0
Exp/Cntr=0.3,0.1

Type RM Length L Ch R = 1 ,80395   ,542,542,542
BEGIN DESCRIPTION:
CLEAR CREEK 87.0
END DESCRIPTION:
XS GIS Cut Line= 3
        2439225.       13585125.        2440375.       13584925.
      2441024.98     13584125.03
#Sta/Elev= 30
  3837.2  300.51  3865.5  299.57  3983.7  296.44  4080.8     290  4121.4  281.51
  4181.6  281.42  4212.7  285.46  4280.5  287.27  4608.6   286.2  4639.1  288.65
  4831.9  288.57  4942.9  278.62  4953.7  276.99  4961.6  270.23  4962.1  269.73
  4982.7  270.23  4984.2  274.07  5001.9  277.18  5040.4  278.84    5082  285.81
  5139.5  286.06  5153.9  282.14  5249.1  286.99  5424.2  290.87  5630.1  296.52
  5798.1  304.87  5964.1  315.76  6013.4  316.33  6015.1  316.53  6035.2   319.7
#Mann= 13 ,-1 , 0
  3837.2    .035       0  3865.5     .07       0  4181.6      .1       0
  4212.7     .07       0  4280.5     .12       0  4942.9      .1       0
  4961.6     .05       0  4982.7      .1       0  5249.1     .12       0
  5424.2     .07       0  5798.1     .05       0  6013.4     .07       0
  6015.1     .05       0
Bank Sta=4961.6,4982.7
XS Rating Curve= 0 ,0
Exp/Cntr=0.3,0.1

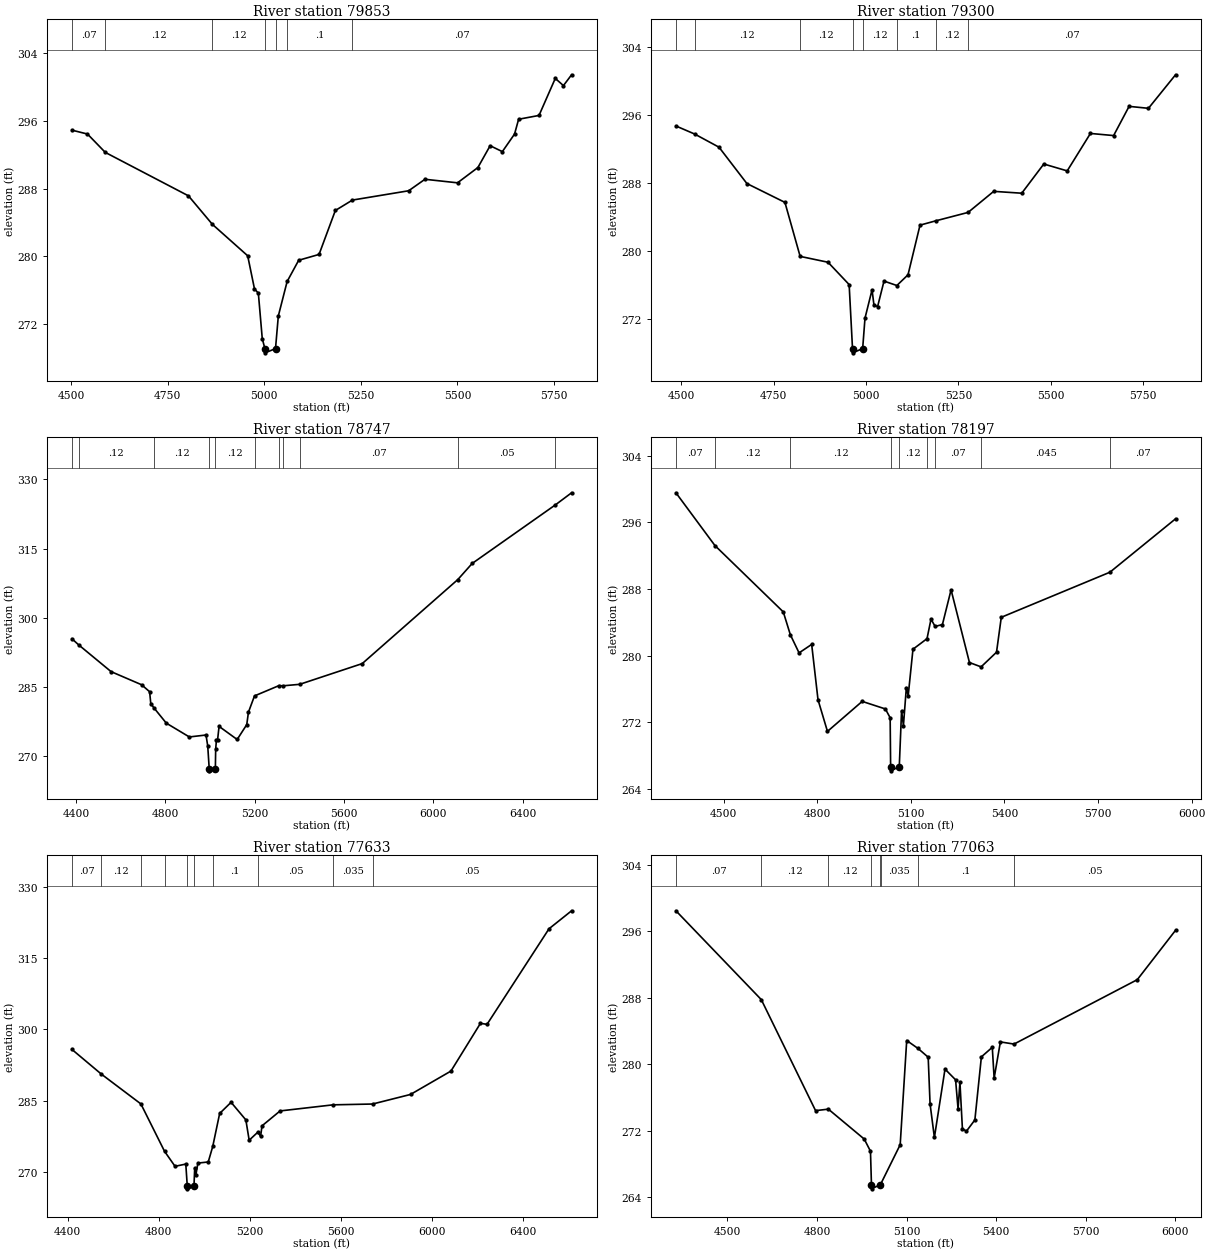
Type RM Length L Ch R = 1 ,79853   ,553,553,553
BEGIN DESCRIPTION:
CLEAR CREEK 86.0
END DESCRIPTION:
XS GIS Cut Line= 3
        2440725.     13585725.02        2440775.       13585225.
      2441025.01     13584474.98
#Sta/Elev= 30
  4502.3  294.91  4542.5  294.45  4588.5  292.28  4803.8  287.14  4865.7  283.77
  4957.1  280.05  4974.7  276.13  4984.7  275.63  4994.8  270.26  5001.6  269.07
  5002.1  268.57  5029.1  269.07  5036.4  272.93  5059.2  277.01  5089.1  279.52
  5141.8  280.21    5184  285.41  5228.2  286.64  5373.7  287.74  5415.9   289.1
  5500.2  288.68  5552.9  290.49  5584.6  293.07  5616.2  292.37  5647.8  294.45
  5658.3   296.2  5711.1  296.65  5753.2  301.03  5774.3  300.18  5795.4  301.46
#Mann= 7 ,-1 , 0
  4502.3     .07       0  4588.5     .12       0  4865.7     .12       0
  5001.6     .05       0  5029.1     .12       0  5059.2      .1       0
  5228.2     .07       0
Bank Sta=5001.6,5029.1
XS Rating Curve= 0 ,0
Exp/Cntr=0.3,0.1

Type RM Length L Ch R = 1 ,79300   ,553,553,553
BEGIN DESCRIPTION:
CLEAR CREEK 85.0
END DESCRIPTION:
XS GIS Cut Line= 3
      2441024.98     13585825.03        2441275.       13585375.
      2441525.01     13584574.97
#Sta/Elev= 30
  4485.1  294.72  4535.9  293.77  4601.8  292.22  4677.3  287.94  4780.3  285.72
  4821.5  279.36    4897  278.67  4954.2  276.04  4963.3   268.5  4963.8     268
  4990.8   268.5  4997.1  272.08  5016.2  275.42  5021.4  273.62  5031.3  273.45
  5048.6  276.45  5083.4  275.93  5113.6  277.19  5146.1  283.04  5188.1  283.54
  5276.3  284.54  5345.7  287.02  5421.6   286.8  5481.3  290.24  5544.7  289.43
  5607.6  293.84  5670.4  293.59  5712.3  297.03  5764.7   296.8  5838.1  300.75
#Mann= 8 ,-1 , 0
  4485.1     .07       0  4535.9     .12       0  4821.5     .12       0
  4963.3     .05       0  4990.8     .12       0  5083.4      .1       0
  5188.1     .12       0  5276.3     .07       0
Bank Sta=4963.3,4990.8
XS Rating Curve= 0 ,0
Exp/Cntr=0.3,0.1

Type RM Length L Ch R = 1 ,78747   ,550,550,550
BEGIN DESCRIPTION:
CLEAR CREEK 84.0
END DESCRIPTION:
XS GIS Cut Line= 3
      2441924.99     13586124.96        2441775.       13585525.
      2441525.01     13583925.04
#Sta/Elev= 30
    4382  295.46  4412.2  294.14  4557.2  288.35  4693.8  285.51  4729.8     284
    4735  281.44  4748.3  280.55  4804.6  277.19  4907.7   274.2  4982.4  274.62
  4990.1  272.25  4996.7  267.36  4997.2  266.86  5024.3  267.36  5025.7  271.58
  5029.3  273.62  5034.3   273.6  5040.9  276.49  5121.9  273.65  5164.9  276.87
  5172.5  279.57  5199.6  283.09  5308.7  285.31  5328.1  285.28  5402.1   285.6
  5682.1  290.09  6110.2  308.29  6174.5  311.78  6547.6  324.48  6619.8  327.09
#Mann= 11 ,-1 , 0
    4382     .07       0  4412.2     .12       0  4748.3     .12       0
  4996.7     .05       0  5024.3     .12       0  5199.6      .1       0
  5308.7    .045       0  5328.1     .12       0  5402.1     .07       0
  6110.2     .05       0  6547.6     .07       0
Bank Sta=4996.7,5024.3
XS Rating Curve= 0 ,0
Exp/Cntr=0.3,0.1

Type RM Length L Ch R = 1 ,78197   ,564,564,564
BEGIN DESCRIPTION:
CLEAR CREEK 83.0
END DESCRIPTION:
XS GIS Cut Line= 3
        2442375.     13586124.97        2442275.       13585475.
      2441775.01     13584675.02
#Sta/Elev= 30
  4347.4  299.57  4472.3  293.23  4691.4  285.25  4714.1   282.5    4742  280.32
  4782.4  281.34  4802.7  274.69    4833  270.88  4944.3  274.49  5018.6  273.58
  5033.9  272.52  5035.4  266.64  5035.9  266.14  5063.1  266.64  5070.5  273.38
  5076.4  271.58  5085.8  276.15  5091.7  275.18    5107  280.76    5152  282.03
  5164.8  284.38    5178   283.5  5201.4  283.73  5229.1   287.9    5288  279.16
  5325.3  278.64  5374.7   280.4    5390   284.6  5738.1  290.02  5948.4  296.44
#Mann= 9 ,-1 , 0
  4347.4     .07       0  4472.3     .12       0  4714.1     .12       0
  5035.4     .05       0  5063.1     .12       0    5152      .1       0
    5178     .07       0  5325.3    .045       0  5738.1     .07       0
Bank Sta=5035.4,5063.1
XS Rating Curve= 0 ,0
Exp/Cntr=0.3,0.1

Type RM Length L Ch R = 1 ,77633   ,570,570,570
BEGIN DESCRIPTION:
CLEAR CREEK 82.0
END DESCRIPTION:
XS GIS Cut Line= 3
      2442574.98     13586025.04        2442775.       13585475.
        2443725.       13584175.
#Sta/Elev= 30
  4418.3   295.8  4547.7  290.61  4721.2  284.36    4825  274.42  4871.2  271.26
  4918.5  271.73  4925.1  267.03  4925.6  266.53  4954.4  267.03  4957.7  270.94
    4963   269.5  4971.7  271.94  5017.1  272.17  5036.9  275.43  5067.3  282.36
  5117.5   284.7  5182.4  281.01    5197  276.74  5234.8  278.42  5247.2  277.56
  5253.4  279.76  5332.9  282.89  5565.7  284.17  5739.2  284.34  5905.9  286.35
  6083.6  291.26  6213.3  301.29  6242.1  301.07  6514.5  321.14  6613.7  324.92
#Mann= 10 ,-1 , 0
  4418.3     .07       0  4547.7     .12       0  4721.2      .1       0
    4825     .12       0  4925.1     .05       0  4954.4     .12       0
  5036.9      .1       0  5234.8     .05       0  5565.7    .035       0
  5739.2     .05       0
Bank Sta=4925.1,4954.4
XS Rating Curve= 0 ,0
Exp/Cntr=0.3,0.1

Type RM Length L Ch R = 1 ,77063   ,548,548,548
BEGIN DESCRIPTION:
CLEAR CREEK 81.0
END DESCRIPTION:
XS GIS Cut Line= 3
      2442825.03     13586174.97        2443275.       13585675.
      2444074.97     13585075.02
#Sta/Elev= 30
  4327.9  298.44  4613.7  287.75  4795.4  274.39  4838.2  274.57  4958.3  270.97
  4979.2  269.51  4982.5  265.48    4983  264.98  5011.8  265.48  5012.9  265.51
  5078.7  270.29  5100.5  282.83  5138.5  281.87  5172.4  280.82  5178.7   275.2
  5193.2  271.16  5228.7  279.39  5264.1   278.1  5272.4  274.61  5278.7   277.8
    5287   272.2  5300.5  271.92  5328.7  273.27  5350.5  280.86    5387  282.01
  5393.2   278.3  5414.1  282.66  5459.8   282.4  5872.4  290.15  6000.5  296.09
#Mann= 8 ,-1 , 0
  4327.9     .07       0  4613.7     .12       0  4838.2     .12       0
  4982.5     .05       0  5011.8     .12       0  5012.9    .035       0
  5138.5      .1       0  5459.8     .05       0
Bank Sta=4982.5,5011.8
XS Rating Curve= 0 ,0
Exp/Cntr=0.3,0.1

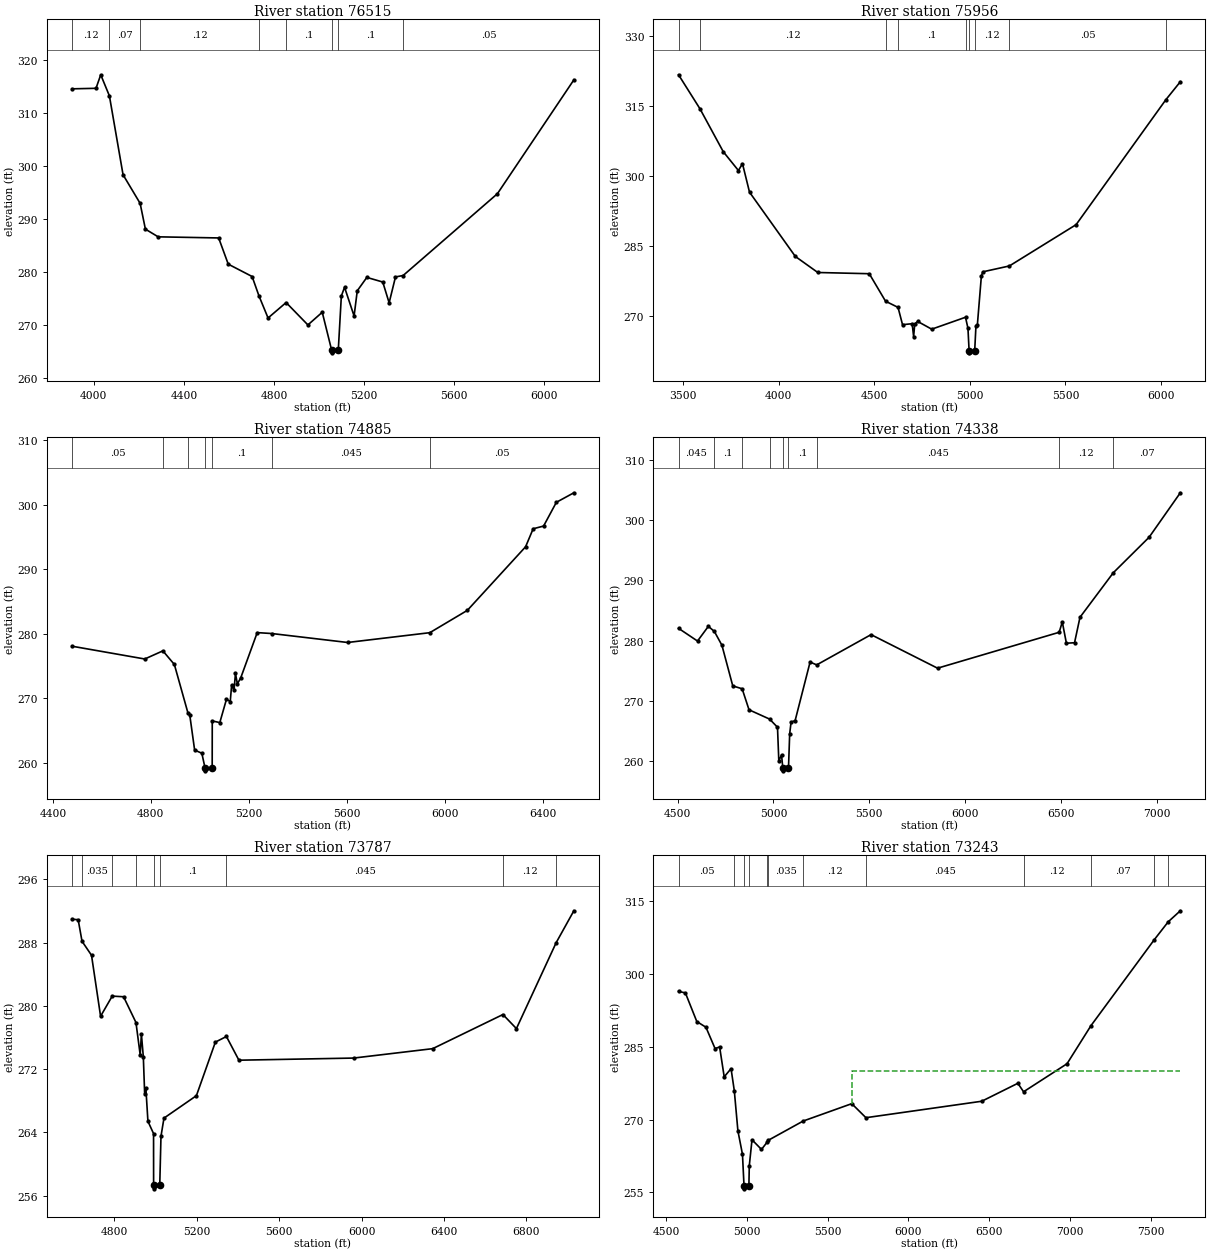
Type RM Length L Ch R = 1 ,76515   ,559,559,559
BEGIN DESCRIPTION:
CLEAR CREEK 80.0
END DESCRIPTION:
XS GIS Cut Line= 3
      2442874.97     13586725.03        2443675.       13585975.
        2444475.       13585175.
#Sta/Elev= 30
  3903.6  314.54  4009.9  314.64  4030.9  317.19  4069.4  313.21    4130  298.34
  4205.8  292.95  4229.2  288.09  4285.8  286.64  4554.5  286.43    4597  281.49
    4703  279.16  4733.4  275.51  4773.8  271.34    4854  274.25  4950.7  270.03
  5014.4  272.42  5056.2  265.27  5056.7  264.77  5085.6  265.27  5099.2  275.48
  5113.4  277.13  5155.8  271.72  5169.9  276.47  5212.4  278.99  5283.1  278.12
  5311.4   274.2  5339.6  279.08  5373.6  279.35  5792.2  294.77  6131.6  316.23
#Mann= 8 ,-1 , 0
  3903.6     .12       0  4069.4     .07       0  4205.8     .12       0
  4733.4    .035       0    4854      .1       0  5056.2     .05       0
  5085.6      .1       0  5373.6     .05       0
Bank Sta=5056.2,5085.6
XS Rating Curve= 0 ,0
Exp/Cntr=0.3,0.1

Type RM Length L Ch R = 1 ,75956   ,1071,1071,1071
BEGIN DESCRIPTION:
CLEAR CREEK 79.0
END DESCRIPTION:
XS GIS Cut Line= 3
      2442774.98     13587125.01        2444075.       13586325.
      2444824.97     13585525.03
#Sta/Elev= 30
  3477.4  321.67  3589.4   314.4  3711.2  305.22  3790.4   301.2  3811.7  302.66
  3848.4  296.57    4088  282.82  4205.4  279.39  4474.4  279.13  4559.5  273.25
  4624.8  271.93  4648.3  268.23  4698.6  268.44  4706.3  265.69  4712.2  268.39
  4727.6  268.92  4800.9  267.27  4977.5  269.82  4990.3  267.45  4996.2  262.71
  4996.7  262.21  5025.6  262.71    5032  267.91  5039.3   268.1  5060.3  278.57
  5067.6  279.53  5206.9  280.79  5555.6  289.62    6025  316.35  6100.4  320.18
#Mann= 9 ,-1 , 0
  3477.4     .07       0  3589.4     .12       0  4559.5    .035       0
  4624.8      .1       0  4977.5     .12       0  4996.2     .05       0
  5025.6     .12       0  5206.9     .05       0    6025     .07       0
Bank Sta=4996.2,5025.6
XS Rating Curve= 0 ,0
Exp/Cntr=0.3,0.1

Type RM Length L Ch R = 1 ,74885   ,547,547,547
BEGIN DESCRIPTION:
CLEAR CREEK 78.0
END DESCRIPTION:
XS GIS Cut Line= 3
        2443575.       13587075.        2444075.       13587225.
      2444874.97     13585925.04
#Sta/Elev= 30
  4478.4   278.1  4775.1  276.12  4849.1  277.38    4896  275.27    4951  267.81
  4958.7  267.48  4978.7     262  5008.1  261.51  5020.9  259.28  5021.4  258.78
  5050.4  259.28  5050.7  266.52  5081.5  266.26  5108.7  269.88  5124.1  269.52
  5129.9  272.12  5139.5  271.24  5145.4  273.88  5153.1  272.27  5166.6  273.16
  5234.2  280.21  5293.2  280.07  5603.3  278.68  5938.8   280.2    6092  283.66
  6329.8  293.52  6360.6  296.31  6403.2  296.73  6455.3  300.41  6526.8  301.89
#Mann= 7 ,-1 , 0
  4478.4     .05       0  4849.1    .035       0    4951      .1       0
  5020.9     .05       0  5050.4      .1       0  5293.2    .045       0
  5938.8     .05       0
Bank Sta=5020.9,5050.4
XS Rating Curve= 0 ,0
Exp/Cntr=0.3,0.1

Type RM Length L Ch R = 1 ,74338   ,551,551,551
BEGIN DESCRIPTION:
CLEAR CREEK 77.0
END DESCRIPTION:
XS GIS Cut Line= 3
      2443774.99     13588075.01        2444125.       13587725.
        2445675.       13586275.
#Sta/Elev= 30
  4505.1  282.03  4604.1  279.91  4660.7  282.36    4692  281.51  4731.4  279.21
    4788  272.44  4836.9  271.96  4872.8  268.46  4980.1  266.91  5021.3  265.55
  5028.2  259.95  5042.4  260.93  5048.9  258.79  5049.4  258.29  5078.7  258.79
  5084.9  264.48  5092.2  266.41  5113.2  266.65  5191.3  276.41  5225.9  275.94
  5509.4  280.98  5856.2  275.39  6490.6  281.37  6506.9   283.1  6528.3  279.55
  6570.8  279.63  6599.2  283.87    6773  291.29  6959.7   297.2  7122.6  304.61
#Mann= 9 ,-1 , 0
  4505.1    .045       0    4692      .1       0  4836.9    .035       0
  4980.1      .1       0  5048.9     .05       0  5078.7      .1       0
  5225.9    .045       0  6490.6     .12       0    6773     .07       0
Bank Sta=5048.9,5078.7
XS Rating Curve= 0 ,0
Exp/Cntr=0.3,0.1

Type RM Length L Ch R = 1 ,73787   ,544,544,544
BEGIN DESCRIPTION:
CLEAR CREEK 76.0
END DESCRIPTION:
XS GIS Cut Line= 3
      2443924.96     13588425.02        2444275.       13588225.
      2445525.03     13586624.97
#Sta/Elev= 30
  4596.3  290.97  4625.9  290.91  4644.6  288.18  4690.6  286.41  4734.6  278.69
    4791  281.24  4846.1  281.16  4906.2   277.9  4926.8  273.78  4932.5  276.45
  4941.9  273.55  4948.4  268.86  4954.1  269.63  4964.2   265.4  4991.5  263.84
  4991.8  257.35  4992.3  256.85  5021.6  257.35  5027.5   263.5    5042   265.8
  5199.3  268.64  5291.3  275.42  5344.9  276.13  5405.5  273.13  5961.7   273.4
  6345.2  274.59  6685.9  278.91  6751.3  277.13    6944     288  7029.9  292.04
#Mann= 9 ,-1 , 0
  4596.3    .045       0  4644.6    .035       0    4791     .05       0
  4906.2      .1       0  4991.8     .05       0  5021.6      .1       0
  5344.9    .045       0  6685.9     .12       0    6944     .07       0
Bank Sta=4991.8,5021.6
XS Rating Curve= 0 ,0
Exp/Cntr=0.3,0.1

Type RM Length L Ch R = 1 ,73243   ,574,574,574
BEGIN DESCRIPTION:
CLEAR CREEK 75.0
END DESCRIPTION:
XS GIS Cut Line= 3
      2444325.02     13588874.98        2444625.       13588575.
      2445824.99     13586175.01
#Sta/Elev= 30
  4576.4  296.41  4618.8  296.11  4689.5  290.21  4746.1  289.03  4802.6  284.64
  4830.9  284.97  4859.2  278.81  4901.6   280.5  4921.8  275.94  4944.1  267.67
  4972.3  262.86  4982.1  256.23  4982.6  255.73    5012  256.23  5014.6   260.5
  5031.4  265.84  5090.1  263.85  5124.3  265.32  5130.9  265.71  5348.2   269.7
  5649.1  273.28  5736.9  270.39  6454.1  273.78  6677.7  277.48  6713.1  275.73
  6982.3  281.51  7130.6  289.36  7521.9  307.04  7609.2  310.77  7683.9  313.03
#Mann= 12 ,-1 , 0
  4576.4     .05       0  4921.8    .035       0  4982.1    .035       0
    5012    .035       0  5124.3     .12       0  5130.9    .035       0
  5348.2     .12       0  5736.9    .045       0  6713.1     .12       0
  7130.6     .07       0  7521.9     .12       0  7609.2     .07       0
#XS Ineff= 2 , 0
       0                    5650       0     280
Permanent Ineff=
       F       F
Bank Sta=4982.1,5012
XS Rating Curve= 0 ,0
Exp/Cntr=0.3,0.1

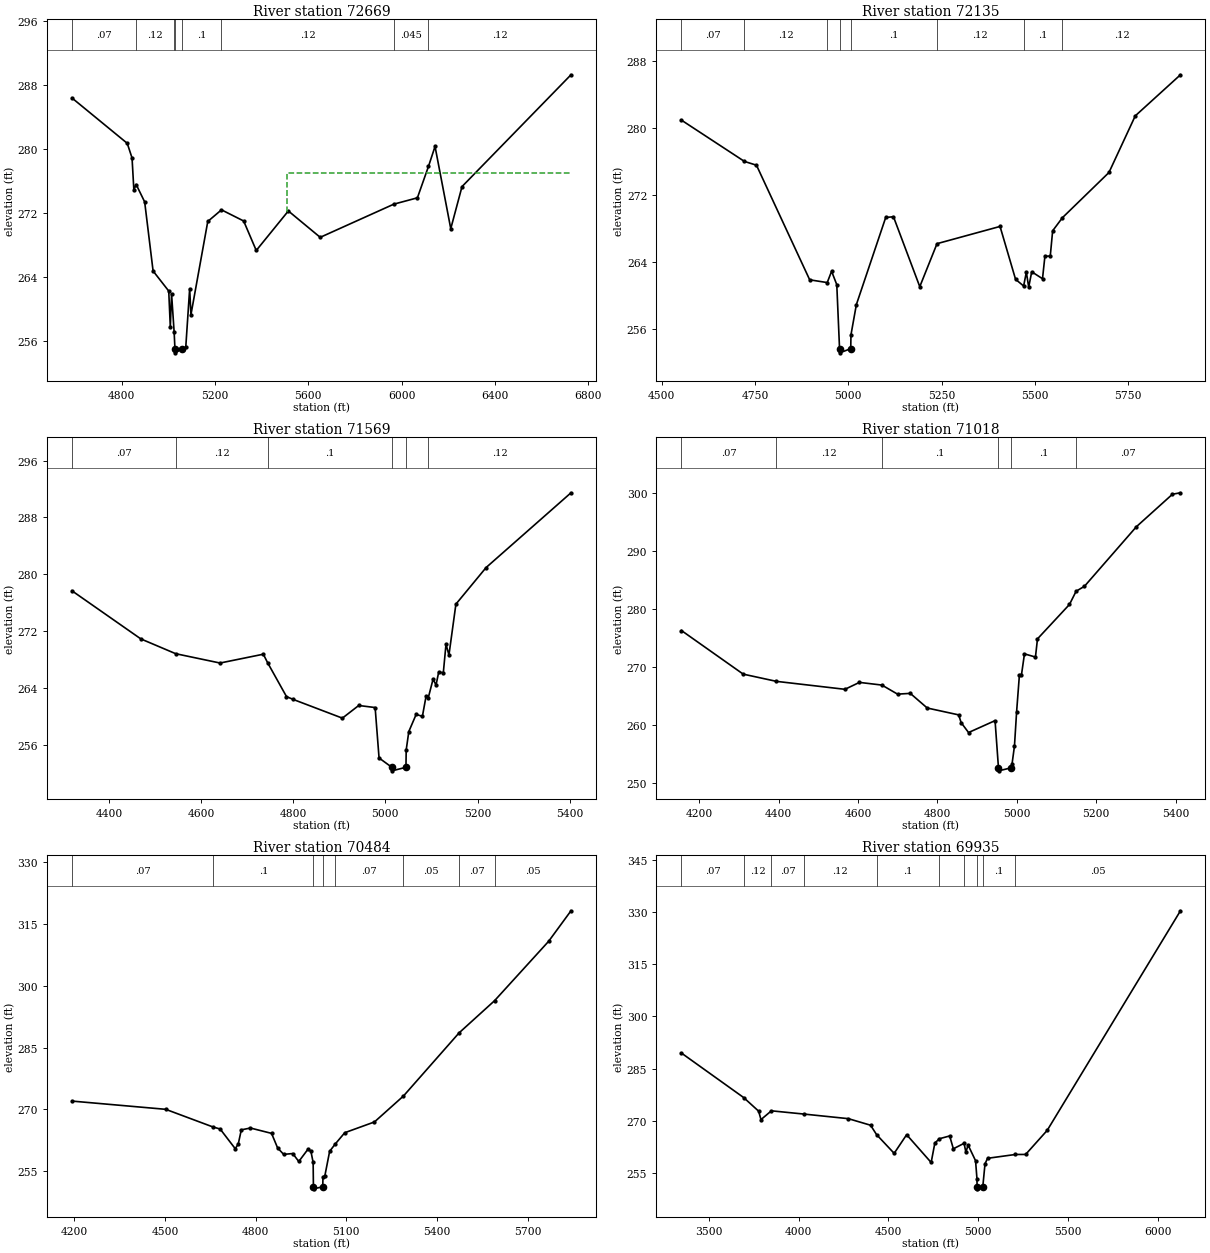
Type RM Length L Ch R = 1 ,72669   ,534,534,534
BEGIN DESCRIPTION:
CLEAR CREEK 74.0
END DESCRIPTION:
XS GIS Cut Line= 3
      2445175.01     13588675.02        2445075.       13588275.
      2445724.99     13586675.02
#Sta/Elev= 30
    4587  286.35  4824.1  280.69  4844.7  278.86  4852.4   274.9  4862.4  275.55
  4898.8  273.38  4934.9  264.76    5002  262.26  5008.7   257.8  5014.1   261.9
  5025.2  257.11  5028.6  255.05  5029.1  254.55  5058.5  255.05  5074.9  255.22
  5091.7  262.56  5097.1   259.3  5169.3  270.94  5228.1  272.39  5323.1     271
  5377.1  267.32  5514.7  272.25  5651.3  268.96    5967   273.1  6067.9  273.89
  6115.4  277.81  6143.5   280.3  6210.9  270.04  6259.1  275.29  6726.3  289.24
#Mann= 8 ,-1 , 0
    4587     .07       0  4862.4     .12       0  5025.2      .1       0
  5028.6     .05       0  5058.5      .1       0  5228.1     .12       0
    5967    .045       0  6115.4     .12       0
#XS Ineff= 2 , 0
       0                    5510       0     277
Permanent Ineff=
       F       F
Bank Sta=5028.6,5058.5
XS Rating Curve= 0 ,0
Exp/Cntr=0.3,0.1

Type RM Length L Ch R = 1 ,72135   ,566,566,566
BEGIN DESCRIPTION:
CLEAR CREEK 73.0
END DESCRIPTION:
XS GIS Cut Line= 3
      2445375.01     13588574.97        2445575.       13588175.
      2446124.99     13587475.01
#Sta/Elev= 30
  4552.9  280.95  4721.9  276.01  4754.1  275.56  4896.7  261.86  4943.7  261.53
  4955.4  262.88  4969.3  261.28  4976.7  253.63  4977.2  253.13  5006.7  253.63
  5007.3  255.28  5021.8   258.9  5100.4  269.31  5121.2   269.4  5191.7  261.04
  5237.9  266.18  5406.8  268.24  5448.4  261.92    5470  261.12  5477.3  262.77
  5483.6  260.98  5491.7  262.82  5520.6  261.99    5527  264.66  5541.4  264.71
  5547.8  267.72  5574.1  269.29  5698.7  274.69  5769.2  281.46  5890.3  286.37
#Mann= 8 ,-1 , 0
  4552.9     .07       0  4721.9     .12       0  4943.7      .1       0
  4976.7     .05       0  5006.7      .1       0  5237.9     .12       0
    5470      .1       0  5574.1     .12       0
Bank Sta=4976.7,5006.7
XS Rating Curve= 0 ,0
Exp/Cntr=0.3,0.1

Type RM Length L Ch R = 1 ,71569   ,551,551,551
BEGIN DESCRIPTION:
CLEAR CREEK 72.0
END DESCRIPTION:
XS GIS Cut Line= 3
      2445724.97     13588675.04        2446125.       13588125.
      2446474.97     13587925.02
#Sta/Elev= 30
  4319.7  277.69  4469.3  270.92    4545  268.84  4641.2  267.53  4735.1  268.77
  4744.7  267.54  4785.4  262.81    4800  262.41  4906.7  259.78  4942.2  261.56
  4977.8  261.27  4986.3  254.18    5014  252.87  5014.5  252.37  5044.7  252.87
  5045.2   255.3  5050.9   257.9  5066.8   260.3  5080.4  260.04  5088.4  262.89
  5093.3  262.68  5103.5  265.25    5110  264.44  5115.7  266.24  5125.8  266.18
  5131.6  270.17    5138  268.66  5153.1  275.81  5218.7  280.96  5402.9  291.47
#Mann= 6 ,-1 , 0
  4319.7     .07       0    4545     .12       0  4744.7      .1       0
    5014     .05       0  5044.7      .1       0  5093.3     .12       0
Bank Sta=5014,5044.7
XS Rating Curve= 0 ,0
Exp/Cntr=0.3,0.1

Type RM Length L Ch R = 1 ,71018   ,534,534,534
BEGIN DESCRIPTION:
CLEAR CREEK 71.0
END DESCRIPTION:
XS GIS Cut Line= 3
      2445774.95     13588675.02        2446575.       13588375.
        2446625.     13587974.96
#Sta/Elev= 30
  4154.8  276.32  4310.6  268.81  4394.1  267.57  4566.9   266.2  4603.4  267.39
    4660  266.93  4699.5  265.37  4731.6   265.5  4774.3  262.98  4853.5   261.8
  4859.7  260.47  4878.4  258.76  4945.2  260.81  4953.8  252.67  4954.3  252.17
  4984.5  252.67  4987.9   253.3  4994.1  256.44  4999.5  262.33  5006.6  268.71
  5011.8  268.71  5019.3   272.3    5047  271.75  5052.1  274.88  5132.7   280.8
  5149.5  283.08  5170.5  283.93  5301.5  294.19  5392.2  299.77  5412.4  300.02
#Mann= 6 ,-1 , 0
  4154.8     .07       0  4394.1     .12       0    4660      .1       0
  4953.8     .05       0  4984.5      .1       0  5149.5     .07       0
Bank Sta=4953.8,4984.5
XS Rating Curve= 0 ,0
Exp/Cntr=0.3,0.1

Type RM Length L Ch R = 1 ,70484   ,549,549,549
BEGIN DESCRIPTION:
CLEAR CREEK 70.0
END DESCRIPTION:
XS GIS Cut Line= 3
      2445875.02       13588825.        2446675.       13588825.
      2447425.02     13588424.99
#Sta/Elev= 30
  4192.7     272  4502.7     270  4659.9  265.69  4682.7  265.22  4732.7  260.43
  4742.7  261.61  4752.7  265.01  4782.7  265.46  4852.7  264.16  4872.7  260.62
  4892.7  259.06  4922.7  259.26  4942.7  257.33  4972.7  260.27  4982.7  259.85
  4990.2   257.1  4991.1  251.19  4991.6  250.69  5021.8  251.19  5022.8  253.64
  5028.5  253.69  5044.7  259.79  5062.5  261.51  5094.7  264.32  5192.8  266.93
  5288.9  273.24  5472.8  288.57  5589.9  296.37  5768.7  310.79  5842.7  318.21
#Mann= 8 ,-1 , 0
  4192.7     .07       0  4659.9      .1       0  4991.1     .05       0
  5021.8      .1       0  5062.5     .07       0  5288.9     .05       0
  5472.8     .07       0  5589.9     .05       0
Bank Sta=4991.1,5021.8
XS Rating Curve= 0 ,0
Exp/Cntr=0.3,0.1

Type RM Length L Ch R = 1 ,69935   ,561,561,561
BEGIN DESCRIPTION:
CLEAR CREEK 69.0
END DESCRIPTION:
XS GIS Cut Line= 3
      2445224.96     13588924.99        2446825.       13589325.
      2447625.03     13588524.97
#Sta/Elev= 30
  3346.1  289.46    3693  276.63  3776.5  272.71  3789.4  270.28  3847.6  272.81
  4029.6  271.87  4276.4  270.55  4400.1  268.66  4433.6  265.95  4531.5  260.56
  4601.1  265.93  4737.7  257.92  4758.3  263.53  4783.8  264.77  4840.8  265.57
  4861.4  261.87  4921.2  263.45    4931  260.93  4943.8  262.92  4985.1  258.43
  4992.8   253.3  4993.8  250.83  4994.3  250.33  5025.2  250.83  5037.8  257.54
    5052  259.13  5207.1  260.23  5264.1  260.24  5384.3  267.18  6126.8  330.45
#Mann= 10 ,-1 , 0
  3346.1     .07       0    3693     .12       0  3847.6     .07       0
  4029.6     .12       0  4433.6      .1       0  4783.8     .12       0
  4921.2      .1       0  4993.8     .05       0  5025.2      .1       0
  5207.1     .05       0
Bank Sta=4993.8,5025.2
XS Rating Curve= 0 ,0
Exp/Cntr=0.3,0.1

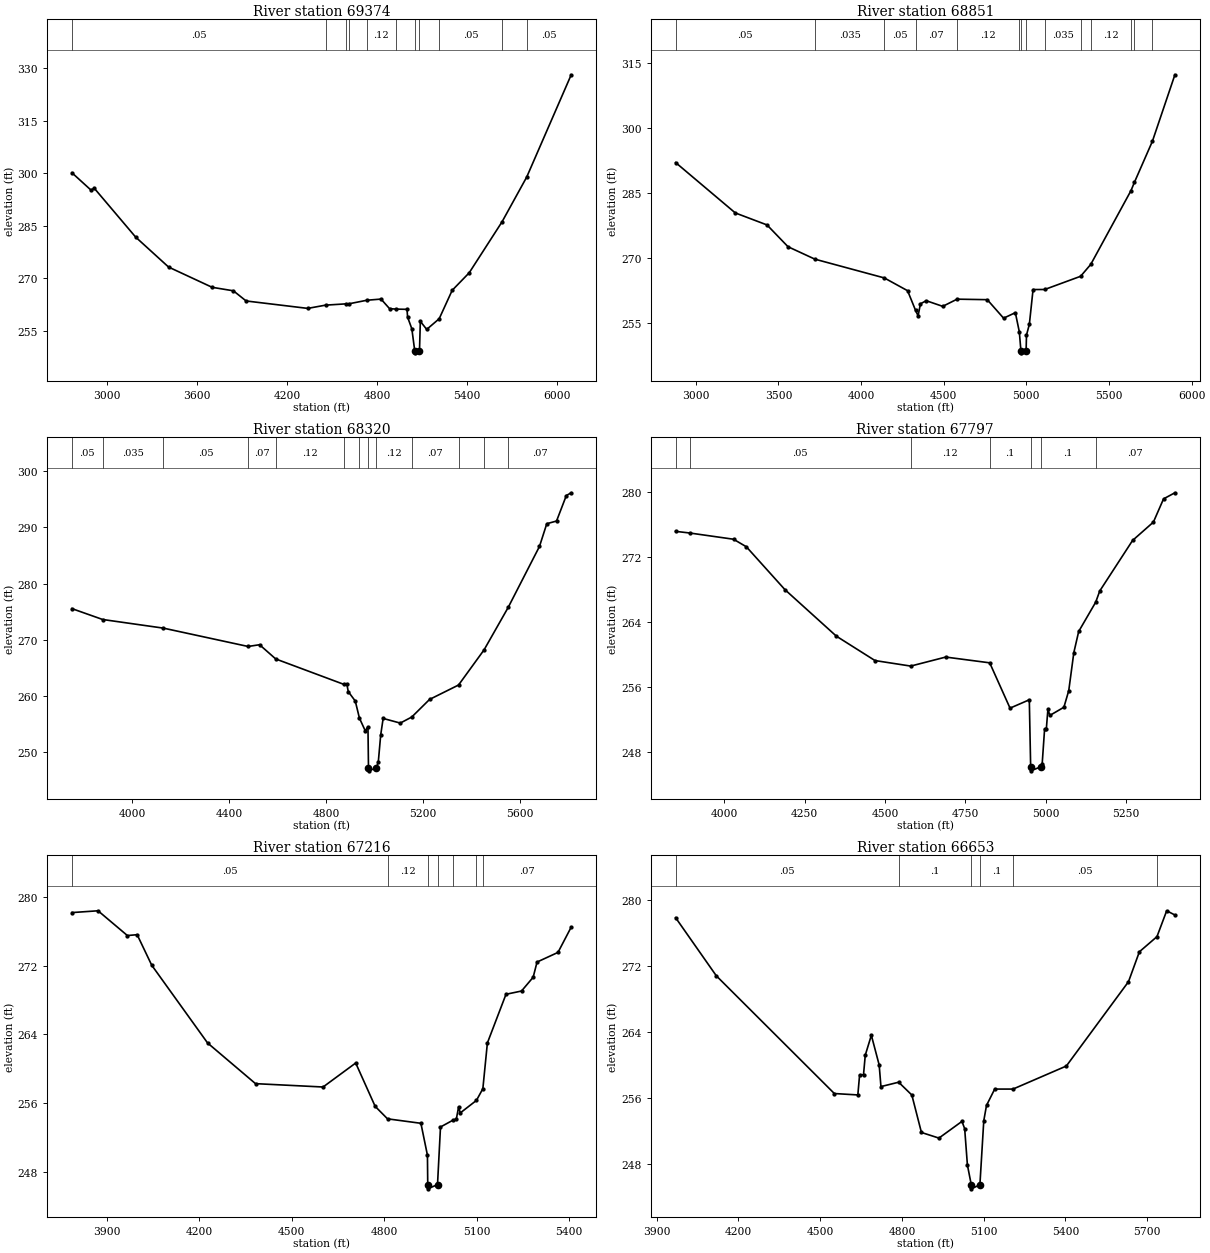
Type RM Length L Ch R = 1 ,69374   ,523,523,523
BEGIN DESCRIPTION:
CLEAR CREEK 68.0
END DESCRIPTION:
XS GIS Cut Line= 3
        2445675.       13591175.        2447275.       13589625.
      2448024.97     13588825.03
#Sta/Elev= 30
  2767.9  300.11  2895.1  295.15  2916.4   295.7  3192.2  281.74  3411.4  273.19
  3701.3  267.41  3842.8  266.41  3927.7  263.51  4337.9  261.39    4457  262.32
  4594.5  262.69  4613.1  262.71  4732.1  263.72  4825.9  264.05  4882.5  261.32
  4924.1  261.19    4999  261.12  5002.6  258.91    5031  255.56  5050.5   249.2
    5051   248.7  5081.9   249.2  5087.6  257.69  5130.1  255.39    5213  258.43
  5299.6  266.55  5412.9  271.55  5631.2  286.08  5795.9  298.89  6092.1  328.09
#Mann= 11 ,-1 , 0
  2767.9     .05       0    4457    .035       0  4594.5     .12       0
  4613.1    .035       0  4732.1     .12       0  4924.1      .1       0
  5050.5     .05       0  5081.9      .1       0    5213     .05       0
  5631.2    .035       0  5795.9     .05       0
Bank Sta=5050.5,5081.9
XS Rating Curve= 0 ,0
Exp/Cntr=0.3,0.1

Type RM Length L Ch R = 1 ,68851   ,531,531,531
BEGIN DESCRIPTION:
CLEAR CREEK 67.0
END DESCRIPTION:
XS GIS Cut Line= 3
        2446125.       13591225.        2447725.       13589825.
      2448125.02     13589024.96
#Sta/Elev= 30
  2878.1  292.07  3239.2  280.44    3431  277.67  3558.1  272.64  3720.8  269.77
  4140.6  265.44  4281.4  262.49  4329.9  257.93    4345  256.68  4359.2  259.47
  4394.3  260.18    4494  258.88  4580.9  260.54  4763.5  260.42  4862.2  256.15
  4933.4  257.42  4957.4     253    4967  248.65  4967.5  248.15  4998.5  248.65
  5000.8  252.25  5018.1  254.72  5040.5  262.76  5110.9  262.77  5328.2  265.82
  5389.5  268.56  5633.1   285.6    5654  287.53  5762.6  296.99  5898.6  312.33
#Mann= 14 ,-1 , 0
  2878.1     .05       0  3720.8    .035       0  4140.6     .05       0
  4329.9     .07       0  4580.9     .12       0  4957.4      .1       0
    4967     .05       0  4998.5      .1       0  5110.9    .035       0
  5328.2     .07       0  5389.5     .12       0  5633.1     .07       0
    5654    .035       0  5762.6     .05       0
Bank Sta=4967,4998.5
XS Rating Curve= 0 ,0
Exp/Cntr=0.3,0.1

Type RM Length L Ch R = 1 ,68320   ,523,523,523
BEGIN DESCRIPTION:
CLEAR CREEK 66.0
END DESCRIPTION:
XS GIS Cut Line= 3
      2446675.01       13590825.        2447825.       13590325.
      2448624.99       13590225.
#Sta/Elev= 30
  3750.2  275.52  3877.1  273.58  4127.7  272.04    4477  268.77  4524.4  269.08
  4591.2  266.54  4870.9  262.03  4884.2  262.12  4890.5  260.71  4919.4  259.03
  4936.5  255.98  4960.6  253.72  4971.7  254.46  4973.9  247.08  4974.4  246.58
  5005.5  247.08  5014.3  248.12  5024.3  252.99  5034.4  255.93    5105   255.1
  5152.4  256.18  5225.9  259.32  5345.5  261.89  5450.9  268.17  5550.3  275.73
  5679.4  286.61  5709.6  290.67  5749.9  291.15  5790.3   295.7  5810.4  296.19
#Mann= 13 ,-1 , 0
  3750.2     .05       0  3877.1    .035       0  4127.7     .05       0
    4477     .07       0  4591.2     .12       0  4870.9      .1       0
  4936.5     .12       0  4973.9     .05       0  5005.5     .12       0
  5152.4     .07       0  5345.5      .1       0  5450.9     .12       0
  5550.3     .07       0
Bank Sta=4973.9,5005.5
XS Rating Curve= 0 ,0
Exp/Cntr=0.3,0.1

Type RM Length L Ch R = 1 ,67797   ,581,581,581
BEGIN DESCRIPTION:
CLEAR CREEK 65.0
END DESCRIPTION:
XS GIS Cut Line= 3
        2446875.       13590825.        2448025.       13590775.
        2448375.       13590975.
#Sta/Elev= 30
  3848.4  275.13  3891.7  274.93  4028.6  274.16  4068.6  273.23  4188.7  267.95
  4348.9  262.22    4469  259.22  4580.2  258.54  4689.2  259.65  4826.1  258.94
  4889.4  253.36  4949.4  254.39  4953.6  246.14  4954.1  245.64  4985.3  246.14
  4989.5  246.52    4997   250.8  5002.4   250.8  5007.4  253.26  5013.2  252.46
  5057.1  253.47  5072.2  255.52    5088   260.2  5103.1   262.8  5156.1  266.41
  5168.7  267.79  5270.9  274.01  5335.7  276.27  5367.3  279.13  5402.6  279.88
#Mann= 7 ,-1 , 0
  3848.4    .035       0  3891.7     .05       0  4580.2     .12       0
  4826.1      .1       0  4953.6     .05       0  4985.3      .1       0
  5156.1     .07       0
Bank Sta=4953.6,4985.3
XS Rating Curve= 0 ,0
Exp/Cntr=0.3,0.1

Type RM Length L Ch R = 1 ,67216   ,563,563,563
BEGIN DESCRIPTION:
CLEAR CREEK 64.0
END DESCRIPTION:
XS GIS Cut Line= 3
      2446775.03     13590925.01        2447925.       13591325.
      2448325.04       13591275.
#Sta/Elev= 30
  3786.3  278.16    3871  278.37  3966.3  275.49    3998  275.59  4045.3  272.04
  4226.6     263  4382.2  258.27  4601.5  257.88  4707.4  260.67  4770.6  255.63
  4810.7  254.18  4919.1  253.66  4940.3  249.95  4941.3  246.54  4941.8  246.04
    4973  246.54  4982.7  253.23    5022     254  5034.1  254.15  5041.6  255.59
  5046.7  254.86  5099.3  256.32  5120.2  257.68  5134.9     263  5195.3  268.66
  5245.7  269.04  5283.5  270.64  5296.1  272.41  5364.1  273.53    5407  276.47
#Mann= 7 ,-1 , 0
  3786.3     .05       0  4810.7     .12       0  4941.3     .05       0
    4973     .12       0    5022     .07       0  5099.3     .12       0
  5120.2     .07       0
Bank Sta=4941.3,4973
XS Rating Curve= 0 ,0
Exp/Cntr=0.3,0.1

Type RM Length L Ch R = 1 ,66653   ,428,428,428
BEGIN DESCRIPTION:
CLEAR CREEK 63.0
END DESCRIPTION:
XS GIS Cut Line= 3
      2446825.04     13591125.03        2447625.       13591775.
      2448425.01       13591725.
#Sta/Elev= 30
  3969.3  277.85  4118.7  270.82  4551.8  256.58    4638  256.41  4644.5  258.84
  4658.8  258.85  4665.3  261.22  4687.6  263.63  4716.3  260.04  4722.8  257.42
  4787.8  257.95  4836.2   256.4  4871.4  251.87  4935.6  251.19  5020.1  253.21
  5030.1  252.33  5040.1  247.94  5054.3  245.55  5054.8  245.05    5086  245.55
  5100.2  253.29  5110.2  255.14  5140.3  257.12  5207.5  257.12  5403.3  259.91
  5631.3  270.11  5671.3  273.73  5735.8  275.56  5771.5  278.69  5801.6  278.18
#Mann= 6 ,-1 , 0
  3969.3     .05       0  4787.8      .1       0  5054.3     .05       0
    5086      .1       0  5207.5     .05       0  5735.8     .07       0
Bank Sta=5054.3,5086
XS Rating Curve= 0 ,0
Exp/Cntr=0.3,0.1