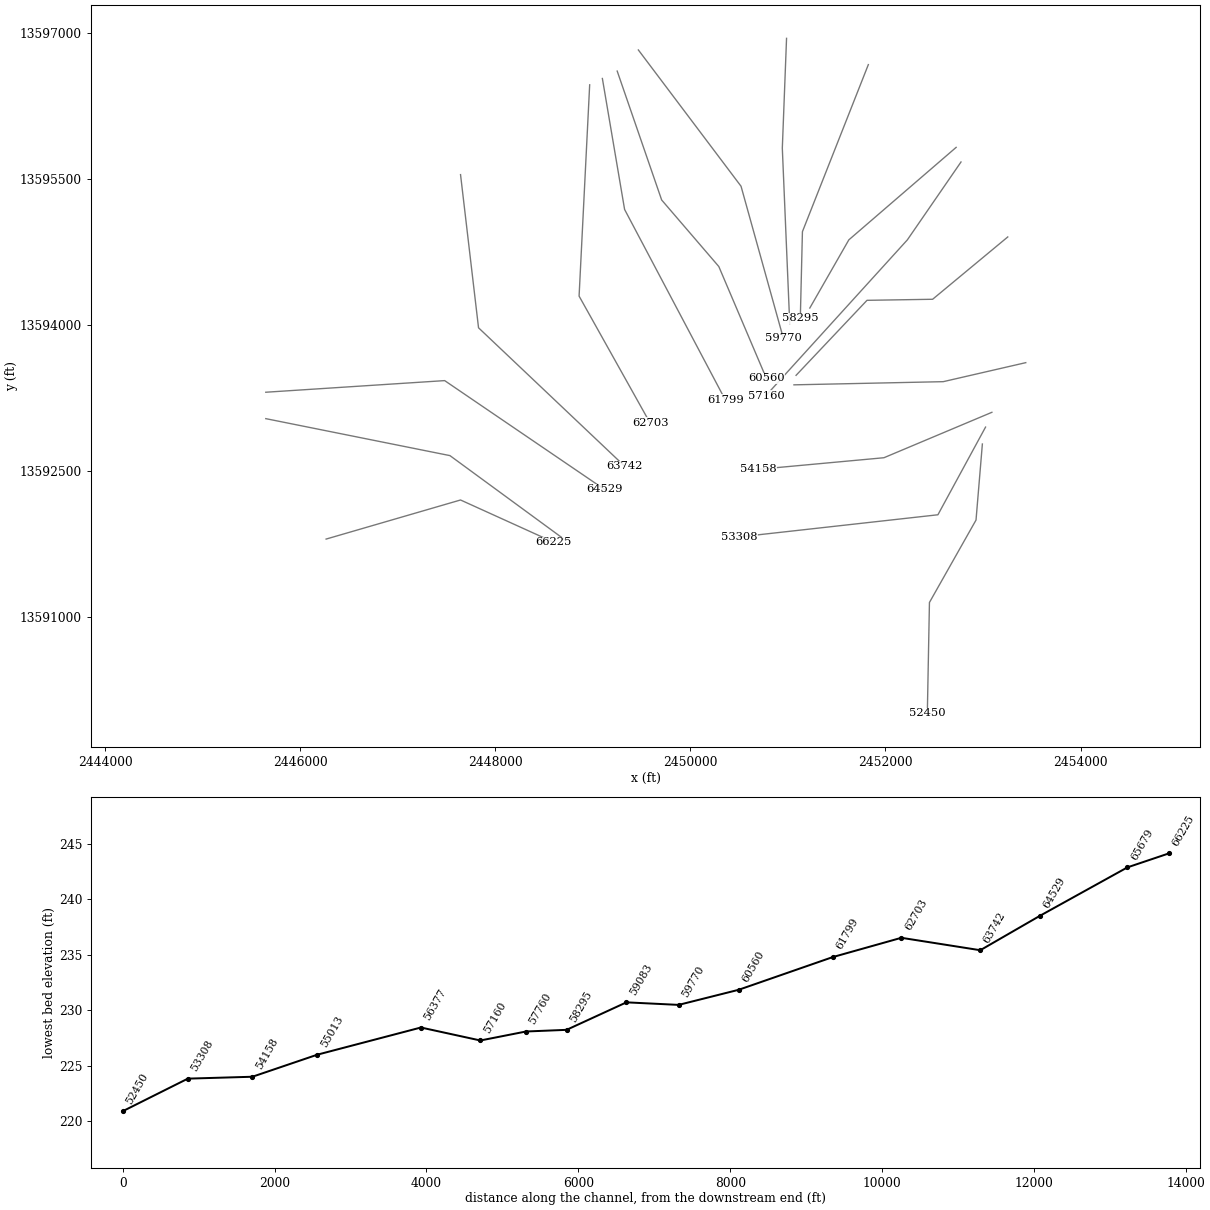
HEC-RAS study CLEAR CREEK.prj: CLEAR CREEK Base Level Engineering

--- CLEAR CREEK.g01 (geometry) --- (continued)

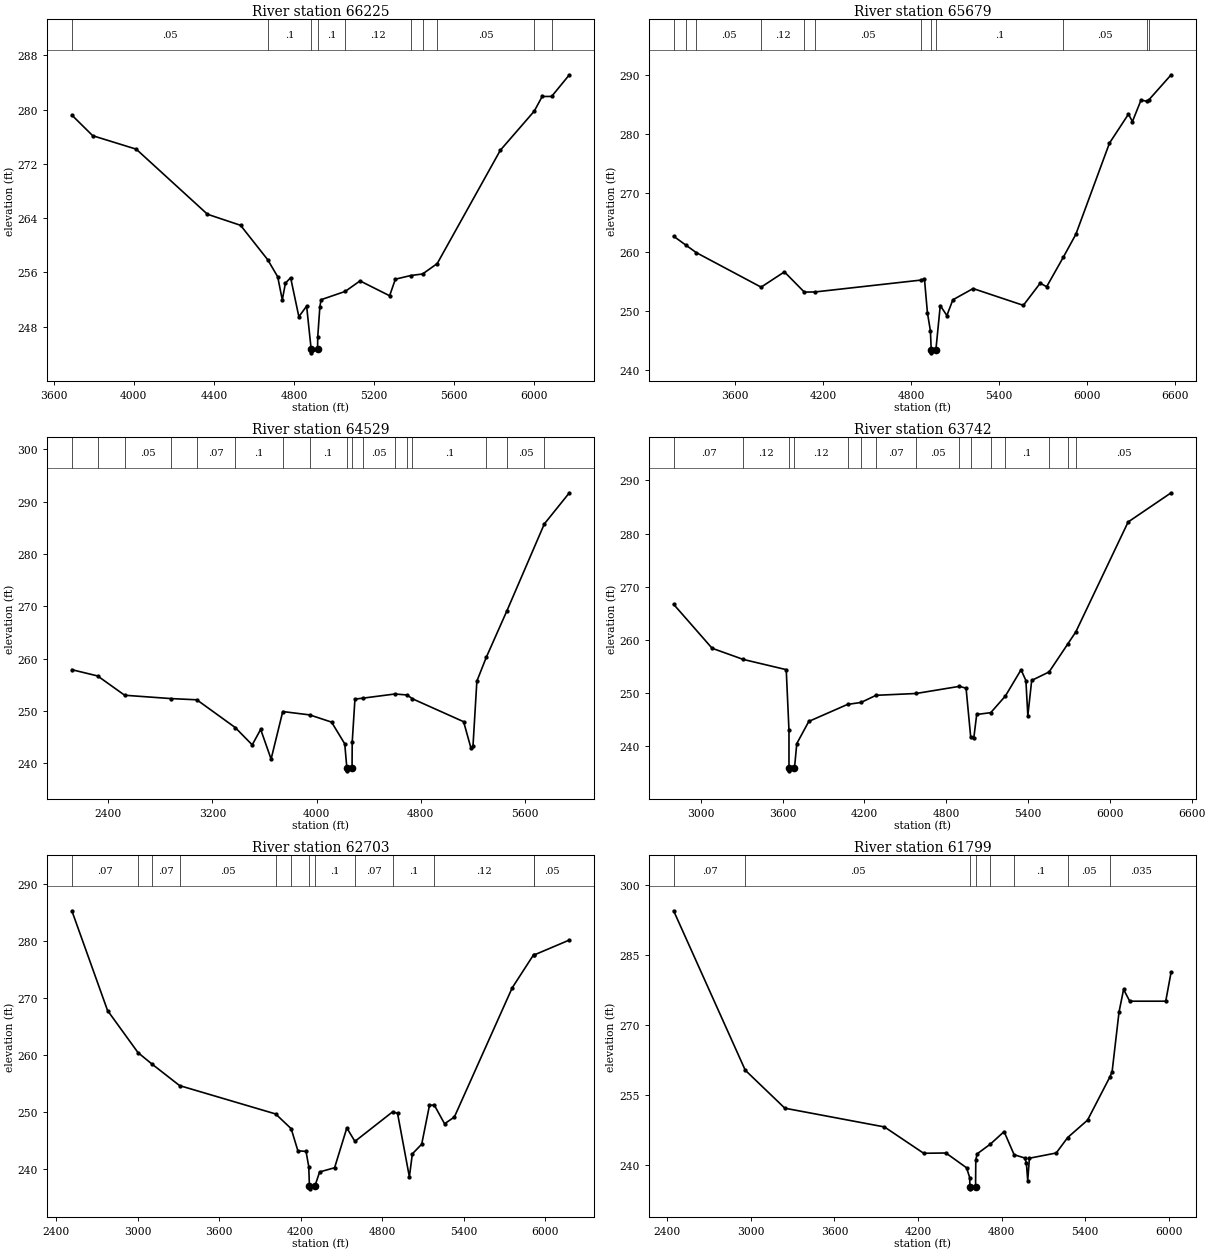
Type RM Length L Ch R = 1 ,66225   ,546,546,546
BEGIN DESCRIPTION:
X18473
END DESCRIPTION:
XS GIS Cut Line= 3
      2446266.55     13591801.77       2447644.6     13592203.25
      2448598.63      13591769.6
#Sta/Elev= 30
  3691.4  279.18  3795.7  276.14  4012.7  274.16  4368.2  264.57  4533.5  262.94
    4669  257.87  4718.8  255.36  4741.8  251.95  4757.5  254.42  4783.4  255.22
  4824.5  249.47  4863.2  251.04    4886  244.65  4886.5  244.15  4917.8  244.65
  4918.8  246.54  4929.3  250.94  4935.4  251.98  5055.8   253.2  5129.7  254.75
  5277.5  252.56  5306.1     255  5382.6  255.54  5442.2  255.77    5515   257.3
  5830.1     274  5999.6  279.77  6038.9  281.92  6086.2  281.93  6174.7  285.12
#Mann= 10 ,-1 , 0
  3691.4     .05       0    4669      .1       0    4886     .05       0
  4917.8      .1       0  5055.8     .12       0  5382.6     .05       0
  5442.2     .12       0    5515     .05       0  5999.6     .07       0
  6086.2     .05       0
Bank Sta=4886,4917.8
XS Rating Curve= 0 ,0
Exp/Cntr=0.3,0.1

Type RM Length L Ch R = 1 ,65679   ,1150,1150,1150
BEGIN DESCRIPTION:
X18472
END DESCRIPTION:
XS GIS Cut Line= 3
      2445648.12     13593038.74      2447536.09     13592658.98
      2448718.83     13591790.91
#Sta/Elev= 30
  3180.4  262.68  3267.3  261.11  3334.9   259.9    3777  254.04  3935.9  256.63
  4071.6   253.2  4143.3  253.22  4868.6  255.24  4890.9  255.47  4911.3  249.67
  4931.7  246.61  4937.1  243.39  4937.6  242.89  4968.9  243.39  4998.8  250.91
  5043.9  249.22  5084.7  251.89  5222.7   253.8  5565.4  250.95  5680.4  254.71
  5724.3  254.11  5837.5   259.1  5923.5  263.01  6152.7  278.48  6282.3   283.4
  6309.3  282.14    6368  285.79  6411.2  285.56  6420.2  285.79  6573.3  290.08
#Mann= 12 ,-1 , 0
  3180.4     .05       0  3267.3     .07       0  3334.9     .05       0
    3777     .12       0  4071.6     .07       0  4143.3     .05       0
  4868.6      .1       0  4937.1     .05       0  4968.9      .1       0
  5837.5     .05       0  6411.2     .07       0  6420.2     .05       0
Bank Sta=4937.1,4968.9
XS Rating Curve= 0 ,0
Exp/Cntr=0.3,0.1

Type RM Length L Ch R = 1 ,64529   ,787,787,787
BEGIN DESCRIPTION:
X18471
END DESCRIPTION:
XS GIS Cut Line= 3
      2445648.02     13593310.01      2447481.84     13593429.38
      2449120.19     13592311.83
#Sta/Elev= 30
  2120.2  257.88  2318.2  256.68  2525.8  252.99  2883.1  252.35  3079.9  252.12
    3375  246.81  3505.4   243.5  3570.2  246.46  3650.4  240.78  3739.9  249.87
  3946.8  249.23  4114.8  247.85  4215.9   243.7  4232.3  239.03  4233.3  238.53
  4272.1  239.03  4273.3     244  4294.3  252.25  4354.2  252.43  4601.1  253.23
  4695.8  253.04  4735.3  252.32  5128.9  247.93  5185.8  242.83  5200.7  243.19
  5230.6  255.68    5303  260.25  5461.4  269.14  5748.7  285.76  5941.1  291.72
#Mann= 17 ,-1 , 0
  2120.2     .05       0  2318.2     .07       0  2525.8     .05       0
  2883.1     .12       0  3079.9     .07       0    3375      .1       0
  3739.9     .12       0  3946.8      .1       0  4232.3     .05       0
  4272.1      .1       0  4354.2     .05       0  4601.1     .07       0
  4695.8     .05       0  4735.3      .1       0    5303     .07       0
  5461.4     .05       0  5748.7     .07       0
Bank Sta=4232.3,4272.1
XS Rating Curve= 0 ,0
Exp/Cntr=0.3,0.1

Type RM Length L Ch R = 1 ,63742   ,1039,1039,1039
BEGIN DESCRIPTION:
CLEAR CREEK 62.0
END DESCRIPTION:
XS GIS Cut Line= 3
       2447644.6     13595545.26      2447829.06     13593971.91
      2449326.49     13592550.44
#Sta/Elev= 30
  2800.7  266.71  3082.9  258.45  3311.6  256.35  3626.6  254.43  3646.7     243
  3646.8  235.92  3647.8  235.42    3687  235.92    3704  240.54  3792.2  244.71
  4076.3   247.9  4175.4  248.27  4285.2  249.61  4578.4  249.95  4895.8  251.29
  4945.5  250.95  4979.7  241.71  5002.1  241.57  5023.5  246.01  5126.4  246.35
  5233.6  249.47  5348.8  254.41  5384.3  252.38  5398.5  245.79  5426.8  252.41
  5554.3     254  5693.7  259.34  5750.9  261.55  6133.9  282.17  6449.5  287.66
#Mann= 15 ,-1 , 0
  2800.7     .07       0  3311.6     .12       0  3646.8     .05       0
    3687     .12       0  4076.3     .07       0  4175.4      .1       0
  4285.2     .07       0  4578.4     .05       0  4895.8     .07       0
  4979.7      .1       0  5126.4     .12       0  5233.6      .1       0
  5554.3     .12       0  5693.7     .07       0  5750.9     .05       0
Bank Sta=3646.8,3687
XS Rating Curve= 0 ,0
Exp/Cntr=0.3,0.1

Type RM Length L Ch R = 1 ,62703   ,904,904,904
BEGIN DESCRIPTION:
CLEAR CREEK 61.0
END DESCRIPTION:
XS GIS Cut Line= 3
      2448968.38     13596467.55      2448859.88     13594297.43
      2449586.86     13592995.36
#Sta/Elev= 30
  2515.2   285.3  2778.1  267.81  3002.7  260.42  3101.8  258.49  3308.9  254.64
  4016.1  249.67  4130.3  247.09  4179.8  243.22  4239.9   243.1  4259.9  240.44
  4264.8  237.04  4265.8  236.54  4305.2  237.04    4340   239.5  4450.2  240.24
  4540.3  247.22  4599.8  244.86  4878.4  250.06    4914  249.76  5000.9  238.64
    5023  242.68  5091.7  244.37  5148.9  251.18    5184  251.24  5260.2  247.95
  5332.2  249.13  5758.3  271.79  5915.5  277.58  5919.7  277.55  6179.3  280.17
#Mann= 13 ,-1 , 0
  2515.2     .07       0  3002.7     .05       0  3101.8     .07       0
  3308.9     .05       0  4016.1     .07       0  4130.3      .1       0
  4264.8     .05       0  4305.2      .1       0  4599.8     .07       0
  4878.4      .1       0    5184     .12       0  5915.5     .07       0
  5919.7     .05       0
Bank Sta=4264.8,4305.2
XS Rating Curve= 0 ,0
Exp/Cntr=0.3,0.1

Type RM Length L Ch R = 1 ,61799   ,1239,1239,1239
BEGIN DESCRIPTION:
CLEAR CREEK 60.0
END DESCRIPTION:
XS GIS Cut Line= 3
      2449098.59     13596532.66      2449326.45     13595187.19
      2450357.28     13593234.05
#Sta/Elev= 30
  2444.9  294.46  2959.4  260.25  3243.8   252.1    3959  248.08  4240.8  242.43
  4400.6  242.49  4549.1  239.31  4571.1  237.22  4572.9   235.3  4573.9   234.8
  4613.4   235.3  4615.1  241.08  4625.9  242.33  4720.6  244.42  4818.3  247.08
  4890.4  242.12  4965.3  241.43  4978.2  240.42    4988  236.57  5000.2  241.37
  5192.7  242.49    5275  245.81  5417.6  249.54    5578  258.81  5594.1  259.95
  5643.8  272.75  5676.5  277.59  5720.6  275.06  5979.2  275.06    6018  281.33
#Mann= 8 ,-1 , 0
  2444.9     .07       0  2959.4     .05       0  4572.9     .05       0
  4613.4     .05       0  4720.6     .12       0  4890.4      .1       0
    5275     .05       0    5578    .035       0
Bank Sta=4572.9,4613.4
XS Rating Curve= 0 ,0
Exp/Cntr=0.3,0.1

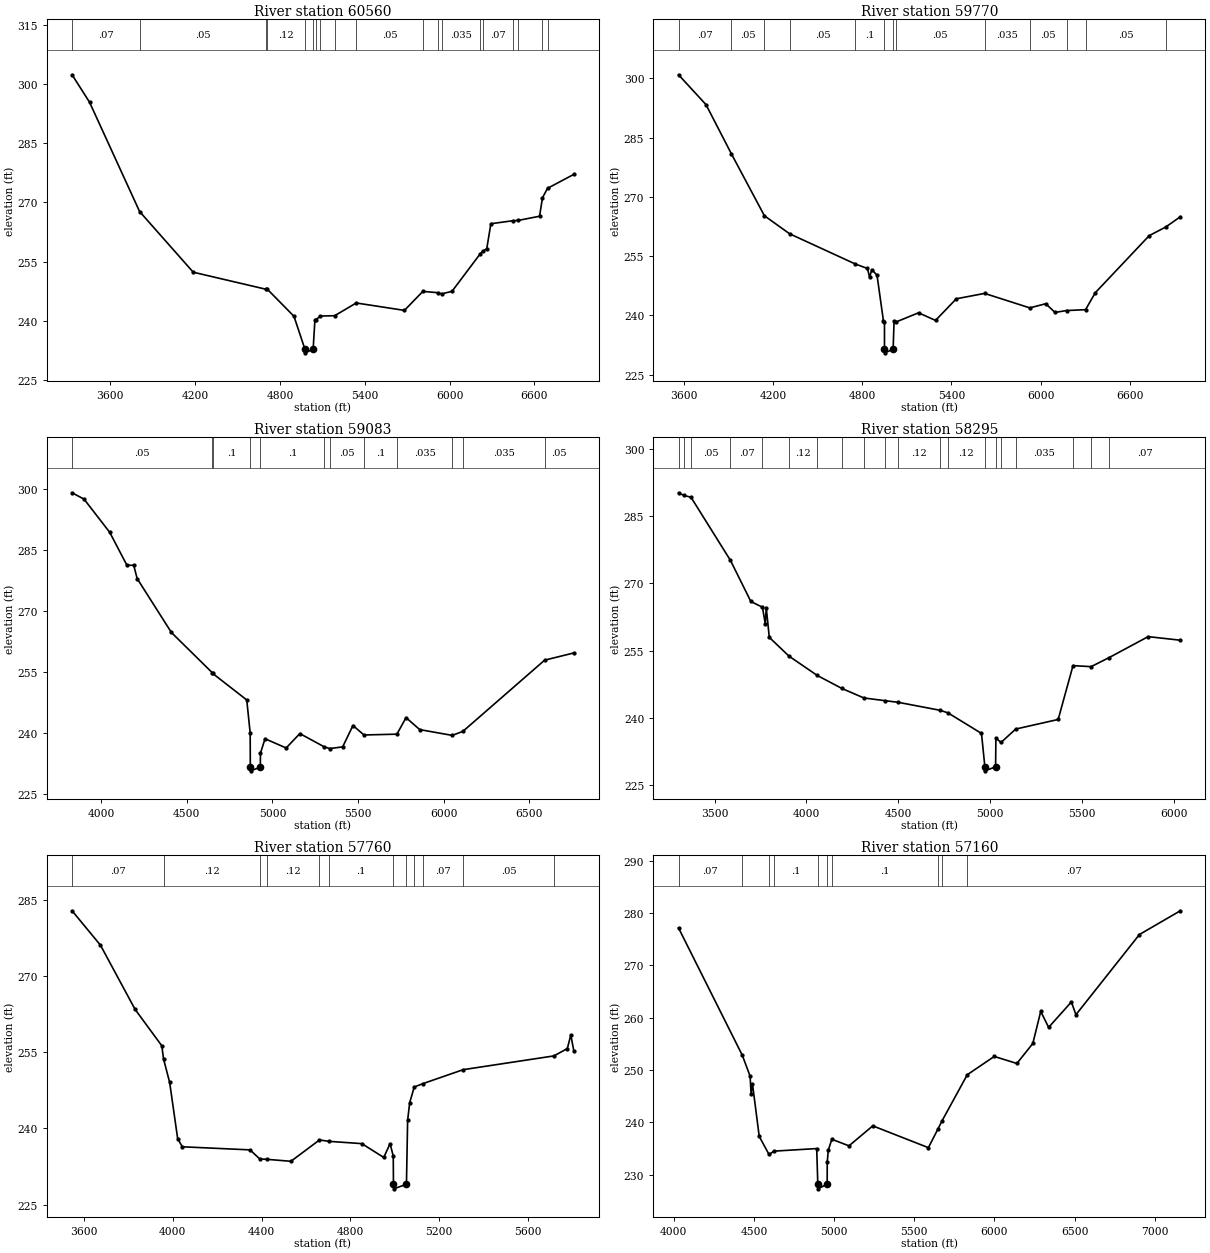
Type RM Length L Ch R = 1 ,60560   ,790,790,790
BEGIN DESCRIPTION:
X18470
END DESCRIPTION:
XS GIS Cut Line= 4
      2449250.49     13596608.66      2449706.23     13595284.84
      2450292.17     13594601.25      2450780.23     13593451.58
#Sta/Elev= 30
  3329.6  302.34    3453   295.4  3807.3  267.67  4186.6  252.29  4704.7  247.94
  4710.7  247.98  4899.3  241.11  4976.8  232.75  4978.1  231.85  5034.8  232.75
  5047.5  240.23  5051.9  240.18  5086.4  241.18  5186.9  241.26  5339.8  244.49
  5680.7  242.61  5810.7  247.43  5916.5   247.1  5944.8  246.81    6017  247.44
  6214.7  256.86  6233.8  257.58  6262.9  258.24  6291.9  264.58  6445.3  265.33
  6484.6  265.42  6636.3  266.48  6656.8  271.13  6692.8  273.56    6879   277.1
#Mann= 19 ,-1 , 0
  3329.6     .07       0  3807.3     .05       0  4704.7     .07       0
  4710.7     .12       0  4976.8     .05       0  5034.8     .12       0
  5051.9     .07       0  5086.4     .12       0  5186.9     .07       0
  5339.8     .05       0  5810.7    .035       0  5916.5     .05       0
  5944.8    .035       0  6214.7     .05       0  6233.8     .07       0
  6445.3    .035       0  6484.6     .05       0  6656.8    .035       0
  6692.8     .07       0
Bank Sta=4976.8,5034.8
XS Rating Curve= 0 ,0
Exp/Cntr=0.3,0.1

Type RM Length L Ch R = 1 ,59770   ,687,687,687
BEGIN DESCRIPTION:
X18469
END DESCRIPTION:
XS GIS Cut Line= 3
      2449467.51     13596825.65      2450520.03      13595425.9
      2450954.06     13593863.38
#Sta/Elev= 30
  3565.9   300.9  3750.6  293.34  3920.4  280.94  4143.2   265.2  4312.8  260.63
  4755.1  252.97  4835.6  251.86  4850.2  249.62  4864.8  251.57  4900.2  250.14
    4943  238.64  4950.2  238.42  4950.3  231.39  4951.7  230.49  5008.4  231.39
  5014.7  238.58  5025.6  238.27  5179.3  240.63  5293.3   238.7  5433.3  244.18
  5623.3  245.54  5927.1  241.87  6034.3  242.93  6096.5  240.72  6173.8   241.2
  6301.9  241.42  6367.4  245.72  6729.6  260.16  6840.3  262.34  6938.9  264.94
#Mann= 13 ,-1 , 0
  3565.9     .07       0  3920.4     .05       0  4143.2     .07       0
  4312.8     .05       0  4755.1      .1       0  4950.3     .05       0
  5008.4      .1       0  5025.6     .05       0  5623.3    .035       0
  5927.1     .05       0  6173.8    .035       0  6301.9     .05       0
  6840.3     .07       0
Bank Sta=4950.3,5008.4
XS Rating Curve= 0 ,0
Exp/Cntr=0.3,0.1

Type RM Length L Ch R = 1 ,59083   ,788,788,788
BEGIN DESCRIPTION:
CLEAR CREEK 59.0
END DESCRIPTION:
XS GIS Cut Line= 3
      2450986.61     13596945.03      2450943.21     13595816.53
      2451019.17     13594015.27
#Sta/Elev= 30
  3829.5  299.18  3899.6  297.61  4049.7  289.43  4149.8  281.35  4189.8  281.32
  4209.8  278.06    4410  264.78  4648.2   254.9  4650.5  254.72  4850.3  248.17
  4870.3  240.01  4871.1  231.62  4872.5  230.72  4929.6  231.62  4930.3  235.07
  4957.1  238.62  5080.5  236.35  5160.5  239.89  5304.5   236.6  5335.9  236.21
  5410.8  236.62  5470.8  241.88  5535.4  239.55  5727.7  239.75  5781.1  243.82
  5861.2  240.87  6050.7  239.45  6113.1  240.43  6590.9  257.97  6761.7  259.75
#Mann= 12 ,-1 , 0
  3829.5     .05       0  4648.2     .12       0  4650.5      .1       0
  4871.1     .05       0  4929.6      .1       0  5304.5      .1       0
  5335.9     .05       0  5535.4      .1       0  5727.7    .035       0
  6050.7     .05       0  6113.1    .035       0  6590.9     .05       0
Bank Sta=4871.1,4929.6
XS Rating Curve= 0 ,0
Exp/Cntr=0.3,0.1

Type RM Length L Ch R = 1 ,58295   ,535,535,535
BEGIN DESCRIPTION:
CLEAR CREEK 58.0
END DESCRIPTION:
XS GIS Cut Line= 3
      2451825.01     13596675.04      2451149.37     13594959.32
      2451127.67     13594069.74
#Sta/Elev= 30
  3303.3  290.21    3331  289.64  3371.2  289.21  3586.3  275.13  3697.3  265.98
  3760.4   264.7  3775.9  261.03  3781.3  264.57  3797.7  257.99  3905.3   253.8
  4058.9   249.5  4193.3   246.6  4313.3  244.48  4429.6  243.87  4500.2  243.51
  4728.8  241.73  4771.2  241.16  4953.8  236.58  4972.2  229.14  4973.6  228.24
  5030.7  229.14  5032.3  235.54  5060.1  234.56  5140.1  237.55  5371.6  239.69
  5452.4  251.69    5551  251.46  5649.7  253.49  5861.8  258.15  6037.1  257.35
#Mann= 20 ,-1 , 0
  3303.3     .05       0    3331     .07       0  3371.2     .05       0
  3586.3     .07       0  3760.4     .05       0  3905.3     .12       0
  4058.9     .05       0  4193.3     .07       0  4313.3     .12       0
  4429.6     .07       0  4500.2     .12       0  4728.8     .07       0
  4771.2     .12       0  4972.2     .05       0  5030.7     .12       0
  5060.1      .1       0  5140.1    .035       0  5452.4     .07       0
    5551     .05       0  5649.7     .07       0
Bank Sta=4972.2,5030.7
XS Rating Curve= 0 ,0
Exp/Cntr=0.3,0.1

Type RM Length L Ch R = 1 ,57760   ,600,600,600
BEGIN DESCRIPTION:
CLEAR CREEK 57.0
END DESCRIPTION:
XS GIS Cut Line= 3
      2452725.04     13595825.03        2451625.       13594875.
      2451225.01     13594175.02
#Sta/Elev= 30
  3546.5  282.83  3674.3  276.06  3830.1  263.43  3950.8  256.24  3958.3  253.68
  3985.9  249.05    4022  237.98  4042.9  236.37  4347.9  235.76  4391.8  233.97
  4424.4   233.9  4532.1  233.51  4660.6  237.71  4703.7  237.44  4851.3  236.99
  4950.1  234.27  4978.6  236.99  4992.9  234.54  4993.8  228.99  4995.2  228.09
  5052.3  228.99  5057.6  241.57  5066.9  245.06  5087.4  248.14  5126.9  248.81
  5307.8  251.55  5716.5  254.26  5776.7   255.7  5792.5  258.39  5806.2   255.2
#Mann= 12 ,-1 , 0
  3546.5     .07       0  3958.3     .12       0  4391.8     .07       0
  4424.4     .12       0  4660.6     .07       0  4703.7      .1       0
  4993.8     .05       0  5052.3      .1       0  5087.4     .12       0
  5126.9     .07       0  5307.8     .05       0  5716.5     .07       0
Bank Sta=4993.8,5052.3
XS Rating Curve= 0 ,0
Exp/Cntr=0.3,0.1

Type RM Length L Ch R = 1 ,57160   ,783,783,783
BEGIN DESCRIPTION:
CLEAR CREEK 56.0
END DESCRIPTION:
XS GIS Cut Line= 3
        2452775.       13595675.        2452225.       13594875.
        2450775.       13593275.
#Sta/Elev= 30
  4029.3  277.16    4427  252.82  4475.8  248.81  4481.9  245.42  4490.4  247.38
  4532.6  237.31  4593.7  233.85  4625.1  234.49  4891.2  234.98    4898  228.18
  4899.4  227.28  4956.6  228.18  4956.8   232.4  4963.7  234.69  4985.5  236.76
  5092.4   235.5  5241.1  239.32  5587.8  235.15    5648  238.75  5672.5  240.25
  5830.3  249.09  5998.7  252.59  6139.9  251.25  6239.3  255.07  6288.6   261.2
  6337.9  258.15  6479.9  263.01  6508.2  260.57  6904.3   275.9  7159.4  280.44
#Mann= 10 ,-1 , 0
  4029.3     .07       0    4427      .1       0  4593.7     .07       0
  4625.1      .1       0    4898     .05       0  4956.6      .1       0
  4985.5      .1       0    5648     .07       0  5672.5      .1       0
  5830.3     .07       0
Bank Sta=4898,4956.6
XS Rating Curve= 0 ,0
Exp/Cntr=0.3,0.1

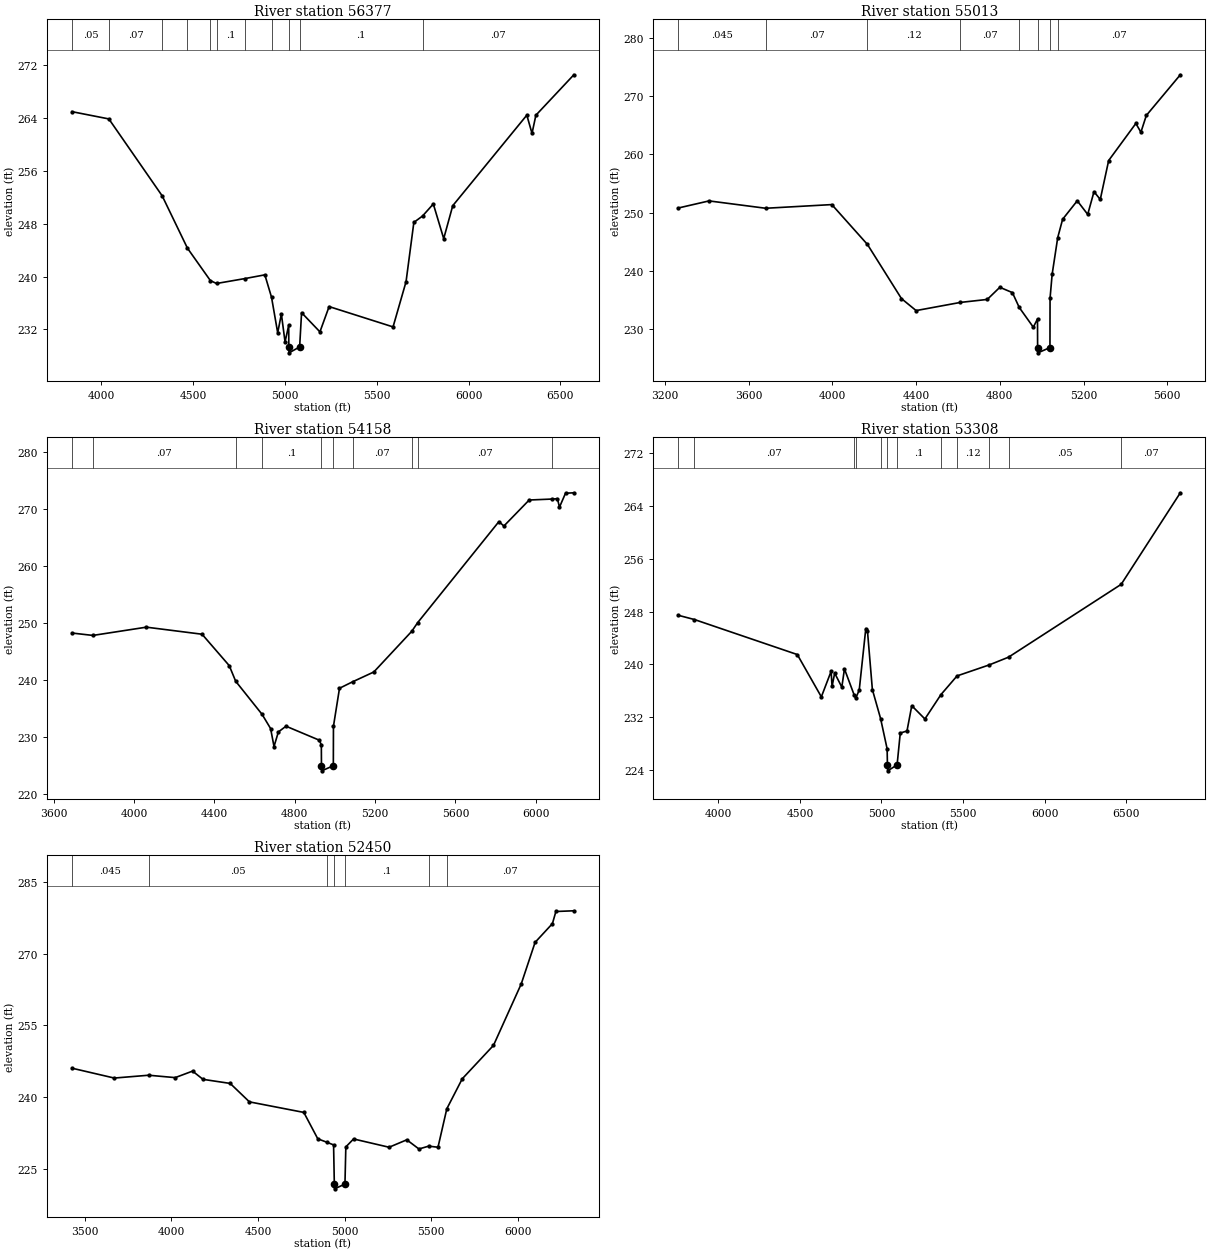
Type RM Length L Ch R = 1 ,56377   ,1364,1364,1364
BEGIN DESCRIPTION:
X18468
END DESCRIPTION:
XS GIS Cut Line= 4
      2453254.39     13594905.06      2452484.01     13594264.88
      2451811.26     13594254.03      2451084.24      13593483.6
#Sta/Elev= 30
  3839.7     265  4040.7   263.9    4331  252.25  4468.8  244.31  4593.7   239.4
  4627.1  238.96  4782.9  239.71  4890.4  240.27  4926.9  236.86  4960.4  231.48
  4980.4  234.34  5000.4  230.11  5020.4  232.63  5020.9  229.35  5022.3  228.45
  5079.9  229.35  5090.4  234.54  5190.4  231.63  5240.4  235.46  5588.7  232.38
  5659.5  239.23    5702  248.22  5749.1  249.18    5808  251.01  5864.6  245.76
  5913.9  250.75  6317.3  264.47  6345.6  261.71  6366.7  264.46  6573.5  270.59
#Mann= 11 ,-1 , 0
  3839.7     .05       0  4040.7     .07       0    4331     .12       0
  4468.8      .1       0  4593.7     .12       0  4627.1      .1       0
  4782.9     .12       0  4926.9      .1       0  5020.9     .05       0
  5079.9      .1       0  5749.1     .07       0
Bank Sta=5020.9,5079.9
XS Rating Curve= 0 ,0
Exp/Cntr=0.3,0.1

Type RM Length L Ch R = 1 ,55013   ,855,855,855
BEGIN DESCRIPTION:
X18467
END DESCRIPTION:
XS GIS Cut Line= 3
      2453438.84     13593613.83      2452592.51     13593418.52
      2451062.53     13593385.97
#Sta/Elev= 30
  3263.7  250.82  3410.2  252.03  3680.8  250.77  3996.9   251.4  4167.2  244.57
  4329.8  235.29  4399.8  233.24  4611.7  234.64  4739.9  235.15  4799.9  237.23
    4860  236.32  4892.6  233.78    4960  230.39    4980  231.81  4980.5   226.9
  4981.9     226  5039.5   226.9    5040  235.36    5050  239.46  5076.6  245.74
    5100  248.88    5170  252.05    5220  249.72    5250  253.61    5280  252.28
  5320.1  258.95  5450.1   265.3  5474.2   263.8  5500.1  266.67  5662.6  273.64
#Mann= 8 ,-1 , 0
  3263.7    .045       0  3680.8     .07       0  4167.2     .12       0
  4611.7     .07       0  4892.6      .1       0  4980.5     .05       0
  5039.5      .1       0  5076.6     .07       0
Bank Sta=4980.5,5039.5
XS Rating Curve= 0 ,0
Exp/Cntr=0.3,0.1

Type RM Length L Ch R = 1 ,54158   ,850,850,850
BEGIN DESCRIPTION:
X18466
END DESCRIPTION:
XS GIS Cut Line= 3
      2453091.62     13593103.85      2451984.88     13592637.27
      2450693.65     13592517.92
#Sta/Elev= 30
  3691.5  248.21  3795.7  247.79    4062  249.24    4339     248  4474.2  242.49
  4506.4  239.74  4637.7  233.93  4680.2  231.43  4697.1  228.28  4718.8  230.84
  4756.8  231.85  4922.6  229.39  4932.6  228.56  4933.2  224.91  4934.6  224.01
  4992.3  224.91  4992.9  231.83    5023  238.51  5087.8  239.64  5193.8  241.37
  5382.5  248.51  5411.7  250.02  5816.4  267.78  5841.1     267    5967  271.57
  6081.9  271.74  6107.6   271.8  6117.7  270.31  6147.8  272.76  6189.3  272.84
#Mann= 10 ,-1 , 0
  3691.5    .045       0  3795.7     .07       0  4506.4     .12       0
  4637.7      .1       0  4933.2     .05       0  4992.3      .1       0
  5087.8     .07       0  5382.5     .12       0  5411.7     .07       0
  6081.9    .035       0
Bank Sta=4933.2,4992.3
XS Rating Curve= 0 ,0
Exp/Cntr=0.3,0.1

Type RM Length L Ch R = 1 ,53308   ,858,858,858
BEGIN DESCRIPTION:
X18465
END DESCRIPTION:
XS GIS Cut Line= 3
      2453026.56     13592951.98      2452538.26     13592051.34
      2450499.14     13591823.56
#Sta/Elev= 30
  3755.4  247.43  3853.8  246.79  4484.1  241.48  4631.5  235.06  4691.4  238.94
  4697.1  236.65  4713.2  238.66    4757  236.54  4773.1   239.3  4832.9  235.33
    4842  234.84  4863.7   236.1  4903.9  245.42    4914   245.1  4944.2  236.17
  4994.6  231.77  5034.7  227.17  5036.5  224.74  5037.9  223.84  5095.7  224.74
  5115.2  229.57  5156.4  229.89  5185.7  233.72  5266.2  231.71  5364.7  235.41
  5463.3  238.24  5660.7  239.91  5778.6  241.08  6469.2  252.13  6831.7  266.02
#Mann= 12 ,-1 , 0
  3755.4    .045       0  3853.8     .07       0  4832.9     .05       0
    4842     .07       0  4994.6      .1       0  5036.5     .05       0
  5095.7      .1       0  5364.7     .07       0  5463.3     .12       0
  5660.7     .07       0  5778.6     .05       0  6469.2     .07       0
Bank Sta=5036.5,5095.7
XS Rating Curve= 0 ,0
Exp/Cntr=0.3,0.1

Type RM Length L Ch R = 1 ,52450   ,1124,1124,1124
BEGIN DESCRIPTION:
X18464
END DESCRIPTION:
XS GIS Cut Line= 4
      2452993.99     13592778.35      2452928.89     13591997.08
      2452451.45     13591150.73      2452429.75     13590011.44
#Sta/Elev= 30
  3426.8  246.08    3671  244.02  3869.5  244.61  4022.2  244.11  4122.6  245.47
  4182.8  243.75  4339.5   242.9  4450.6  239.05  4764.3  236.85  4844.9  231.34
  4895.3  230.65    4936  230.07  4940.3   221.9  4941.8   220.9  5001.6   221.9
  5006.7  229.65  5051.3  231.31  5256.1  229.58  5358.3  231.13  5428.3  229.22
  5484.7  229.81  5538.3  229.58  5589.2  237.61  5678.3  243.87  5858.4  250.84
  6018.4  263.66  6098.4  272.34  6198.4  276.25  6218.4  278.78    6322  278.93
#Mann= 7 ,-1 , 0
  3426.8    .045       0  3869.5     .05       0  4895.3      .1       0
  4940.3     .05       0  5001.6      .1       0  5484.7     .12       0
  5589.2     .07       0
Bank Sta=4940.3,5001.6
XS Rating Curve= 0 ,0
Exp/Cntr=0.3,0.1