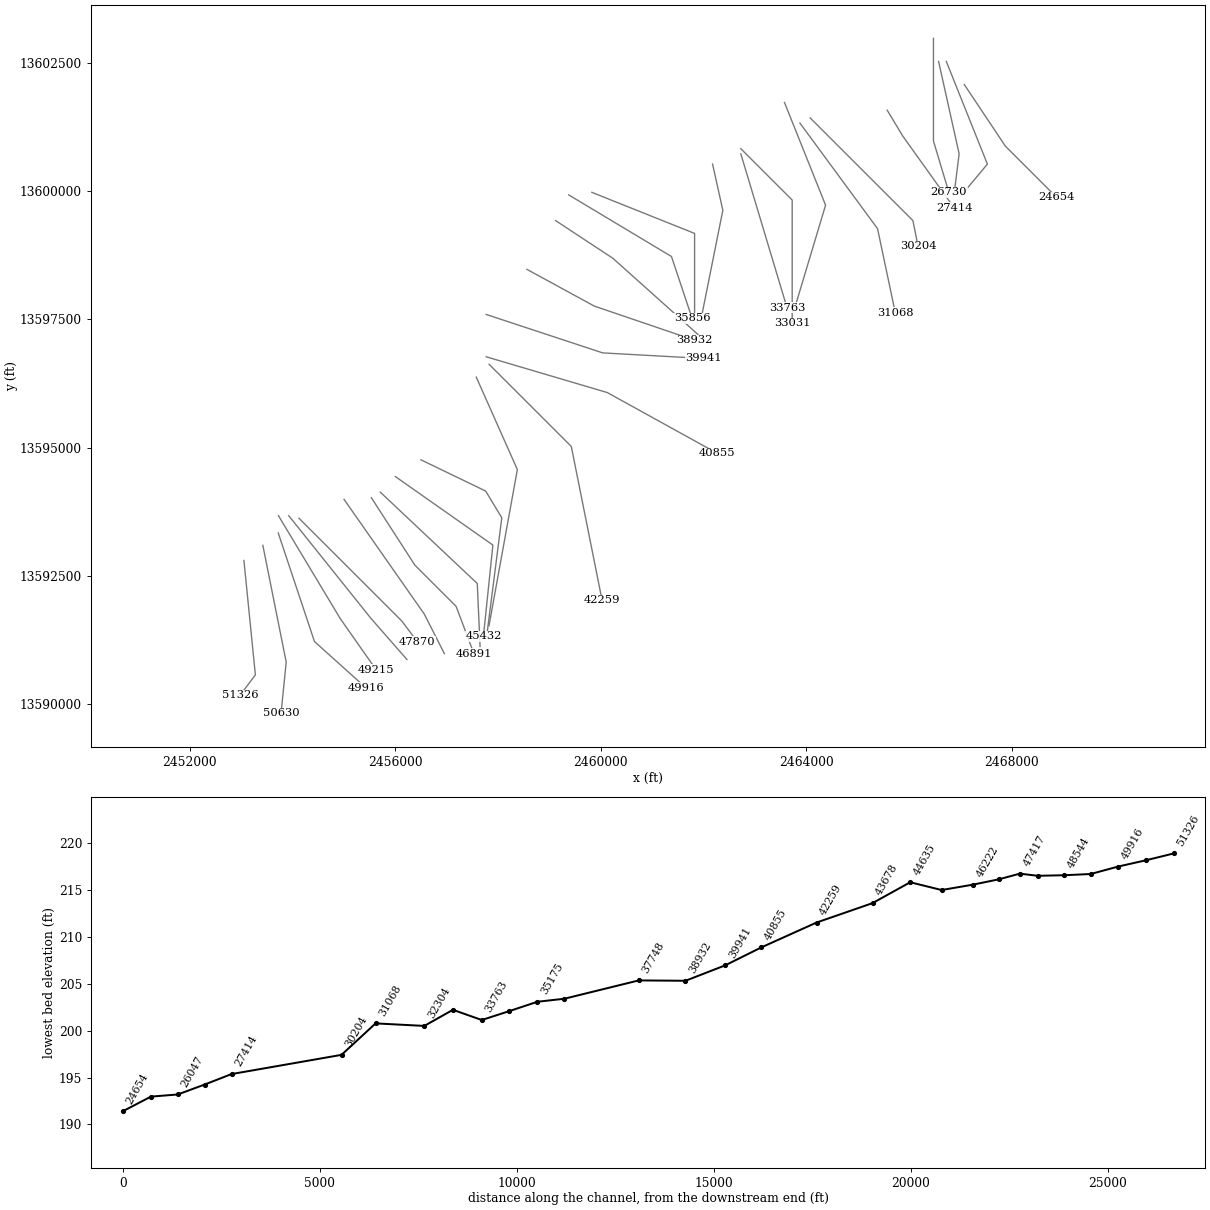
HEC-RAS study CLEAR CREEK.prj: CLEAR CREEK Base Level Engineering

--- CLEAR CREEK.g01 (geometry) --- (continued)

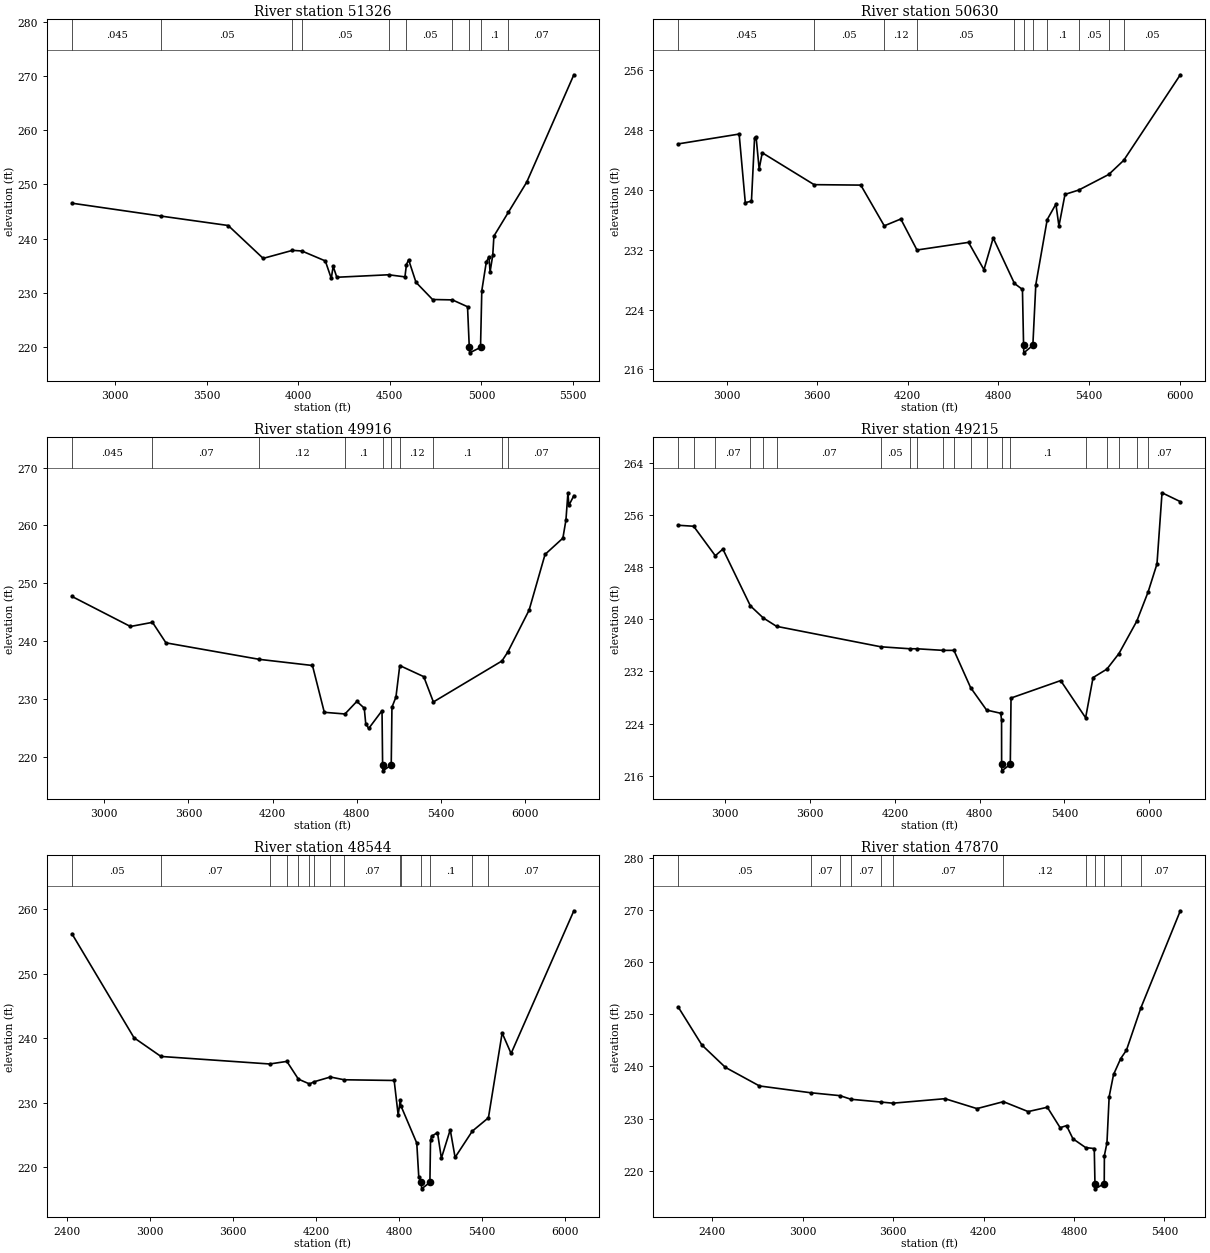
Type RM Length L Ch R = 1 ,51326   ,696,696,696
BEGIN DESCRIPTION:
CLEAR CREEK 55.0
END DESCRIPTION:
XS GIS Cut Line= 3
      2453052.13      13592803.7        2453275.       13590575.
      2452975.01     13590175.01
#Sta/Elev= 30
  2764.7  246.52  3252.1  244.14  3617.6  242.41  3808.6  236.35  3968.6  237.83
  4019.8  237.71  4147.8  235.88  4180.4  232.65  4190.5   234.9  4210.6  232.87
  4493.3  233.33  4582.4  232.94  4590.7  235.22  4602.5   236.1  4642.7  231.94
  4733.2  228.77  4841.4   228.7  4924.1  227.44  4933.7  219.94  4935.2  218.94
    4995  219.94    5002   230.4  5026.4  235.64    5041  236.66  5047.2  233.86
  5061.8  236.93  5068.1  240.46  5147.4  244.87  5247.2   250.4  5504.5  270.19
#Mann= 10 ,-1 , 0
  2764.7    .045       0  3252.1     .05       0  3968.6     .12       0
  4019.8     .05       0  4493.3     .07       0  4590.7     .05       0
  4841.4      .1       0  4933.7     .05       0    4995      .1       0
  5147.4     .07       0
Bank Sta=4933.7,4995
XS Rating Curve= 0 ,0
Exp/Cntr=0.3,0.1

Type RM Length L Ch R = 1 ,50630   ,714,714,714
BEGIN DESCRIPTION:
CLEAR CREEK 54.0
END DESCRIPTION:
XS GIS Cut Line= 3
      2453420.12     13593099.41        2453875.       13590825.
        2453775.     13589825.04
#Sta/Elev= 30
  2680.6  246.14  3082.8  247.45  3123.6  238.29  3164.4  238.48  3184.8  246.87
    3195  247.07  3215.4  242.79  3235.8  244.95  3579.4  240.69  3888.5  240.63
  4044.1  235.19  4153.6   236.1  4260.7  231.96  4602.3  232.98  4704.3  229.33
  4765.5  233.57  4906.3  227.49  4959.3  226.69  4966.8  219.22  4968.3  218.22
  5028.2  219.22  5047.8  227.33  5123.3  236.02  5180.9  238.09    5201  235.16
  5241.2  239.39  5332.3  239.97  5530.9  242.05  5630.2  243.94    6005  255.37
#Mann= 11 ,-1 , 0
  2680.6    .045       0  3579.4     .05       0  4044.1     .12       0
  4260.7     .05       0  4906.3    .035       0  4966.8    .035       0
  5028.2    .035       0  5123.3      .1       0  5332.3     .05       0
  5530.9     .07       0  5630.2     .05       0
Bank Sta=4966.8,5028.2
XS Rating Curve= 0 ,0
Exp/Cntr=0.3,0.1

Type RM Length L Ch R = 1 ,49916   ,701,701,701
BEGIN DESCRIPTION:
CLEAR CREEK 53.0
END DESCRIPTION:
XS GIS Cut Line= 3
      2453719.93     13593340.22        2454425.       13591225.
        2455425.       13590325.
#Sta/Elev= 30
  2770.6  247.72  3187.2  242.52  3344.2  243.24  3440.2  239.69  4106.2  236.83
  4483.7  235.77  4568.1  227.67  4715.2  227.38    4800  229.56  4852.7  228.39
  4863.2   225.7  4884.3  224.87  4979.2  227.95  4983.4  218.54  4984.9  217.54
  5044.8  218.54  5049.9  228.55  5078.3   230.3  5105.6  235.76  5276.4  233.84
    5345  229.46  5833.2  236.55  5874.4  238.07  6026.8  245.35  6140.4  254.99
  6267.5  257.81  6289.2  260.94  6303.4  265.66  6310.1  263.49  6345.6  265.15
#Mann= 10 ,-1 , 0
  2770.6    .045       0  3344.2     .07       0  4106.2     .12       0
  4715.2      .1       0  4983.4     .05       0  5044.8      .1       0
  5105.6     .12       0    5345      .1       0  5833.2     .12       0
  5874.4     .07       0
Bank Sta=4983.4,5044.8
XS Rating Curve= 0 ,0
Exp/Cntr=0.3,0.1

Type RM Length L Ch R = 1 ,49215   ,671,671,671
BEGIN DESCRIPTION:
CLEAR CREEK 52.0
END DESCRIPTION:
XS GIS Cut Line= 3
      2453725.02     13593674.97        2454925.       13591675.
        2455625.       13590675.
#Sta/Elev= 30
  2667.7  254.45  2775.5   254.3  2928.8  249.77  2982.5  250.79    3177  242.08
  3267.7  240.23  3362.4  238.93  4100.4  235.79    4304  235.49    4360  235.48
  4541.2  235.24  4618.2  235.24  4736.4  229.51  4849.4  226.07  4949.5  225.58
  4955.3  224.53  4955.7  217.74  4957.2  216.74  5017.1  217.74  5022.3  227.92
  5373.6   230.6  5550.3  224.89    5603  231.06  5700.8  232.36  5786.2  234.75
  5912.6  239.73  5992.9  244.22  6055.5  248.52  6091.2  259.44  6220.7  258.08
#Mann= 20 ,-1 , 0
  2667.7     .07       0  2775.5    .035       0  2928.8     .07       0
    3177     .05       0  3267.7     .12       0  3362.4     .07       0
  4100.4     .05       0    4304     .07       0    4360     .05       0
  4541.2     .05       0  4618.2     .07       0  4736.4     .12       0
  4849.4      .1       0  4955.7     .05       0  5017.1      .1       0
  5550.3     .07       0  5700.8     .07       0  5786.2     .12       0
  5912.6     .12       0  5992.9     .07       0
Bank Sta=4955.7,5017.1
XS Rating Curve= 0 ,0
Exp/Cntr=0.3,0.1

Type RM Length L Ch R = 1 ,48544   ,674,674,674
BEGIN DESCRIPTION:
CLEAR CREEK 51.0
END DESCRIPTION:
XS GIS Cut Line= 3
      2453924.99     13593675.01        2455525.       13591675.
      2456225.02     13590874.98
#Sta/Elev= 30
  2438.3   256.2  2886.5  240.06  3080.9  237.16    3866  235.99  3990.3  236.39
  4073.4  233.64  4153.6  232.89  4186.9  233.23  4304.4  233.97  4403.7  233.54
    4765  233.43  4793.9  228.08  4809.5  230.39  4813.6  229.51  4928.3  223.71
  4942.7  218.46  4961.7  217.61  4963.2  216.61  5023.1  217.61  5027.6  224.15
  5035.2  224.77  5077.9  225.35  5105.9  221.36  5169.9  225.78    5205  221.49
    5329  225.56  5445.7  227.64  5544.8   240.8  5609.4  237.62  6062.6  259.77
#Mann= 15 ,-1 , 0
  2438.3     .05       0  3080.9     .07       0    3866     .05       0
  3990.3     .12       0  4073.4     .05       0  4153.6     .12       0
  4186.9     .07       0  4304.4     .05       0  4403.7     .07       0
  4809.5     .12       0  4813.6      .1       0  4961.7     .05       0
  5023.1      .1       0    5329     .12       0  5445.7     .07       0
Bank Sta=4961.7,5023.1
XS Rating Curve= 0 ,0
Exp/Cntr=0.3,0.1

Type RM Length L Ch R = 1 ,47870   ,453,453,453
BEGIN DESCRIPTION:
CLEAR CREEK 50.0
END DESCRIPTION:
XS GIS Cut Line= 3
      2454125.01     13593624.99        2456125.       13591625.
        2456425.     13591225.01
#Sta/Elev= 30
  2176.6  251.32  2332.1  244.11  2487.7  239.83    2714  236.26  3053.6  234.96
  3248.5   234.4  3320.9  233.71  3517.6  233.18  3598.9  232.96  3944.3  233.82
  4156.5  231.92  4331.8  233.25  4495.9  231.35  4623.2  232.18    4708  228.26
  4750.4  228.66  4792.9  226.14  4877.3  224.45  4934.3  224.27  4938.9  217.55
  4940.4  216.55  5000.4  217.55  5001.5  222.93  5018.5  225.35  5033.1  234.21
  5062.3  238.46  5109.9  241.52  5147.7  243.11    5243  251.19    5505  269.82
#Mann= 12 ,-1 , 0
  2176.6     .05       0  3053.6     .07       0  3248.5     .05       0
  3320.9     .07       0  3517.6     .12       0  3598.9     .07       0
  4331.8     .12       0  4877.3      .1       0  4938.9     .05       0
  5000.4      .1       0  5109.9     .12       0    5243     .07       0
Bank Sta=4938.9,5000.4
XS Rating Curve= 0 ,0
Exp/Cntr=0.3,0.1

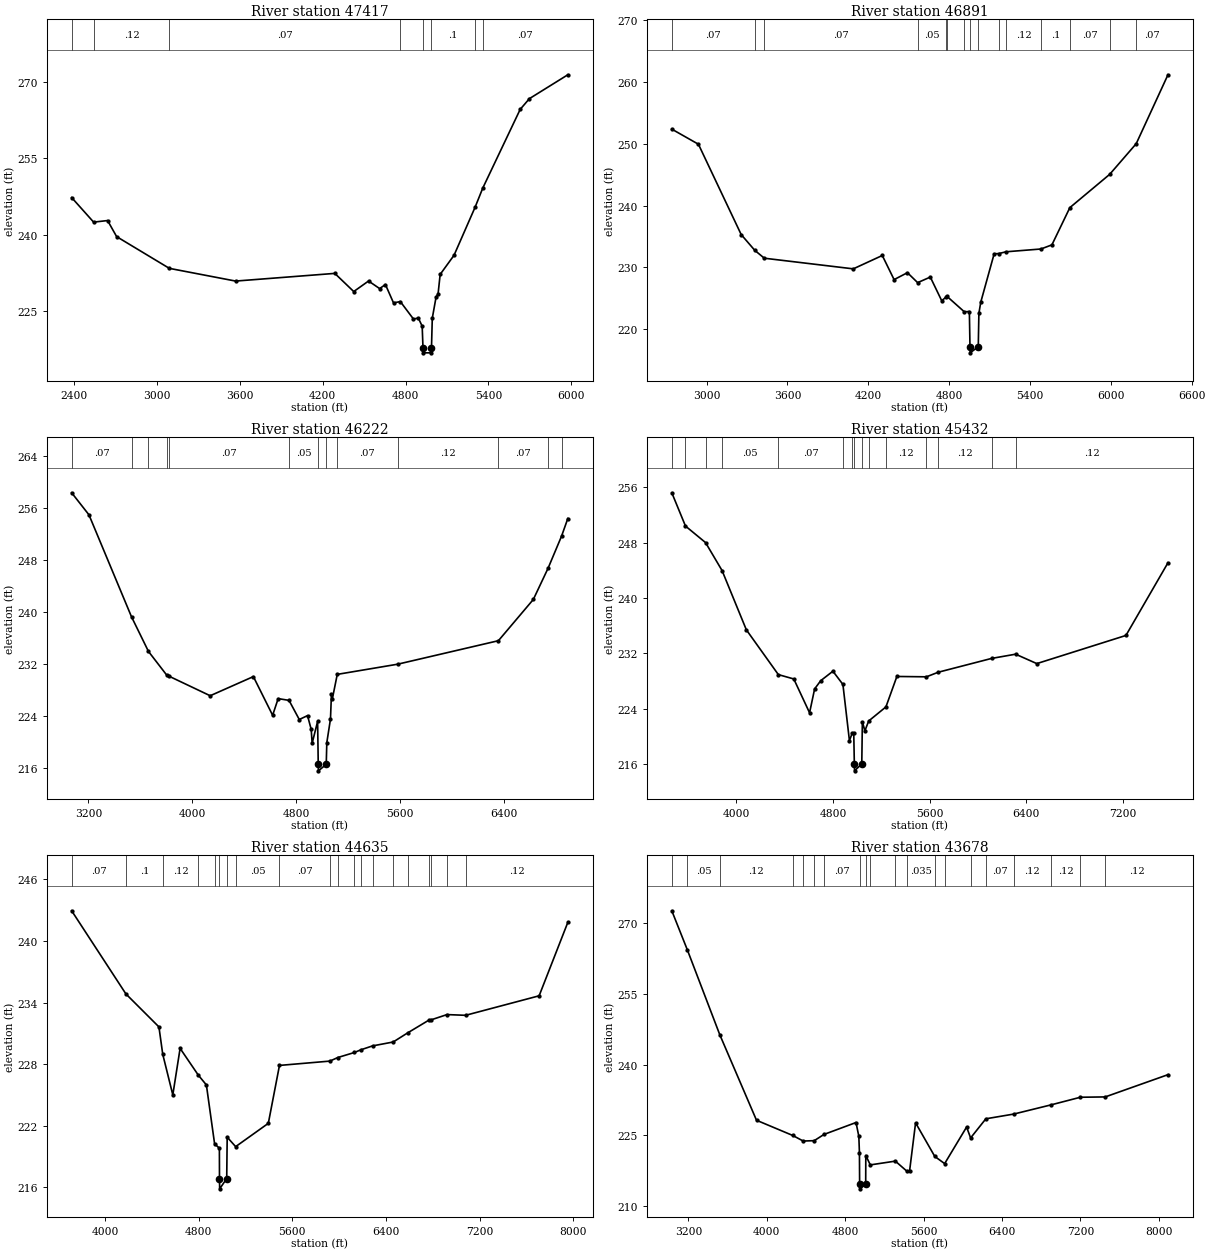
Type RM Length L Ch R = 1 ,47417   ,526,526,526
BEGIN DESCRIPTION:
X18463
END DESCRIPTION:
XS GIS Cut Line= 3
      2455001.36     13593993.62      2456563.87     13591758.37
        2456954.     13590988.95
#Sta/Elev= 30
  2384.1  247.31  2542.9  242.48  2644.1  242.79  2709.5  239.63  3090.9  233.39
  3570.3  230.89    4288   232.4    4425  228.83  4532.2   230.9  4612.5  229.41
  4654.3  230.21  4712.8   226.6  4762.1  226.86  4856.7  223.44  4892.4  223.61
  4920.2  222.03  4926.1  217.78  4927.6  216.78  4986.1  216.78  4987.6  217.78
  4993.4  223.59  5020.6  227.72  5035.4  228.39  5050.3   232.2  5150.7  235.96
  5302.9   245.4  5358.6  249.17  5629.4  264.65  5696.2  266.76    5974  271.45
#Mann= 8 ,-1 , 0
  2384.1     .05       0  2542.9     .12       0  3090.9     .07       0
  4762.1      .1       0  4926.1     .05       0  4987.6      .1       0
  5302.9     .12       0  5358.6     .07       0
Bank Sta=4926.1,4987.6
XS Rating Curve= 0 ,0
Exp/Cntr=0.3,0.1

Type RM Length L Ch R = 1 ,46891   ,669,669,669
BEGIN DESCRIPTION:
X18462
END DESCRIPTION:
XS GIS Cut Line= 4
      2455533.08     13594026.12      2456379.41     13592713.23
      2457182.36     13591910.28       2457529.2     13590988.99
#Sta/Elev= 30
  2742.1  252.35  2939.6  249.91  3257.1   235.3    3358  232.75  3428.7  231.48
  4088.8  229.76  4304.1  231.92  4391.7  228.02  4490.7  229.14  4566.5  227.53
  4660.4  228.43  4745.2   224.6  4780.4  225.26  4783.3  225.33  4912.7  222.82
  4950.3  222.86  4954.9  217.18  4956.4  216.18  5016.4  217.18    5021  222.57
  5035.2   224.4  5134.2  232.19  5168.1  232.23  5222.8  232.52  5481.3  232.97
  5562.9  233.64  5696.1  239.66  5991.6  245.04  6188.6     250  6424.1  261.14
#Mann= 15 ,-1 , 0
  2742.1     .07       0    3358     .12       0  3428.7     .07       0
  4566.5     .05       0  4780.4     .07       0  4783.3     .05       0
  4912.7      .1       0  4954.9     .05       0  5016.4      .1       0
  5168.1     .07       0  5222.8     .12       0  5481.3      .1       0
  5696.1     .07       0  5991.6    .035       0  6188.6     .07       0
Bank Sta=4954.9,5016.4
XS Rating Curve= 0 ,0
Exp/Cntr=0.3,0.1

Type RM Length L Ch R = 1 ,46222   ,790,790,790
BEGIN DESCRIPTION:
X18461
END DESCRIPTION:
XS GIS Cut Line= 3
      2455706.67     13594134.66      2457594.68     13592355.16
      2457648.92     13591129.52
#Sta/Elev= 30
  3070.6  258.29  3203.7  254.91  3531.5  239.25  3662.2  233.93  3801.1  230.34
  3823.7   230.1  4137.5  227.13    4470  230.07  4618.5  224.13    4661  226.69
  4744.6  226.42  4823.7  223.48  4887.2  224.08  4915.5  221.96  4922.8  219.83
  4964.9   223.2  4969.7   216.6  4971.2   215.6  5031.3   216.6  5035.7  219.93
    5064  223.56  5071.3  227.33  5078.1  226.63  5116.2  230.41  5580.9  231.97
  6357.4  235.58  6626.2  241.91  6739.7   246.7  6843.5  251.62  6891.9  254.34
#Mann= 13 ,-1 , 0
  3070.6     .07       0  3531.5     .12       0  3662.2     .07       0
  3801.1     .12       0  3823.7     .07       0  4744.6     .05       0
  4969.7     .05       0  5031.3     .05       0  5116.2     .07       0
  5580.9     .12       0  6357.4     .07       0  6739.7     .12       0
  6843.5     .07       0
Bank Sta=4969.7,5031.3
XS Rating Curve= 0 ,0
Exp/Cntr=0.3,0.1

Type RM Length L Ch R = 1 ,45432   ,797,797,797
BEGIN DESCRIPTION:
X18460
END DESCRIPTION:
XS GIS Cut Line= 3
      2455999.59     13594438.52       2457898.5     13593103.85
      2457714.04     13591324.32
#Sta/Elev= 30
    3465  255.22  3578.3  250.41  3744.6  248.02  3881.3  243.98  4082.6  235.41
  4347.5  228.94  4475.5  228.31  4606.2  223.42    4648  226.87  4698.6  228.06
  4799.6  229.43  4882.4  227.52  4936.4   219.4    4961  220.53  4972.2  220.51
  4977.1  216.03  4978.6  215.03  5038.7  216.03  5043.6  222.12  5064.5  220.82
  5096.2  222.24  5238.7  224.27  5329.5  228.67  5574.4  228.62  5671.5  229.28
  6114.4  231.28  6313.1  231.89  6488.6  230.53    7227   234.6  7575.1   245.1
#Mann= 15 ,-1 , 0
    3465     .07       0  3578.3     .05       0  3744.6     .07       0
  3881.3     .05       0  4347.5     .07       0  4882.4      .1       0
    4961     .12       0  4977.1     .05       0  5038.7     .12       0
  5096.2     .07       0  5238.7     .12       0  5574.4    .035       0
  5671.5     .12       0  6114.4     .07       0  6313.1     .12       0
Bank Sta=4977.1,5038.7
XS Rating Curve= 0 ,0
Exp/Cntr=0.3,0.1

Type RM Length L Ch R = 1 ,44635   ,957,957,957
BEGIN DESCRIPTION:
X18459
END DESCRIPTION:
XS GIS Cut Line= 4
      2456498.73     13594764.03      2457757.44     13594156.37
      2458072.11     13593635.54      2457789.99     13591421.97
#Sta/Elev= 30
  3715.8  242.94  4179.3  234.84  4461.2  231.63  4493.8  228.96  4579.7  225.01
    4642  229.54  4798.3  226.92  4866.5  225.98  4936.8  220.23  4977.5  219.82
  4978.4  216.86  4979.9  215.86  5040.1  216.86  5044.2  220.89  5116.5  219.97
  5395.5  222.24  5490.7  227.88  5921.1   228.3    5989  228.65  6131.2  229.14
  6185.6   229.4  6285.3  229.78  6461.8  230.16  6584.4  231.04  6766.9  232.29
  6783.8  232.31  6921.6  232.83  7080.4  232.76  7708.5  234.66  7953.5  241.81
#Mann= 20 ,-1 , 0
  3715.8     .07       0  4179.3      .1       0  4493.8     .12       0
  4798.3      .1       0  4936.8     .12       0  4978.4     .05       0
  5040.1     .12       0  5116.5     .05       0  5490.7     .07       0
  5921.1      .1       0    5989     .07       0  6131.2     .12       0
  6185.6    .035       0  6285.3     .12       0  6461.8     .07       0
  6584.4     .12       0  6766.9     .07       0  6783.8     .12       0
  6921.6     .07       0  7080.4     .12       0
Bank Sta=4978.4,5040.1
XS Rating Curve= 0 ,0
Exp/Cntr=0.3,0.1

Type RM Length L Ch R = 1 ,43678   ,1419,1419,1419
BEGIN DESCRIPTION:
CLEAR CREEK 49.0
END DESCRIPTION:
XS GIS Cut Line= 3
      2457574.99     13596375.03        2458375.       13594575.
      2457822.55     13591530.52
#Sta/Elev= 30
  3030.3  272.62  3189.6  264.29  3519.7  246.34  3894.8  228.18    4265  224.95
  4371.5  223.77  4483.7  223.85  4584.4  225.18  4910.5   227.7  4939.2  224.76
  4945.4  221.25  4947.3  214.63  4948.8  213.63  5009.2  214.63  5010.3   220.7
  5056.2  218.71  5311.8  219.51  5430.8  217.35  5457.4  217.46  5518.4  227.63
  5714.4   220.5  5815.1  218.98    6039  226.74  6080.1  224.43  6235.6  228.49
  6519.8  229.49  6902.2  231.45  7200.5  233.06  7453.8  233.13  8094.3  237.85
#Mann= 20 ,-1 , 0
  3030.3     .07       0  3189.6     .05       0  3519.7     .12       0
    4265     .07       0  4371.5     .12       0  4483.7     .12       0
  4584.4     .07       0  4947.3     .05       0  5009.2      .1       0
  5056.2     .05       0  5311.8    .035       0  5430.8    .035       0
  5714.4    .035       0  5815.1     .07       0  6080.1      .1       0
  6235.6     .07       0  6519.8     .12       0  6902.2     .12       0
  7200.5     .07       0  7453.8     .12       0
Bank Sta=4947.3,5009.2
XS Rating Curve= 0 ,0
Exp/Cntr=0.3,0.1

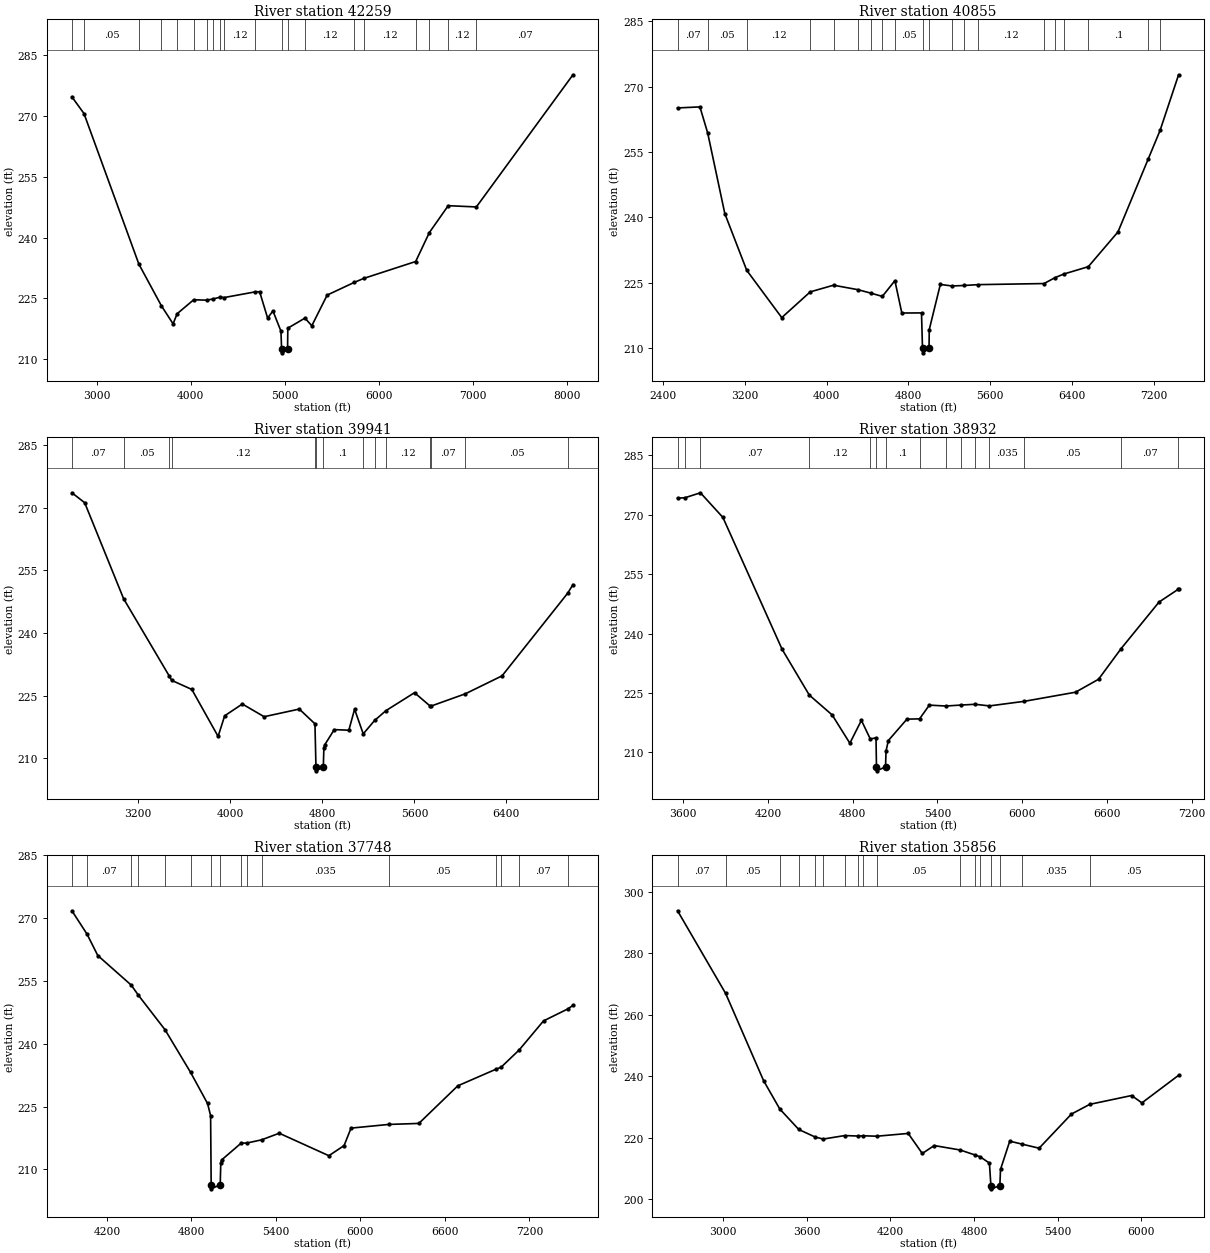
Type RM Length L Ch R = 1 ,42259   ,1404,1404,1404
BEGIN DESCRIPTION:
CLEAR CREEK 48.0
END DESCRIPTION:
XS GIS Cut Line= 3
      2457824.97     13596625.03        2459425.       13595025.
        2460025.       13592025.
#Sta/Elev= 30
  2737.2  274.76  2865.5  270.64  3448.5  233.46  3688.4  223.15    3812  218.72
  3854.7  221.21  4030.7  224.66  4169.5  224.57  4235.7  224.86  4312.7   225.3
  4355.4  225.21  4685.3  226.62  4731.3  226.64  4816.1  220.15  4872.7   221.9
  4957.6  216.91  4964.6  212.56  4966.1  211.56  5028.2  212.56  5030.6  217.65
  5212.5  220.13  5285.5  218.25  5448.7  225.82  5735.2  228.94  5835.1  229.92
  6388.9  234.11  6534.6  241.27  6734.4  247.89  7033.5  247.58  8059.4  280.21
#Mann= 20 ,-1 , 0
  2737.2     .07       0  2865.5     .05       0  3448.5     .12       0
  3688.4     .12       0  3854.7     .07       0  4030.7    .035       0
  4169.5     .12       0  4235.7    .035       0  4312.7     .07       0
  4355.4     .12       0  4685.3      .1       0  4964.6     .05       0
  5028.2      .1       0  5212.5     .12       0  5735.2    .035       0
  5835.1     .12       0  6388.9     .12       0  6534.6     .07       0
  6734.4     .12       0  7033.5     .07       0
Bank Sta=4964.6,5028.2
XS Rating Curve= 0 ,0
Exp/Cntr=0.3,0.1

Type RM Length L Ch R = 1 ,40855   ,914,914,914
BEGIN DESCRIPTION:
CLEAR CREEK 47.0
END DESCRIPTION:
XS GIS Cut Line= 3
      2457768.26      13596771.4        2460125.       13596075.
      2462260.24     13594894.35
#Sta/Elev= 30
  2542.9   265.1  2761.6  265.34  2837.7  259.33  3005.1  240.84    3219  227.84
  3561.4  216.98  3839.7  222.89  4067.5  224.42  4306.5  223.39  4432.9   222.6
  4544.4  221.85  4667.3  225.46  4735.1  218.04  4927.4  218.06  4937.2   209.9
  4938.7   208.9    5001   209.9  5003.2  214.23  5111.5   224.6  5226.3  224.24
  5346.3  224.36  5480.7  224.55  6125.7   224.8  6231.5  226.15  6319.3  226.99
  6557.7  228.67  6847.9  236.65  7145.1  253.48  7259.3  259.94  7440.3  272.71
#Mann= 20 ,-1 , 0
  2542.9     .07       0  2837.7     .05       0    3219     .12       0
  3839.7     .07       0  4067.5     .05       0  4306.5     .12       0
  4432.9     .07       0  4544.4     .12       0  4667.3     .05       0
  4937.2     .05       0    5001     .05       0  5226.3     .12       0
  5346.3      .1       0  5480.7     .12       0  6125.7      .1       0
  6231.5     .05       0  6319.3     .12       0  6557.7      .1       0
  7145.1    .035       0  7259.3     .07       0
Bank Sta=4937.2,5001
XS Rating Curve= 0 ,0
Exp/Cntr=0.3,0.1

Type RM Length L Ch R = 1 ,39941   ,1009,1009,1009
BEGIN DESCRIPTION:
X18458
END DESCRIPTION:
XS GIS Cut Line= 3
      2457768.25     13597596.06      2460036.09     13596847.34
      2462000.06     13596738.84
#Sta/Elev= 30
    2623  273.57  2734.1  271.19  3072.4   248.2    3471  229.61  3490.7  228.65
  3665.2  226.48  3893.8  215.24  3950.9  220.17  4104.4  222.99    4294  219.95
  4599.4  221.78  4735.6  218.25  4744.4  207.99  4745.9  206.99  4808.3  207.99
  4813.3  212.54  4820.5  213.21  4903.3  216.86  5030.2  216.72  5080.2  221.74
  5155.3  215.84    5254  219.05  5352.6   221.4    5601   225.7  5735.5  222.53
  5747.3  222.52  6043.4  225.44  6362.2  229.74  6931.4  249.49  6978.2  251.56
#Mann= 14 ,-1 , 0
    2623     .07       0  3072.4     .05       0    3471    .035       0
  3490.7     .12       0  4735.6      .1       0  4744.4     .05       0
  4808.3      .1       0  5155.3     .12       0    5254     .07       0
  5352.6     .12       0  5735.5     .05       0  5747.3     .07       0
  6043.4     .05       0  6931.4    .035       0
Bank Sta=4744.4,4808.3
XS Rating Curve= 0 ,0
Exp/Cntr=0.3,0.1

Type RM Length L Ch R = 1 ,38932   ,1184,1184,1184
BEGIN DESCRIPTION:
X18457
END DESCRIPTION:
XS GIS Cut Line= 3
      2458560.39     13598474.95      2459873.33      13597758.8
      2461815.59     13597096.91
#Sta/Elev= 30
  3559.7  274.16  3613.1  274.29  3721.7  275.53  3880.7  269.31  4300.3     236
  4492.6  224.46  4654.4  219.45  4779.7  212.31  4861.3  218.08  4924.4  213.38
  4964.8  213.67  4968.2  206.34  4969.7  205.34  5032.2  206.34    5036  210.38
  5052.1  212.98  5183.8  218.39  5273.2  218.46  5342.3  221.93  5459.3   221.7
  5564.3  221.94  5667.1  222.14  5767.9  221.73  6013.3  222.88  6377.6  225.19
  6540.5  228.46    6699  236.14  6968.8  247.95  7104.2  251.16  7107.2  251.16
#Mann= 15 ,-1 , 0
  3559.7     .07       0  3613.1    .035       0  3721.7     .07       0
  4492.6     .12       0  4924.4      .1       0  4968.2     .05       0
  5032.2      .1       0  5273.2     .12       0  5459.3     .07       0
  5564.3    .035       0  5667.1     .05       0  5767.9    .035       0
  6013.3     .05       0    6699     .07       0  7104.2     .05       0
Bank Sta=4968.2,5032.2
XS Rating Curve= 0 ,0
Exp/Cntr=0.3,0.1

Type RM Length L Ch R = 1 ,37748   ,1892,1892,1892
BEGIN DESCRIPTION:
CLEAR CREEK 46.0
END DESCRIPTION:
XS GIS Cut Line= 3
      2459120.68     13599423.73      2460234.02     13598690.56
       2461890.8      13597206.1
#Sta/Elev= 30
  3951.3  271.78  4058.8   266.2    4135   261.1  4372.6  254.03  4423.8  251.59
  4612.7  243.36  4793.8   233.2  4914.4  225.76  4936.1  222.87  4940.2  206.38
  4941.7  205.38  5004.3  206.38  5008.4  211.51  5014.4  212.28  5153.9  216.32
  5191.2   216.3    5298  217.08  5423.4  218.66  5775.8  213.29  5883.9  215.71
  5933.2  219.88  6200.7  220.76  6414.7     221  6691.3  229.98    6966     234
  6998.6  234.42  7126.4  238.52  7299.8  245.48  7471.3  248.32  7508.9  249.19
#Mann= 16 ,-1 , 0
  3951.3    .035       0  4058.8     .07       0  4372.6    .035       0
  4423.8     .07       0  4612.7     .12       0  4793.8      .1       0
  4940.2     .05       0  5004.3      .1       0  5153.9    .035       0
  5191.2      .1       0    5298    .035       0  6200.7     .05       0
    6966     .07       0  6998.6     .05       0  7126.4     .07       0
  7471.3     .05       0
Bank Sta=4940.2,5004.3
XS Rating Curve= 0 ,0
Exp/Cntr=0.3,0.1

Type RM Length L Ch R = 1 ,35856   ,681,681,681
BEGIN DESCRIPTION:
CLEAR CREEK 45.0
END DESCRIPTION:
XS GIS Cut Line= 3
      2459374.97     13599925.02        2461375.       13598725.
      2461774.99     13597525.02
#Sta/Elev= 30
    2672   293.8  3017.2  266.94  3290.1  238.55    3406  229.37  3542.5  222.71
  3659.8  220.26  3717.6   219.6  3872.8  220.74  3970.3  220.58  4004.7  220.66
  4103.6  220.53    4328  221.43  4429.1  214.91  4514.6  217.49  4701.6  216.04
  4806.5  214.44  4843.9  213.85  4911.1  211.79  4921.8  204.42  4923.3  203.42
    4986  204.42  4990.8  209.74  5057.1  218.92  5142.7  217.98  5267.9  216.63
  5499.8  227.72  5631.3  230.88    5932  233.75  6005.8  231.36  6269.3  240.32
#Mann= 17 ,-1 , 0
    2672     .07       0  3017.2     .05       0    3406     .07       0
  3542.5     .05       0  3659.8      .1       0  3717.6     .05       0
  3872.8     .12       0  3970.3     .05       0  4004.7     .12       0
  4103.6     .05       0  4701.6     .07       0  4806.5     .05       0
  4843.9      .1       0  4921.8     .05       0    4986      .1       0
  5142.7    .035       0  5631.3     .05       0
Bank Sta=4921.8,4986
XS Rating Curve= 0 ,0
Exp/Cntr=0.3,0.1

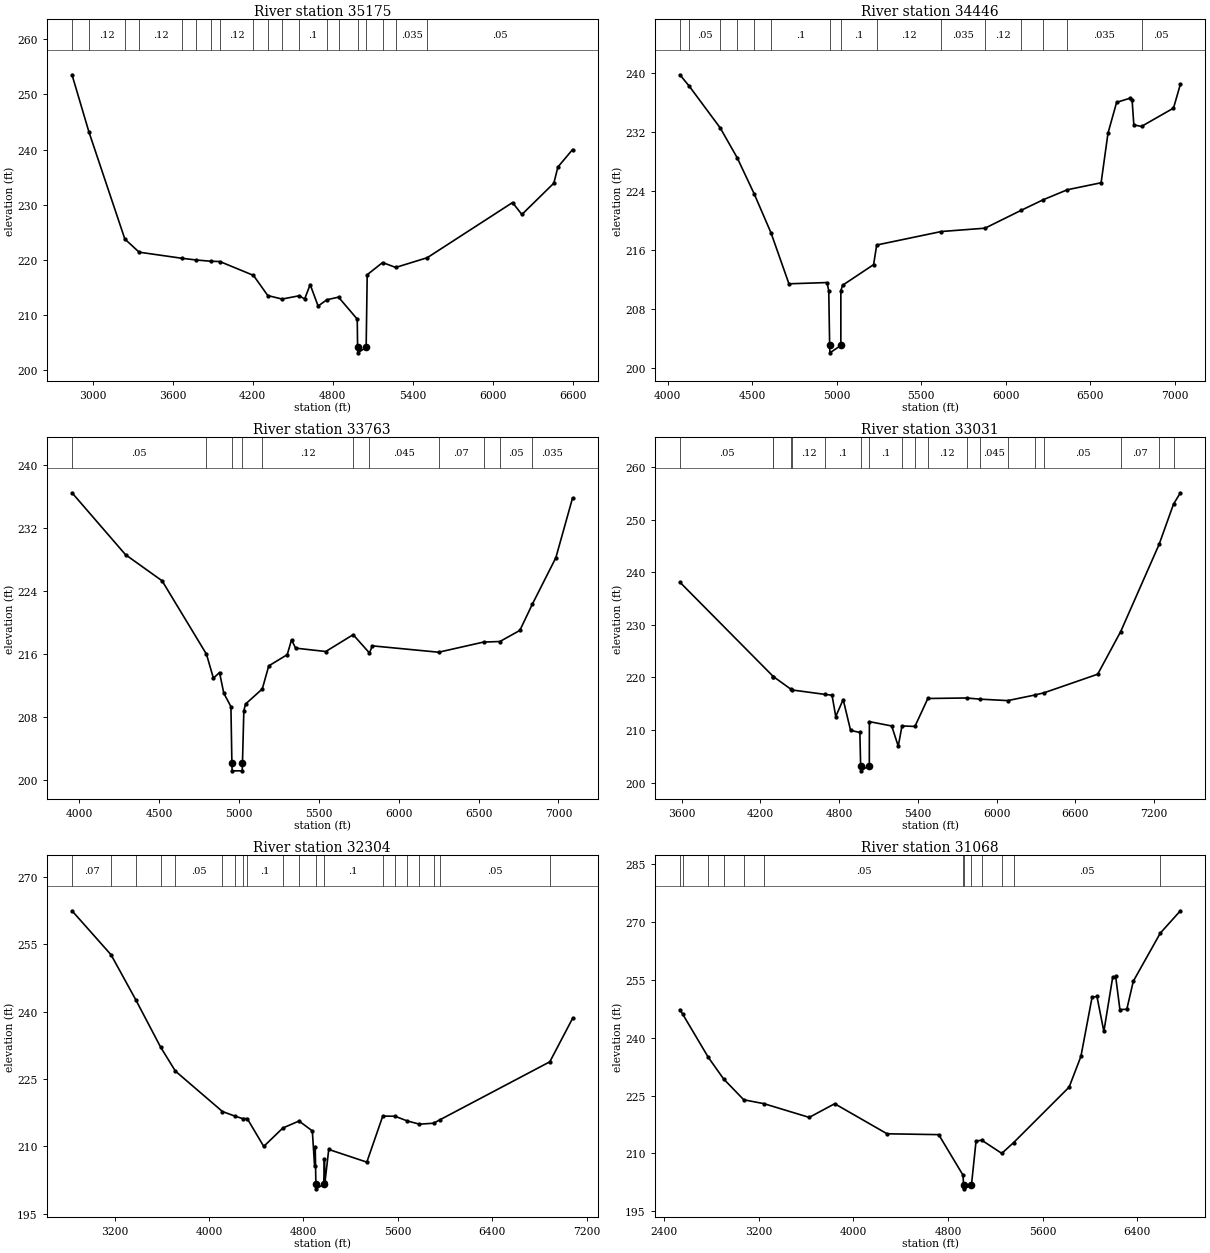
Type RM Length L Ch R = 1 ,35175   ,729,729,729
BEGIN DESCRIPTION:
CLEAR CREEK 44.0
END DESCRIPTION:
XS GIS Cut Line= 3
      2459824.99       13599975.        2461825.       13599175.
        2461825.     13597574.97
#Sta/Elev= 30
  2845.9  253.57  2972.4  243.23  3242.3  223.75  3349.5  221.37    3671  220.26
  3778.2  219.95  3885.4  219.73    3955  219.67  4206.9  217.16  4314.1   213.5
  4421.2  212.86  4550.3  213.46  4590.7  212.87  4632.4  215.49  4691.7  211.59
  4757.1  212.73  4844.7  213.21  4985.2  209.22  4987.9   204.1  4989.4   203.1
  5052.1   204.1    5060  217.28  5175.4  219.49  5273.9   218.6  5510.6  220.37
    6150  230.38    6220  228.21    6460   233.9    6490  236.82    6600  239.99
#Mann= 19 ,-1 , 0
  2845.9    .035       0  2972.4     .12       0  3242.3     .05       0
  3349.5     .12       0    3671     .07       0  3778.2     .12       0
  3885.4     .07       0    3955     .12       0  4206.9     .05       0
  4314.1     .12       0  4421.2     .05       0  4550.3      .1       0
  4757.1     .05       0  4844.7      .1       0  4987.9     .05       0
  5052.1      .1       0  5175.4     .12       0  5273.9    .035       0
  5510.6     .05       0
Bank Sta=4987.9,5052.1
XS Rating Curve= 0 ,0
Exp/Cntr=0.3,0.1

Type RM Length L Ch R = 1 ,34446   ,683,683,683
BEGIN DESCRIPTION:
CLEAR CREEK 43.0
END DESCRIPTION:
XS GIS Cut Line= 3
        2462175.     13600525.02        2462375.       13599625.
        2461975.     13597624.99
#Sta/Elev= 30
  4073.1  239.78  4126.9  238.29  4311.8  232.58  4412.1  228.54  4512.4  223.66
  4612.7  218.33  4718.5  211.44  4943.9  211.61  4954.1  210.48  4959.4  203.08
  4960.9  202.08  5025.6  203.08  5025.7  210.51  5035.9  211.24  5219.4  214.04
  5237.8   216.7  5620.4  218.53  5878.6  218.98  6094.1  221.42  6222.6  222.83
  6365.6  224.19  6565.6  225.14  6606.4  231.87  6657.4  236.04  6738.9  236.62
  6749.1  236.32  6759.3  232.98  6804.6  232.78  6993.9  235.26  7034.7   238.5
#Mann= 15 ,-1 , 0
  4073.1     .12       0  4126.9     .05       0  4311.8     .12       0
  4412.1    .035       0  4512.4     .12       0  4612.7      .1       0
  4959.4     .05       0  5025.6      .1       0  5237.8     .12       0
  5620.4    .035       0  5878.6     .12       0  6094.1    .035       0
  6222.6     .05       0  6365.6    .035       0  6804.6     .05       0
Bank Sta=4959.4,5025.6
XS Rating Curve= 0 ,0
Exp/Cntr=0.3,0.1

Type RM Length L Ch R = 1 ,33763   ,732,732,732
BEGIN DESCRIPTION:
CLEAR CREEK 42.0
END DESCRIPTION:
XS GIS Cut Line= 3
      2462725.01     13600724.97        2463025.       13599725.
      2463625.01     13597724.96
#Sta/Elev= 30
    3956   236.5  4290.9  228.63  4519.7  225.31  4797.4  215.98  4840.8  212.93
  4879.1  213.65    4906  211.01  4950.4  209.32  4956.5  202.15    4958  201.15
  5021.2  201.15  5022.7  202.15  5031.3  208.79  5041.8  209.64  5146.7  211.56
  5187.1  214.49  5302.8  215.92  5329.7  217.81    5355  216.75  5543.8  216.32
  5715.4  218.46  5817.4  216.13  5835.2  217.04  6250.3  216.23  6531.4  217.52
  6633.4  217.59  6758.3     219  6837.4  222.37  6983.7  228.24  7088.1  235.83
#Mann= 11 ,-1 , 0
    3956     .05       0  4797.4      .1       0  4956.5     .05       0
  5022.7      .1       0  5146.7     .12       0  5715.4    .035       0
  5817.4    .045       0  6250.3     .07       0  6531.4    .035       0
  6633.4     .05       0  6837.4    .035       0
Bank Sta=4956.5,5022.7
XS Rating Curve= 0 ,0
Exp/Cntr=0.3,0.1

Type RM Length L Ch R = 1 ,33031   ,727,727,727
BEGIN DESCRIPTION:
CLEAR CREEK 41.0
END DESCRIPTION:
XS GIS Cut Line= 3
      2462725.03     13600824.97        2463725.       13599825.
        2463725.     13597424.98
#Sta/Elev= 30
  3586.4   238.1  4298.9  220.15  4299.6  220.14  4435.1  217.71  4441.7  217.61
    4692  216.77    4746  216.61  4774.3  212.56  4830.9  215.79  4887.4  209.93
  4958.1  209.53  4963.9  203.24  4965.4  202.24  5030.1  203.24  5030.6  211.59
  5200.6  210.77  5250.6  206.93  5279.1  210.77  5377.6  210.68  5476.1  215.99
  5771.7  216.09  5870.3  215.87  6084.9  215.59  6290.8  216.65  6362.4  217.08
  6770.6  220.61  6945.8  228.72  7238.2  245.27  7348.3  252.94  7400.6  255.09
#Mann= 19 ,-1 , 0
  3586.4     .05       0  4298.9    .035       0  4299.6     .12       0
  4435.1    .035       0  4441.7     .12       0    4692      .1       0
  4963.9     .05       0  5030.1      .1       0  5279.1     .07       0
  5377.6    .035       0  5476.1     .12       0  5771.7    .035       0
  5870.3    .045       0  6084.9     .05       0  6290.8    .035       0
  6362.4     .05       0  6945.8     .07       0  7238.2    .035       0
  7348.3     .07       0
Bank Sta=4963.9,5030.1
XS Rating Curve= 0 ,0
Exp/Cntr=0.3,0.1

Type RM Length L Ch R = 1 ,32304   ,1236,1236,1236
BEGIN DESCRIPTION:
CLEAR CREEK 40.0
END DESCRIPTION:
XS GIS Cut Line= 3
      2463575.01     13601724.98        2464375.       13599725.
        2463775.     13597725.01
#Sta/Elev= 30
  2838.4  262.48  3169.2  252.68    3379  242.64  3588.9  232.12  3714.3  226.76
  4113.5  217.75  4218.4  216.73  4284.7  216.17  4323.3  216.18  4463.4  209.97
  4625.7  214.08  4762.3  215.63  4875.3  213.43  4894.2  205.57  4899.6  209.95
  4905.4  201.52  4906.9  200.52  4971.7  201.52  4977.6  207.06    4983  202.14
  5014.2   209.3    5337  206.47  5472.1  216.73  5575.9   216.7  5679.7  215.65
  5783.4  214.93  5902.6  215.14  5959.7  215.95    6888  228.83  7080.5  238.48
#Mann= 20 ,-1 , 0
  2838.4     .07       0  3169.2    .035       0    3379     .07       0
  3588.9     .12       0  3714.3     .05       0  4113.5     .07       0
  4218.4      .1       0  4284.7     .07       0  4323.3      .1       0
  4625.7     .05       0  4762.3      .1       0  4905.4     .05       0
  4971.7      .1       0  5472.1     .05       0  5575.9     .12       0
  5679.7    .035       0  5783.4     .05       0  5902.6    .045       0
  5959.7     .05       0    6888     .07       0
Bank Sta=4905.4,4971.7
XS Rating Curve= 0 ,0
Exp/Cntr=0.3,0.1

Type RM Length L Ch R = 1 ,31068   ,864,864,864
BEGIN DESCRIPTION:
CLEAR CREEK 39.0
END DESCRIPTION:
XS GIS Cut Line= 3
        2463875.       13601325.      2465386.74     13599267.61
      2465732.98     13597624.67
#Sta/Elev= 30
  2532.4  247.27  2556.2  246.11  2772.7  234.91  2901.9  229.31  3072.7  223.89
  3242.4  222.89  3626.2  219.32  3841.4  222.87  4284.3  215.07    4721  214.85
  4926.5  204.34  4931.4  201.79  4932.9  200.79  4997.9  201.79  5036.6  213.17
  5084.6  213.41  5254.4  209.99  5354.5  212.79  5823.8  227.18  5923.4  235.14
  6017.8   250.5    6059  250.69  6117.4  241.62  6191.9  255.64    6217  255.89
  6253.2   247.3  6311.5  247.37  6366.4  254.65  6594.5  267.12  6764.5  272.92
#Mann= 13 ,-1 , 0
  2532.4     .07       0  2556.2    .035       0  2772.7     .07       0
  2901.9     .05       0  3072.7     .07       0  3242.4     .05       0
  4926.5      .1       0  4931.4     .05       0  4997.9      .1       0
  5084.6     .05       0  5254.4    .035       0  5354.5     .05       0
  6594.5    .035       0
Bank Sta=4931.4,4997.9
XS Rating Curve= 0 ,0
Exp/Cntr=0.3,0.1

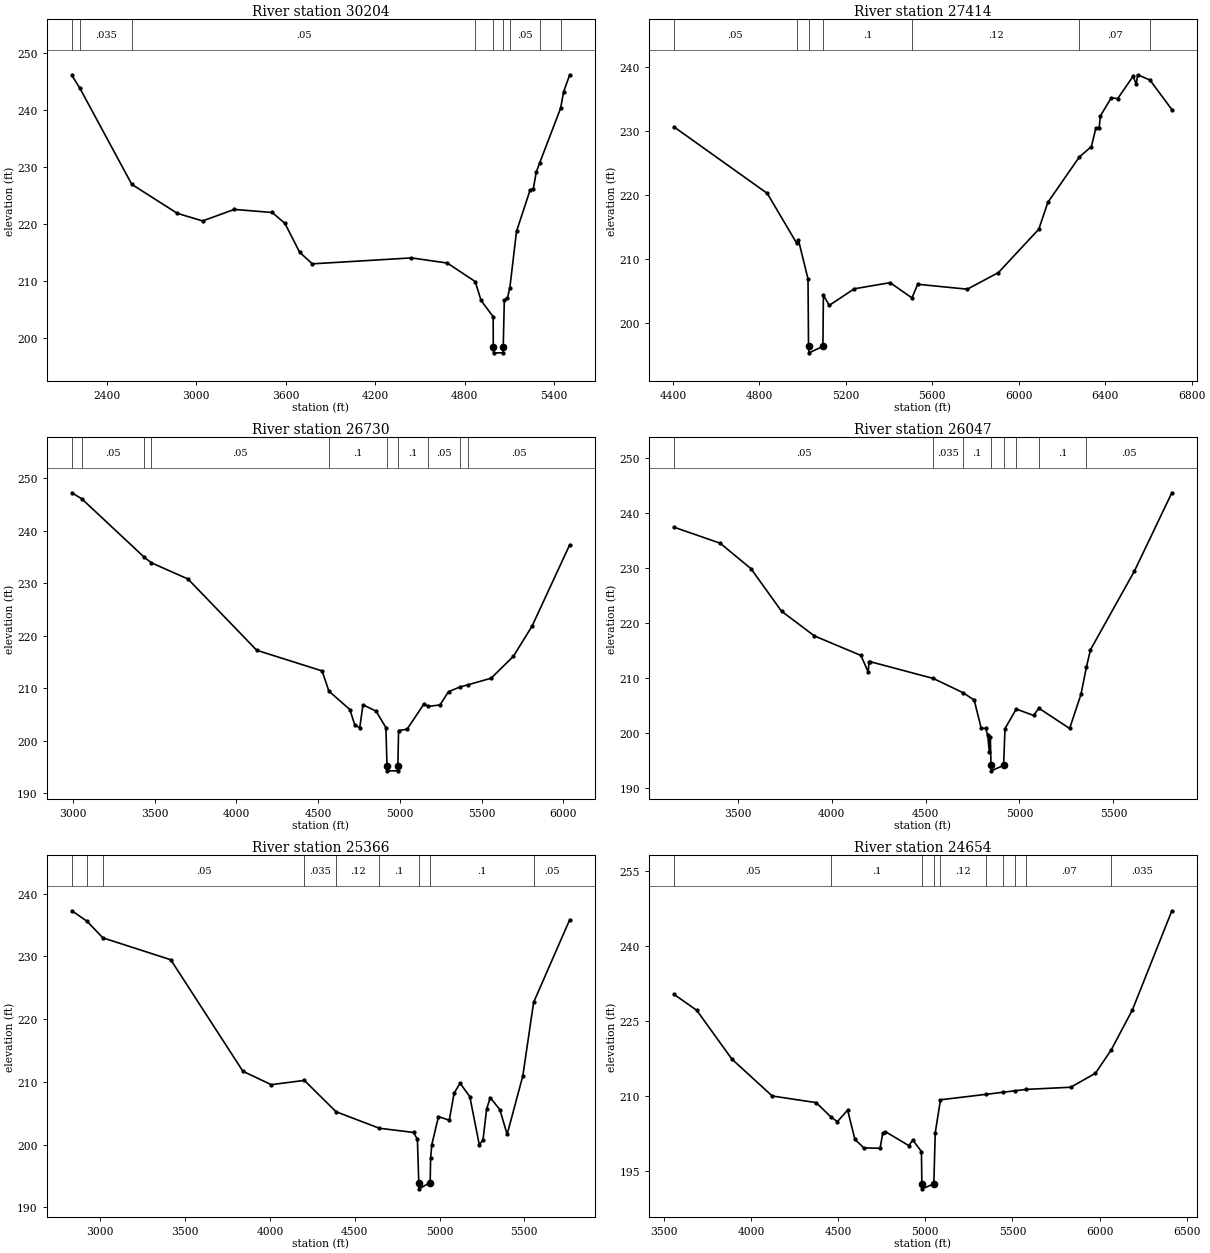
Type RM Length L Ch R = 1 ,30204   ,2790,2790,2790
BEGIN DESCRIPTION:
CLEAR CREEK 38.0
END DESCRIPTION:
XS GIS Cut Line= 3
      2464074.99     13601425.01        2466075.       13599425.
      2466174.99     13598925.05
#Sta/Elev= 30
  2167.2  246.08  2221.8  243.77  2568.7  226.97  2874.3  221.88    3044  220.55
  3256.2  222.57  3510.7  222.03  3595.6  220.13  3694.6  215.06  3779.4  213.03
  4444.1  214.07  4684.5  213.17  4871.8  209.92  4910.8  206.63  4992.1  203.75
    4993  198.43  4994.5  197.43    5058  197.43  5059.5  198.43    5067  206.74
  5087.4  206.99  5104.2  208.88  5148.6  218.71  5240.4  226.02  5260.8  226.13
  5281.2  229.12    5304  230.72  5444.2   240.3  5464.8  243.22  5505.5  246.17
#Mann= 9 ,-1 , 0
  2167.2     .07       0  2221.8    .035       0  2568.7     .05       0
  4871.8    .035       0    4993    .035       0  5059.5    .035       0
  5104.2     .05       0    5304    .035       0  5444.2     .05       0
Bank Sta=4993,5059.5
XS Rating Curve= 0 ,0
Exp/Cntr=0.3,0.1

Type RM Length L Ch R = 1 ,27414   ,684,684,684
BEGIN DESCRIPTION:
CLEAR CREEK 37.0
END DESCRIPTION:
XS GIS Cut Line= 3
      2465574.98     13601575.03        2465875.       13601075.
        2466875.       13599675.
#Sta/Elev= 30
  4404.8   230.7  4836.3  220.31  4971.8  212.55  4980.2  213.07  5024.8  206.93
  5027.2  196.38  5028.7  195.38  5093.7  196.38  5096.1  204.41  5123.1   202.8
  5238.6  205.39  5404.5  206.35  5505.9  203.97  5532.3   206.1  5762.1  205.33
  5905.9  207.93  6092.7  214.71  6134.5   218.9  6280.2     226    6336  227.62
  6356.9  230.52  6371.7  230.56  6377.8  232.42  6428.2  235.26  6457.7  235.12
    6529  238.62  6543.7  237.35  6549.9  238.85    6607  238.03  6708.4  233.41
#Mann= 7 ,-1 , 0
  4404.8     .05       0  4971.8      .1       0  5027.2     .05       0
  5093.7      .1       0  5505.9     .12       0  6280.2     .07       0
    6607     .05       0
Bank Sta=5027.2,5093.7
XS Rating Curve= 0 ,0
Exp/Cntr=0.3,0.1

Type RM Length L Ch R = 1 ,26730   ,683,683,683
BEGIN DESCRIPTION:
CLEAR CREEK 36.0
END DESCRIPTION:
XS GIS Cut Line= 3
        2466475.     13602975.02        2466475.       13600975.
      2466774.99     13599975.04
#Sta/Elev= 30
  2994.3   247.2  3055.6  246.03  3435.9  234.96  3481.1  233.86  3704.3  230.78
  4124.3  217.22  4524.3  213.28  4565.6  209.44  4694.3  205.92  4724.3  202.96
  4754.3  202.46  4774.3  206.84  4854.3  205.62  4914.3  202.49  4921.1  195.26
  4922.6  194.26  4986.1  194.26  4987.6  195.26  4991.8  201.93  5043.9  202.19
  5148.3  207.05  5172.1  206.53  5244.9   206.8  5297.1  209.33  5365.7  210.21
  5414.2  210.62  5558.1   211.9  5693.8  216.07  5807.8   221.8  6038.3   237.3
#Mann= 10 ,-1 , 0
  2994.3     .07       0  3055.6     .05       0  3435.9    .035       0
  3481.1     .05       0  4565.6      .1       0  4921.1     .05       0
  4987.6      .1       0  5172.1     .05       0  5365.7     .12       0
  5414.2     .05       0
Bank Sta=4921.1,4987.6
XS Rating Curve= 0 ,0
Exp/Cntr=0.3,0.1

Type RM Length L Ch R = 1 ,26047   ,681,681,681
BEGIN DESCRIPTION:
CLEAR CREEK 35.0
END DESCRIPTION:
XS GIS Cut Line= 3
      2466575.01     13602524.97        2466975.       13600725.
        2466875.       13599925.
#Sta/Elev= 30
  3161.1  237.49  3406.9  234.58  3570.8  229.95  3733.4  222.22  3908.9  217.72
    4156  214.18  4194.4   211.2  4199.5  213.04  4205.9  213.04  4541.6  209.99
  4700.4  207.39  4759.1  206.06  4796.3  200.95  4820.6   200.9  4830.8  199.67
  4839.8  196.58  4844.9  199.33  4848.5   194.2    4850   193.2  4915.5   194.2
    4923  200.89  4982.9  204.43  5075.5  203.27  5103.1  204.59    5267   200.9
  5327.5  207.12  5356.1  212.03  5377.9  215.21  5612.2  229.54  5811.2  243.75
#Mann= 8 ,-1 , 0
  3161.1     .05       0  4541.6    .035       0  4700.4      .1       0
  4848.5     .05       0  4915.5      .1       0  4982.9     .05       0
  5103.1      .1       0  5356.1     .05       0
Bank Sta=4848.5,4915.5
XS Rating Curve= 0 ,0
Exp/Cntr=0.3,0.1

Type RM Length L Ch R = 1 ,25366   ,712,712,712
BEGIN DESCRIPTION:
CLEAR CREEK 34.0
END DESCRIPTION:
XS GIS Cut Line= 3
      2466724.98     13602525.04        2467525.       13600525.
      2467025.02     13599925.03
#Sta/Elev= 30
  2832.6  237.25  2921.6  235.59  3015.1  232.94  3415.6  229.45    3841  211.69
    4008  209.56  4203.3  210.24  4389.8  205.25  4645.2  202.62  4846.7  201.95
  4869.6  200.87  4877.8  193.97  4879.3  192.97  4944.8  193.97  4947.7   197.9
  4954.4  199.98  4993.9  204.47  5057.7   203.9  5086.3  208.22  5121.4  209.79
  5178.7  207.65  5234.7  199.96  5256.8  200.81  5277.6  205.66  5299.1  207.49
  5355.7  205.59  5398.7  201.64  5491.1  210.95  5554.9  222.68  5767.7  235.83
#Mann= 9 ,-1 , 0
  2832.6     .05       0  2921.6    .035       0  3015.1     .05       0
  4203.3    .035       0  4389.8     .12       0  4645.2      .1       0
  4877.8     .05       0  4944.8      .1       0  5554.9     .05       0
Bank Sta=4877.8,4944.8
XS Rating Curve= 0 ,0
Exp/Cntr=0.3,0.1

Type RM Length L Ch R = 1 ,24654   ,752,752,752
BEGIN DESCRIPTION:
CLEAR CREEK 33.0
END DESCRIPTION:
XS GIS Cut Line= 3
      2467074.98     13602075.03        2467875.       13600875.
      2468875.02     13599874.98
#Sta/Elev= 30
  3557.9  230.31  3688.6  227.11  3889.9  217.36  4121.3  209.98  4373.7  208.65
  4459.2  205.75  4495.4  204.85    4554  207.15    4596  201.29  4647.1   199.6
  4740.3  199.52  4755.3  202.51  4770.3  202.85  4905.5  200.05    4928  201.18
  4977.6  198.86  4979.9  192.41  4981.4  191.41  5048.7  192.41  5056.7  202.63
  5086.9  209.22  5348.3  210.31  5444.7  210.72  5516.5  211.03  5580.2   211.3
  5834.5  211.73    5976  214.53  6066.2  219.18  6188.1  227.21  6414.4  247.02
#Mann= 10 ,-1 , 0
  3557.9     .05       0  4459.2      .1       0  4979.9     .05       0
  5048.7      .1       0  5086.9     .12       0  5348.3     .05       0
  5444.7    .035       0  5516.5     .05       0  5580.2     .07       0
  6066.2    .035       0
Bank Sta=4979.9,5048.7
XS Rating Curve= 0 ,0
Exp/Cntr=0.3,0.1