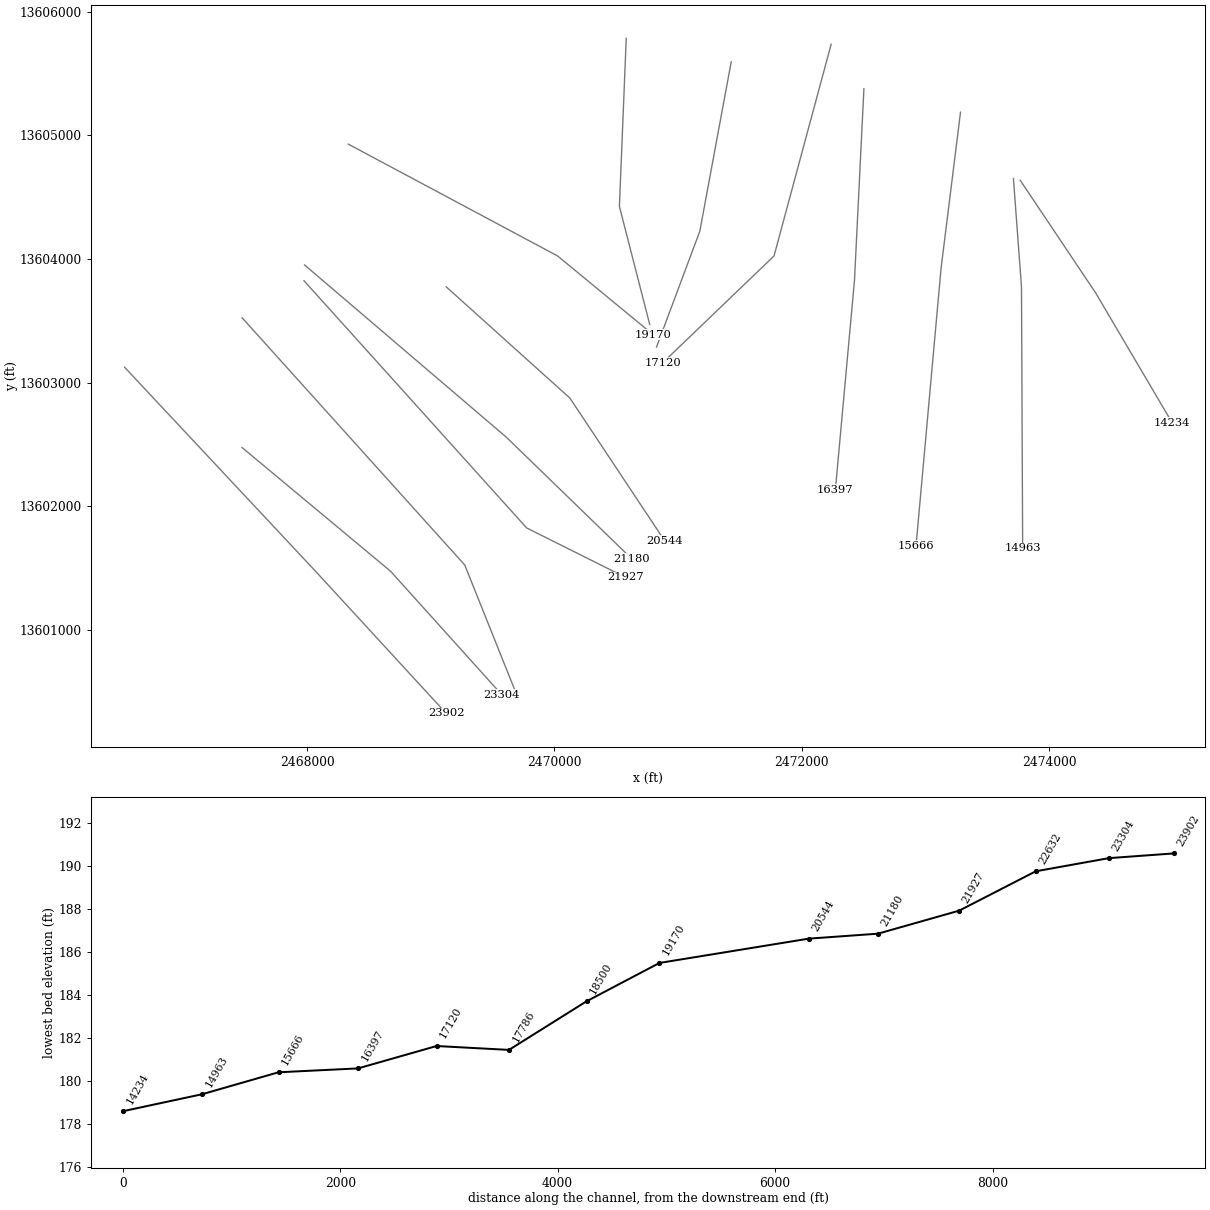
HEC-RAS study CLEAR CREEK.prj: CLEAR CREEK Base Level Engineering

--- CLEAR CREEK.g01 (geometry) --- (continued)

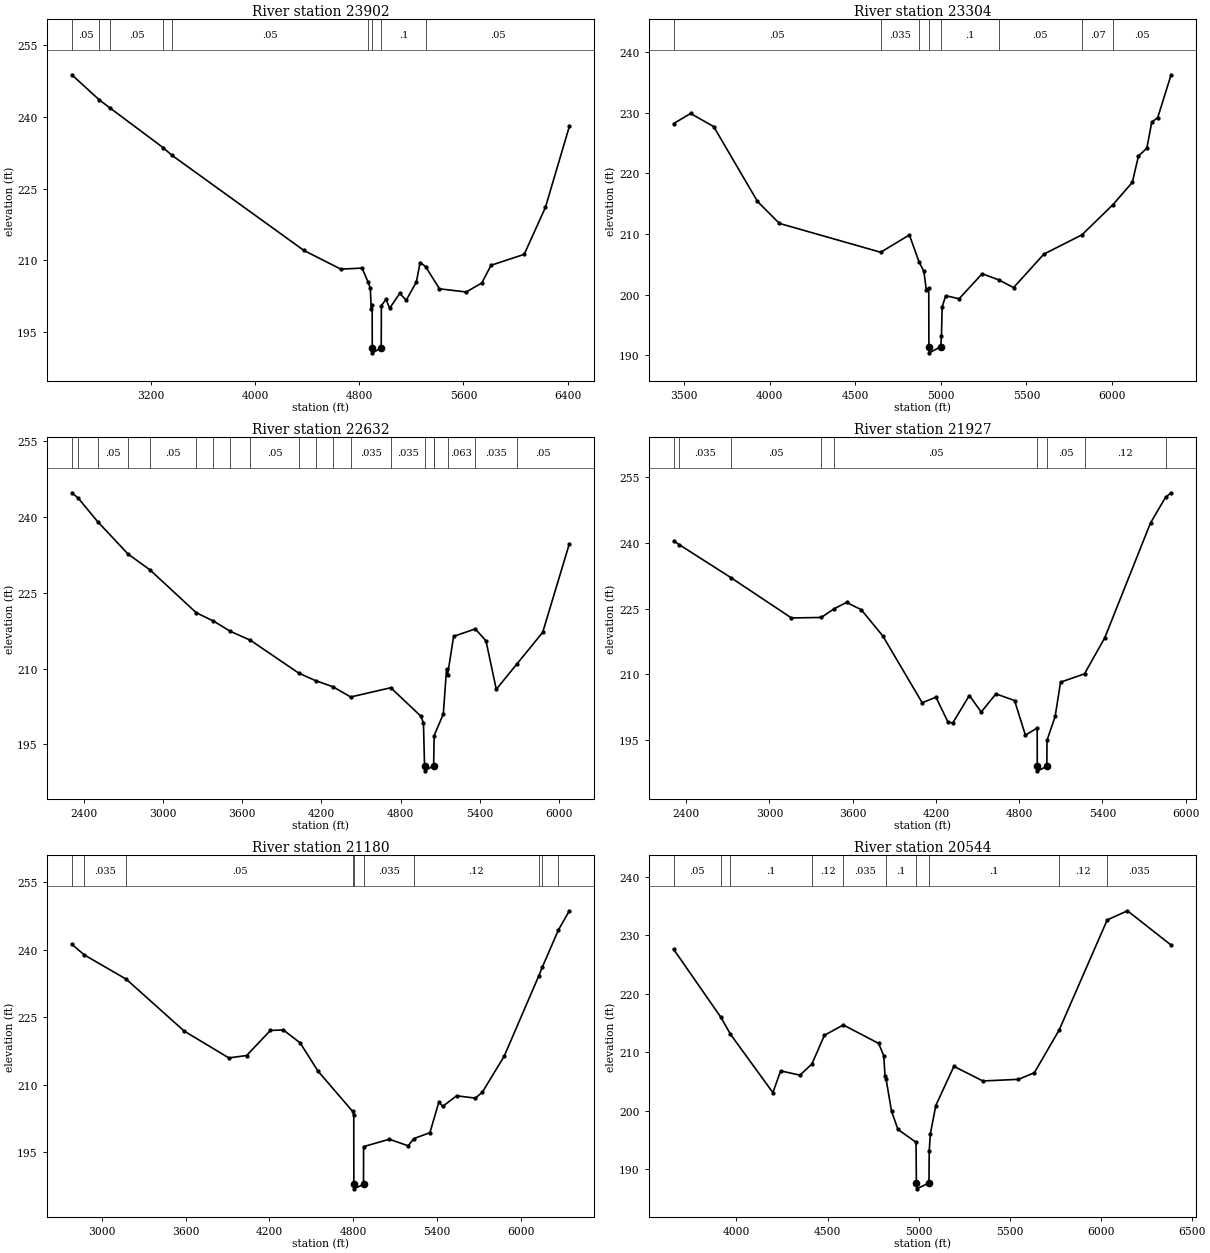
Type RM Length L Ch R = 1 ,23902   ,598,598,598
BEGIN DESCRIPTION:
CLEAR CREEK 32.0
END DESCRIPTION:
XS GIS Cut Line= 3
      2466525.02     13603124.97       2468081.9      13601460.4
        2469125.       13600325.
#Sta/Elev= 30
  2592.9  248.86  2805.1  243.56  2887.7  241.87    3295  233.57  3358.5  232.05
  4375.6  212.04  4658.9  208.13  4821.6  208.35  4866.4  205.53  4885.1  204.16
  4892.5  199.74  4899.3  200.71  4900.1  191.59  4901.6  190.59  4968.9  191.59
  4970.2  200.48  5005.4  201.78  5033.7  199.94  5111.4  203.04  5161.3  201.62
    5239  205.45  5267.4  209.51  5309.8  208.67    5416  204.01  5621.3  203.34
  5741.5  205.23  5812.4  208.94  6067.1  211.23  6229.9  221.06  6413.9  238.04
#Mann= 9 ,-1 , 0
  2592.9     .05       0  2805.1     .07       0  2887.7     .05       0
    3295    .035       0  3358.5     .05       0  4866.4      .1       0
  4900.1     .05       0  4968.9      .1       0  5309.8     .05       0
Bank Sta=4900.1,4968.9
XS Rating Curve= 0 ,0
Exp/Cntr=0.3,0.1

Type RM Length L Ch R = 1 ,23304   ,672,672,672
BEGIN DESCRIPTION:
CLEAR CREEK 31.0
END DESCRIPTION:
XS GIS Cut Line= 3
        2467475.       13602475.        2468675.       13601475.
      2469574.99     13600475.01
#Sta/Elev= 30
  3437.9  228.23  3537.5   229.9  3672.2  227.73    3928  215.38  4055.6  211.75
  4648.1  206.98  4815.8  209.84  4871.8  205.43  4900.4  203.83  4914.7  200.77
    4929   201.1  4929.8  191.37  4931.3  190.37  4998.6  191.37  5003.3  193.14
  5007.1  197.91    5028  199.81  5106.5   199.3    5241  203.43  5337.2  202.43
  5424.9  201.15    5602  206.68  5824.1  209.85  6005.6  214.85  6118.5  218.52
  6154.4  222.86  6203.7  224.18  6232.1  228.45  6267.2  229.23  6345.3  236.29
#Mann= 8 ,-1 , 0
  3437.9     .05       0  4648.1    .035       0  4871.8      .1       0
  4929.8     .05       0  4998.6      .1       0  5337.2     .05       0
  5824.1     .07       0  6005.6     .05       0
Bank Sta=4929.8,4998.6
XS Rating Curve= 0 ,0
Exp/Cntr=0.3,0.1

Type RM Length L Ch R = 1 ,22632   ,705,705,705
BEGIN DESCRIPTION:
CLEAR CREEK 30.0
END DESCRIPTION:
XS GIS Cut Line= 3
        2467475.       13603525.        2469275.       13601525.
      2469675.02     13600524.96
#Sta/Elev= 30
  2309.4   244.8  2357.9  243.73  2505.4  239.07  2734.8  232.68  2902.4  229.51
  3251.8  221.05  3381.1  219.42  3510.3  217.37  3661.7  215.61  4027.3  209.11
  4156.5   207.6  4285.8  206.42    4421  204.38  4724.7  206.21  4950.4  200.63
  4972.1   199.3  4980.5  190.76    4982  189.76  5049.4  190.76  5053.2  196.74
  5122.6  201.01  5146.9  209.87  5154.7  208.71  5200.7  216.38  5364.5  217.85
  5445.7   215.5  5523.8   205.9  5679.3  210.89  5875.2  217.17  6077.2  234.71
#Mann= 20 ,-1 , 0
  2309.4     .05       0  2357.9    .035       0  2505.4     .05       0
  2734.8    .035       0  2902.4     .05       0  3251.8    .035       0
  3381.1    .035       0  3510.3    .035       0  3661.7     .05       0
  4027.3    .035       0  4156.5    .035       0  4285.8    .035       0
    4421    .035       0  4724.7    .035       0  4980.5    .063       0
  5049.4    .063       0  5053.2    .035       0  5154.7    .063       0
  5364.5    .035       0  5679.3     .05       0
Bank Sta=4980.5,5049.4
XS Rating Curve= 0 ,0
Exp/Cntr=0.3,0.1

Type RM Length L Ch R = 1 ,21927   ,747,747,747
BEGIN DESCRIPTION:
CLEAR CREEK 29.0
END DESCRIPTION:
XS GIS Cut Line= 3
      2467975.02     13603824.98        2469775.       13601825.
      2470574.98     13601425.01
#Sta/Elev= 30
  2309.3  240.46  2351.1  239.58    2721  232.09  3158.7  222.85  3373.7  222.97
  3464.9  224.93  3555.6  226.41  3661.7  224.73  3817.2  218.73  4100.5  203.49
  4199.9  204.75  4285.1  199.17  4320.2  198.83  4440.5  205.14  4525.8  201.37
  4631.9  205.51  4766.4  203.99  4844.2  196.08  4929.4  197.72  4929.9  188.93
  4931.4  187.93    4999  188.93    5000  194.89  5058.7  200.35  5097.8  208.18
  5270.4  210.09  5416.5  218.34  5746.3  244.58    5854   250.4  5894.4  251.45
#Mann= 9 ,-1 , 0
  2309.3     .05       0  2351.1    .035       0    2721     .05       0
  3373.7    .035       0  3464.9     .05       0  4929.9     .05       0
    4999     .05       0  5270.4     .12       0    5854     .07       0
Bank Sta=4929.9,4999
XS Rating Curve= 0 ,0
Exp/Cntr=0.3,0.1

Type RM Length L Ch R = 1 ,21180   ,636,636,636
BEGIN DESCRIPTION:
CLEAR CREEK 28.0
END DESCRIPTION:
XS GIS Cut Line= 3
      2467980.09     13603951.89      2469609.39     13602560.19
      2470624.99     13601575.01
#Sta/Elev= 30
  2786.8  241.19  2875.2  238.84    3176  233.43  3589.6  221.92  3909.1  215.95
  4036.5  216.47  4206.6  222.05  4298.8  222.16  4419.6  219.28    4547  213.01
  4794.5  204.07  4802.8  203.21  4803.3  187.86  4804.8  186.86  4872.4  187.86
    4873  196.24  5057.4  197.88  5191.7  196.42  5232.6  198.02  5347.4  199.34
  5411.1  206.13  5439.2  205.18  5538.2  207.53  5672.7  207.01  5722.1  208.32
  5877.8  216.28  6125.8  234.17  6150.6  236.07  6266.8   244.4  6344.5  248.63
#Mann= 10 ,-1 , 0
  2786.8     .05       0  2875.2    .035       0    3176     .05       0
  4794.5    .035       0  4803.3     .05       0  4872.4    .035       0
  5232.6     .12       0  6125.8     .07       0  6150.6     .12       0
  6266.8     .07       0
Bank Sta=4803.3,4872.4
XS Rating Curve= 0 ,0
Exp/Cntr=0.3,0.1

Type RM Length L Ch R = 1 ,20544   ,1374,1374,1374
BEGIN DESCRIPTION:
CLEAR CREEK 27.0
END DESCRIPTION:
XS GIS Cut Line= 3
      2469124.98     13603775.02        2470125.       13602875.
      2470891.94     13601719.19
#Sta/Elev= 30
  3654.6  227.61  3914.3  215.97  3966.8  213.08  4199.9  203.09  4242.5  206.81
  4348.6  206.07  4414.3  207.99  4483.1   212.9  4586.5  214.66  4780.6  211.51
    4809   209.4  4815.7  205.91  4821.7  205.39  4851.6   199.9  4886.8  196.79
  4986.2   194.6    4988  187.63  4989.5  186.63  5057.1  187.63  5058.6  193.06
  5064.6     196  5094.7  200.88    5194  207.58  5353.3  205.08  5548.8  205.36
  5636.1  206.49  5772.4  213.81  6036.1  232.62  6147.3  234.19  6387.1  228.32
#Mann= 10 ,-1 , 0
  3654.6     .05       0  3914.3     .12       0  3966.8      .1       0
  4414.3     .12       0  4586.5    .035       0  4821.7      .1       0
    4988     .05       0  5057.1      .1       0  5772.4     .12       0
  6036.1    .035       0
Bank Sta=4988,5057.1
XS Rating Curve= 0 ,0
Exp/Cntr=0.3,0.1

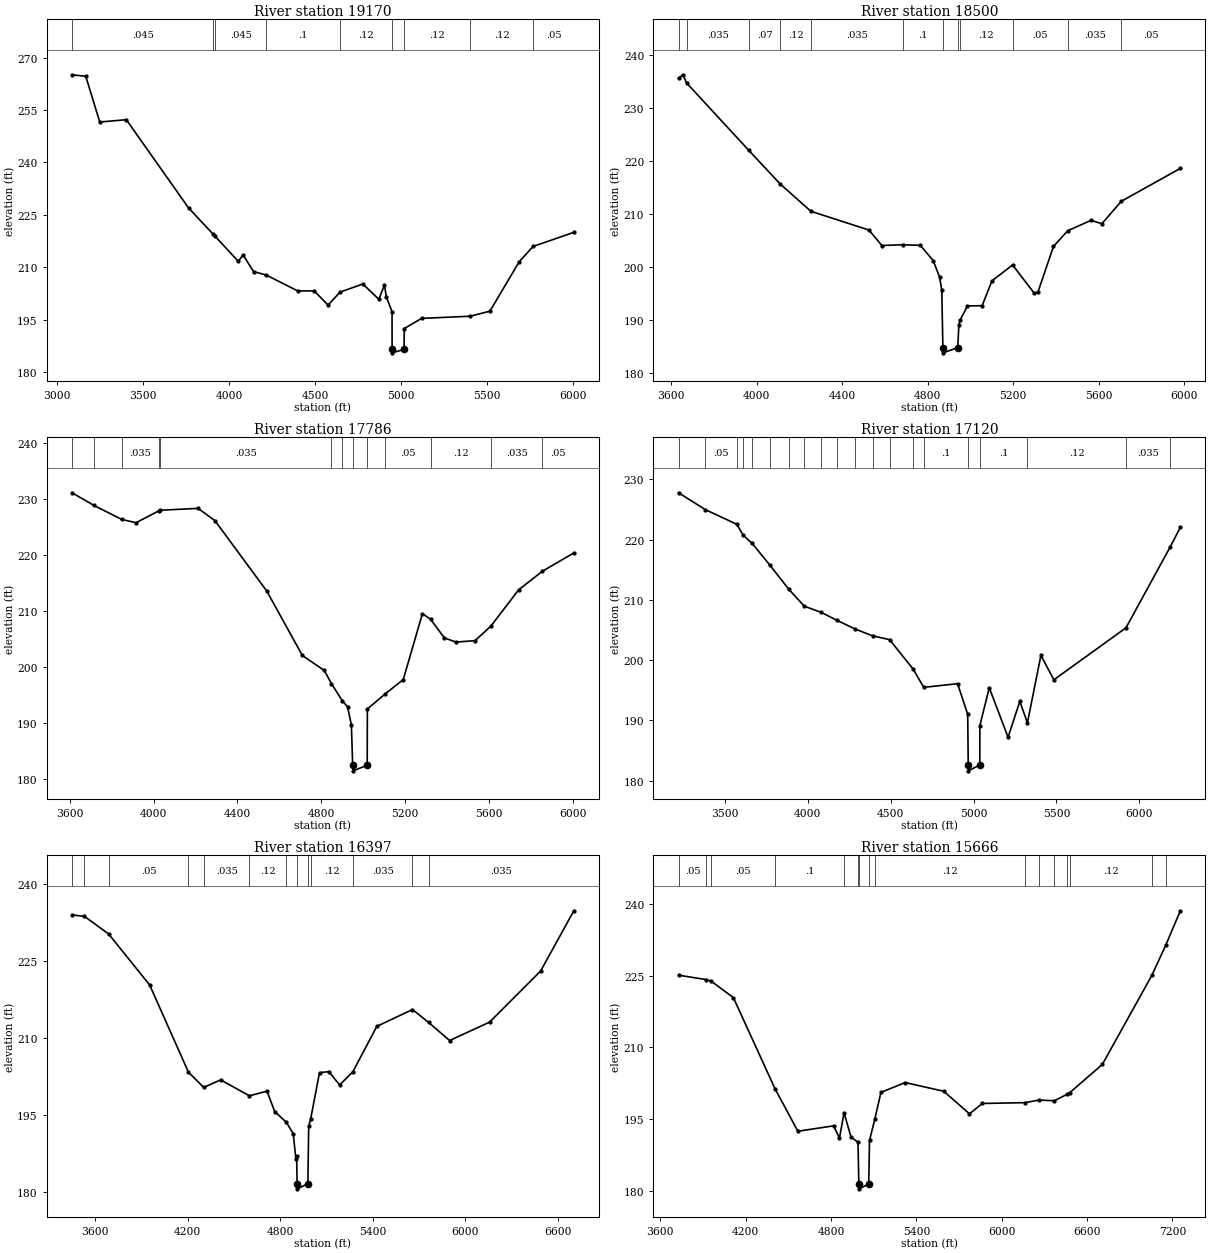
Type RM Length L Ch R = 1 ,19170   ,670,670,670
BEGIN DESCRIPTION:
CLEAR CREEK 26.0
END DESCRIPTION:
XS GIS Cut Line= 3
      2468333.12     13604929.48        2470025.       13604025.
       2470796.5      13603389.2
#Sta/Elev= 30
  3086.6  265.09  3166.4  264.65  3247.5  251.57  3402.1  252.23  3763.8     227
  3905.8  219.52  3918.5  218.86  4052.6  211.73  4081.7  213.51  4141.8  208.78
  4216.5  207.75  4399.5  203.21  4494.8  203.24  4575.1  199.17  4645.4  202.88
  4777.5   205.2  4870.9  200.83    4903  204.93  4914.8  201.43  4947.4   197.3
  4947.8   186.5  4949.3   185.5    5017   186.5  5018.7  192.46  5119.1  195.36
  5400.8  195.98  5516.5  197.42  5687.2  211.59  5767.3  215.94  6004.8  219.99
#Mann= 9 ,-1 , 0
  3086.6    .045       0  3905.8     .05       0  3918.5    .045       0
  4216.5      .1       0  4645.4     .12       0  4947.8     .05       0
    5017     .12       0  5400.8     .12       0  5767.3     .05       0
Bank Sta=4947.8,5017
XS Rating Curve= 0 ,0
Exp/Cntr=0.3,0.1

Type RM Length L Ch R = 1 ,18500   ,714,714,714
BEGIN DESCRIPTION:
CLEAR CREEK 25.0
END DESCRIPTION:
XS GIS Cut Line= 3
      2470580.19     13605784.84        2470525.       13604425.
      2470770.11     13603470.54
#Sta/Elev= 30
  3634.9  235.59  3654.8  236.26  3673.1  234.69  3963.6  221.97  4110.7  215.61
  4253.7  210.47  4525.5  206.92  4585.5     204  4682.4  204.15  4765.7  204.03
  4825.7  201.15  4855.7  198.03  4865.8  195.55  4871.1  184.72  4872.6  183.72
  4940.4  184.72  4945.8  188.91  4950.8  189.85  4985.9  192.57  5054.4  192.63
  5100.3  197.32    5197  200.32  5298.9  194.95  5315.9  195.25  5388.2  203.83
  5454.7  206.79  5563.7  208.75  5614.6  208.12  5705.5  212.36  5981.3  218.57
#Mann= 12 ,-1 , 0
  3634.9     .07       0  3673.1    .035       0  3963.6     .07       0
  4110.7     .12       0  4253.7    .035       0  4682.4      .1       0
  4871.1     .05       0  4940.4      .1       0  4950.8     .12       0
    5197     .05       0  5454.7    .035       0  5705.5     .05       0
Bank Sta=4871.1,4940.4
XS Rating Curve= 0 ,0
Exp/Cntr=0.3,0.1

Type RM Length L Ch R = 1 ,17786   ,666,666,666
BEGIN DESCRIPTION:
CLEAR CREEK 24.0
END DESCRIPTION:
XS GIS Cut Line= 3
       2471428.8     13605594.82        2471175.       13604225.
      2470825.23      13603288.3
#Sta/Elev= 30
  3611.2  231.09  3716.2  228.82  3847.6  226.34  3916.1  225.74  4025.5  227.88
  4029.8  227.97  4212.3  228.31  4292.4  226.12  4539.7  213.55  4709.4  202.05
  4814.2  199.37  4847.9  197.04  4900.7  193.93    4925   192.9  4943.3  189.63
  4949.3  182.46  4950.8  181.46  5018.7  182.46  5019.5   192.5    5105  195.21
  5190.6  197.75  5281.9  209.51  5320.7  208.52  5386.8  205.19    5442  204.44
  5532.9   204.7  5608.5  207.29  5740.9  213.77  5854.1  217.08  6004.2  220.36
#Mann= 13 ,-1 , 0
  3611.2    .035       0  3716.2     .05       0  3847.6    .035       0
  4025.5     .12       0  4029.8    .035       0  4847.9      .1       0
  4900.7     .12       0  4949.3     .05       0  5018.7     .12       0
    5105     .05       0  5320.7     .12       0  5608.5    .035       0
  5854.1     .05       0
Bank Sta=4949.3,5018.7
XS Rating Curve= 0 ,0
Exp/Cntr=0.3,0.1

Type RM Length L Ch R = 1 ,17120   ,723,723,723
BEGIN DESCRIPTION:
CLEAR CREEK 23.0
END DESCRIPTION:
XS GIS Cut Line= 3
      2472236.68      13605737.4        2471775.       13604025.
      2470873.39     13603158.84
#Sta/Elev= 30
  3222.4  227.77  3384.3  224.97  3574.4  222.53  3611.6  220.73  3665.3   219.4
  3774.5  215.71  3885.3  211.81  3980.2  208.95    4083  207.92  4175.4  206.63
  4288.7  205.14  4391.5  204.04  4494.3   203.4  4637.1  198.48    4700  195.49
  4903.9   196.1  4964.9  191.03  4968.2  182.64  4969.7  181.64  5037.8  182.64
  5038.3  189.15  5094.9  195.43  5208.1  187.21  5278.8  193.16  5324.9  189.61
  5406.2  200.82  5483.9  196.74  5918.8  205.37  6184.4  218.74  6246.2  222.02
#Mann= 20 ,-1 , 0
  3222.4     .05       0  3384.3     .05       0  3574.4     .07       0
  3611.6     .05       0  3665.3    .035       0  3774.5     .05       0
  3885.3     .07       0  3980.2     .07       0    4083     .05       0
  4175.4    .035       0  4288.7     .12       0  4391.5    .035       0
  4494.3     .12       0  4637.1    .035       0    4700      .1       0
  4968.2     .05       0  5037.8      .1       0  5324.9     .12       0
  5918.8    .035       0  6184.4     .12       0
Bank Sta=4968.2,5037.8
XS Rating Curve= 0 ,0
Exp/Cntr=0.3,0.1

Type RM Length L Ch R = 1 ,16397   ,731,731,731
BEGIN DESCRIPTION:
CLEAR CREEK 22.0
END DESCRIPTION:
XS GIS Cut Line= 3
      2472501.43     13605377.51        2472425.       13603825.
      2472270.61     13602132.52
#Sta/Elev= 30
  3450.3  233.91  3530.1  233.64    3687  230.22  3953.4  220.28    4205   203.3
  4303.8  200.34    4414  201.81  4600.1  198.71  4714.3  199.61  4764.4  195.64
    4840  193.55  4884.5  191.34  4901.3   186.5  4906.3  187.01  4909.8   181.6
  4911.3   180.6  4979.4   181.6  4984.7  192.76  4997.7  194.24  5054.8   203.2
  5115.1  203.42  5185.4  200.82  5270.8  203.37  5426.4  212.22  5657.8   215.5
  5761.8     213  5898.4  209.47  6157.5  213.04  6488.3  222.98  6704.2  234.72
#Mann= 13 ,-1 , 0
  3450.3     .12       0  3530.1     .07       0    3687     .05       0
    4205     .12       0  4303.8    .035       0  4600.1     .12       0
    4840      .1       0  4909.8     .05       0  4979.4      .1       0
  4997.7     .12       0  5270.8    .035       0  5657.8     .12       0
  5761.8    .035       0
Bank Sta=4909.8,4979.4
XS Rating Curve= 0 ,0
Exp/Cntr=0.3,0.1

Type RM Length L Ch R = 1 ,15666   ,703,703,703
BEGIN DESCRIPTION:
CLEAR CREEK 21.0
END DESCRIPTION:
XS GIS Cut Line= 3
      2473282.14     13605187.46        2473125.       13603925.
      2472922.44     13601678.81
#Sta/Elev= 30
  3727.9  225.07  3924.3  224.14  3958.2   223.8  4113.3  220.39  4405.5  201.38
  4566.8  192.46  4818.7  193.59    4859  190.98  4891.5  196.33  4939.6   191.3
  4989.5  190.13  4995.4  181.42  4996.9  180.42    5065  181.42  5070.4  190.53
  5108.2  195.04  5150.7  200.58  5321.4  202.63  5592.5  200.81  5773.2  196.09
  5863.6  198.26  6162.3  198.43  6261.5  198.97  6369.6  198.83  6457.7  200.15
  6478.7  200.54    6707  206.41    7055  225.02  7154.1  231.41  7255.4  238.53
#Mann= 16 ,-1 , 0
  3727.9     .05       0  3924.3    .035       0  3958.2     .05       0
  4405.5      .1       0  4891.5     .12       0  4989.5      .1       0
  4995.4     .05       0    5065      .1       0  5108.2     .12       0
  6162.3    .035       0  6261.5     .12       0  6369.6    .035       0
  6457.7     .07       0  6478.7     .12       0    7055     .07       0
  7154.1    .035       0
Bank Sta=4995.4,5065
XS Rating Curve= 0 ,0
Exp/Cntr=0.3,0.1

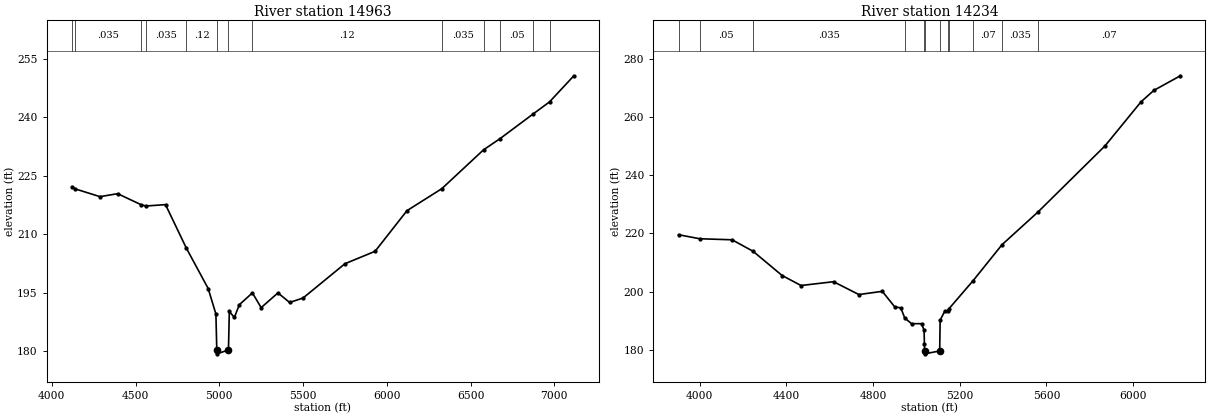
Type RM Length L Ch R = 1 ,14963   ,729,729,729
BEGIN DESCRIPTION:
CLEAR CREEK 20.0
END DESCRIPTION:
XS GIS Cut Line= 3
      2473709.84     13604651.15        2473775.       13603775.
      2473784.51     13601658.69
#Sta/Elev= 30
  4121.4  222.18  4140.8  221.65    4288  219.67  4393.2  220.43  4535.6  217.57
  4563.6  217.28  4679.1  217.63  4803.5  206.48  4933.7  196.14  4979.9  189.59
  4985.1   180.4  4986.6   179.4  5054.8   180.4    5060  190.25    5090  188.73
    5120     192  5197.7  195.01    5250  191.24    5350  195.01    5420  192.56
    5500   193.7    5750  202.49    5930  205.67    6120  216.07  6328.1  221.71
    6577  231.66  6675.5  234.53  6872.5  240.83    6971  243.95  7116.3  250.64
#Mann= 13 ,-1 , 0
  4121.4     .05       0  4140.8    .035       0  4535.6     .05       0
  4563.6    .035       0  4803.5     .12       0  4985.1     .05       0
  5054.8     .12       0  5197.7     .12       0  6328.1    .035       0
    6577     .12       0  6675.5     .05       0  6872.5     .07       0
    6971    .035       0
Bank Sta=4985.1,5054.8
XS Rating Curve= 0 ,0
Exp/Cntr=0.3,0.1

Type RM Length L Ch R = 1 ,14234   ,726,726,726
BEGIN DESCRIPTION:
CLEAR CREEK 19.0
END DESCRIPTION:
XS GIS Cut Line= 3
      2473764.14     13604637.59        2474375.       13603725.
      2474992.94     13602675.59
#Sta/Elev= 30
  3901.8  219.52  3999.4  218.14  4148.8  217.78  4245.5  213.85    4380  205.51
  4467.1  202.08  4617.2  203.38  4734.3  198.97  4842.3  200.08  4899.4  194.75
  4927.8  194.39  4945.8  190.91  4977.5  188.96  5023.2  188.97  5035.1  186.77
  5036.6  181.89  5037.3  179.61  5038.8  178.61  5107.1  179.61  5109.3  190.17
  5130.7  193.27  5143.9  193.21  5149.1  194.03  5261.6  203.76  5394.9   216.1
  5560.6  227.31  5870.3  250.04  6036.6  265.18  6095.2  269.07  6217.8  274.11
#Mann= 12 ,-1 , 0
  3901.8    .035       0  3999.4     .05       0  4245.5    .035       0
  4945.8     .12       0  5036.6      .1       0  5037.3     .05       0
  5107.1      .1       0  5143.9     .12       0  5149.1    .035       0
  5261.6     .07       0  5394.9    .035       0  5560.6     .07       0
Bank Sta=5037.3,5107.1
XS Rating Curve= 0 ,0
Exp/Cntr=0.3,0.1