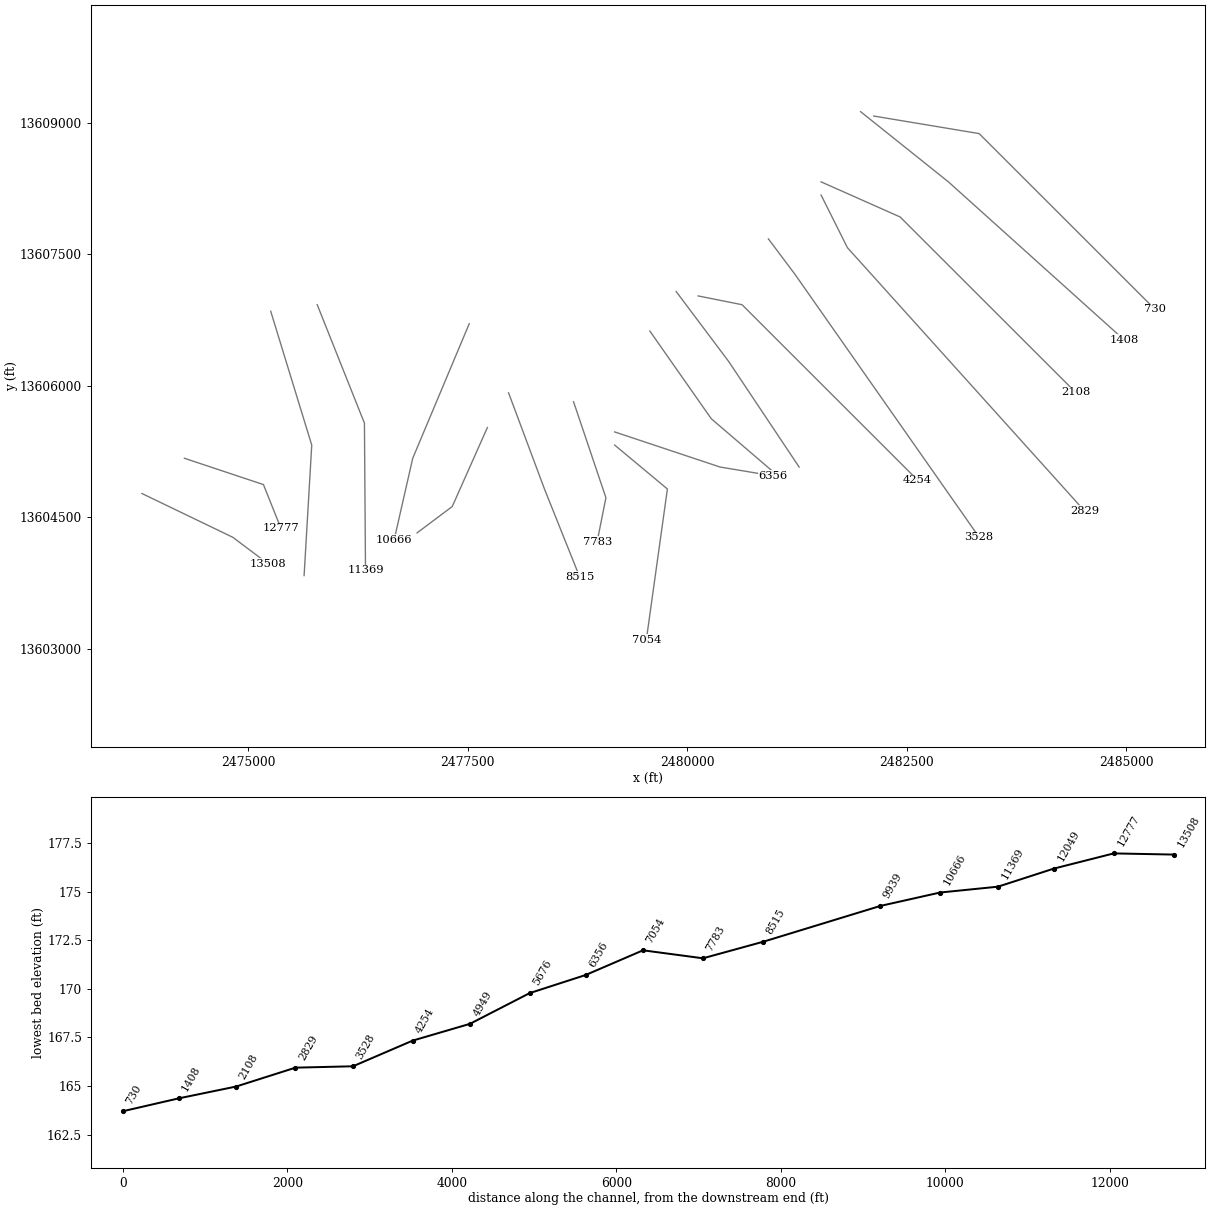
HEC-RAS study CLEAR CREEK.prj: CLEAR CREEK Base Level Engineering

--- CLEAR CREEK.g01 (geometry) --- (continued)

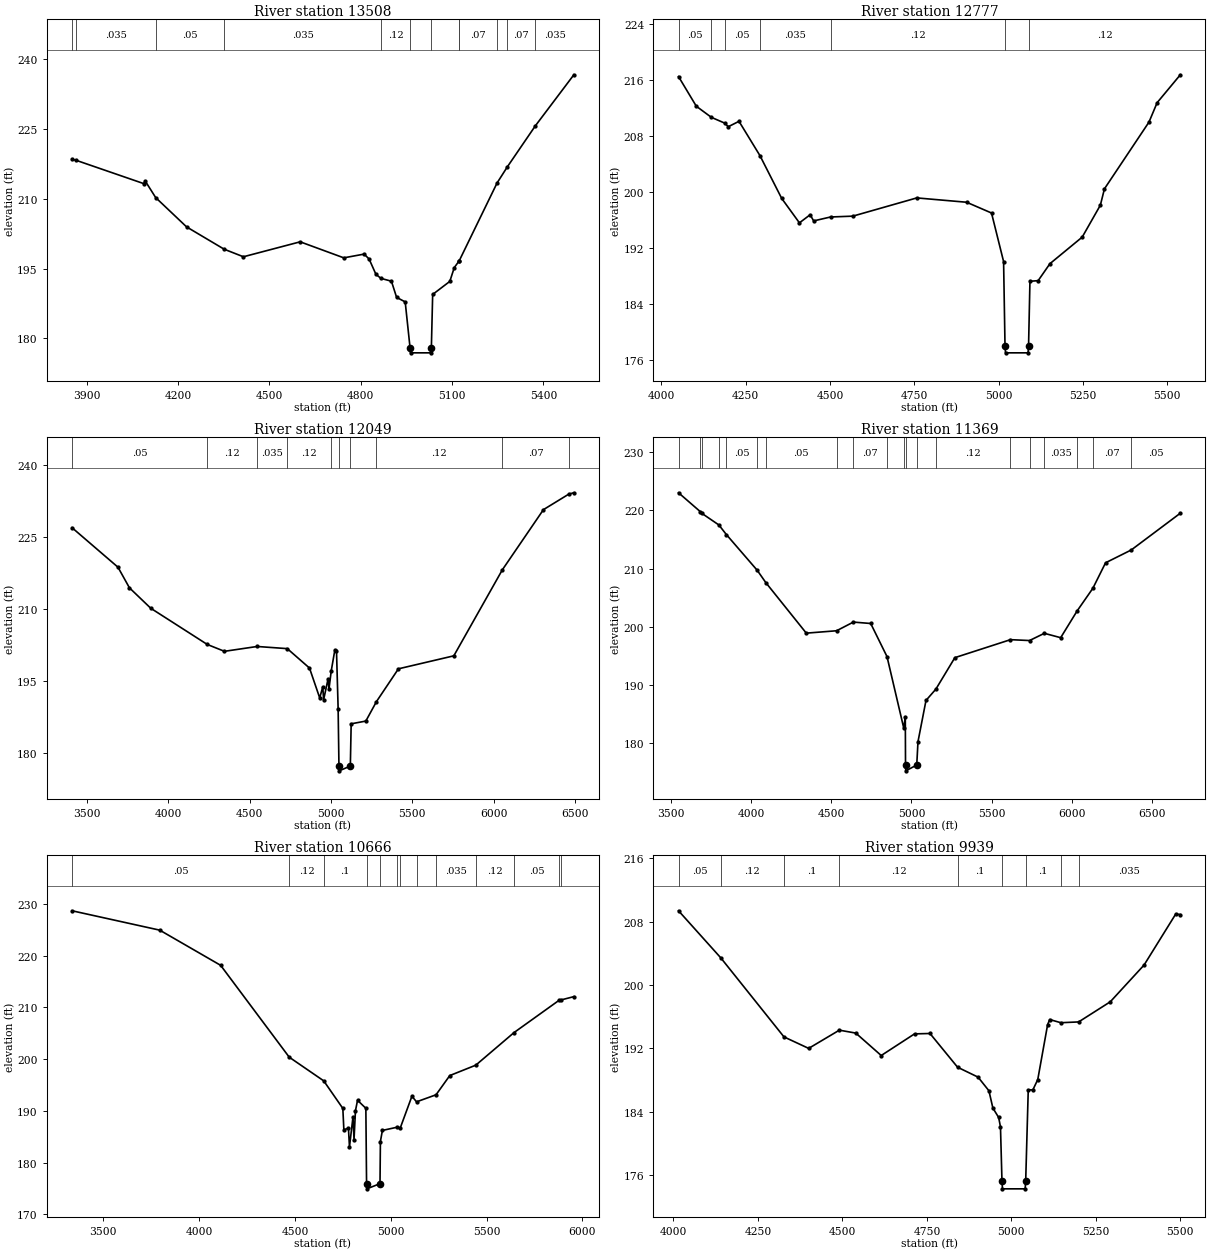
Type RM Length L Ch R = 1 ,13508   ,731,731,731
BEGIN DESCRIPTION:
CLEAR CREEK 18.0
END DESCRIPTION:
XS GIS Cut Line= 3
      2473791.28     13604773.36        2474825.       13604275.
      2475225.02     13603974.99
#Sta/Elev= 30
  3852.4  218.42  3863.7  218.29  4087.3  213.25  4092.8  213.78  4126.9  210.24
  4228.5  203.94  4351.9  199.15    4415  197.53  4601.4  200.74  4744.6   197.3
  4811.3   198.1  4827.6  197.06  4850.2  193.75  4866.7  192.89    4901  192.28
    4918  188.81  4946.2  187.84  4962.3   177.9  4963.8   176.9  5030.6   176.9
  5032.1   177.9  5036.4  189.44  5092.7  192.24  5107.3   195.2  5122.3  196.55
  5123.1   196.6  5247.9  213.38  5281.3  216.81  5373.6  225.65    5500  236.61
#Mann= 12 ,-1 , 0
  3852.4     .05       0  3863.7    .035       0  4126.9     .05       0
  4351.9    .035       0  4866.7     .12       0  4962.3     .05       0
  5032.1     .12       0  5122.3     .12       0  5123.1     .07       0
  5247.9    .035       0  5281.3     .07       0  5373.6    .035       0
Bank Sta=4962.3,5032.1
XS Rating Curve= 0 ,0
Exp/Cntr=0.3,0.1

Type RM Length L Ch R = 1 ,12777   ,728,728,728
BEGIN DESCRIPTION:
CLEAR CREEK 17.0
END DESCRIPTION:
XS GIS Cut Line= 3
      2474275.04     13605174.99        2475175.       13604875.
      2475375.02     13604374.96
#Sta/Elev= 30
  4051.4  216.49  4104.1  212.25  4148.7  210.66  4187.9  209.84  4198.9  209.32
  4230.6  210.09  4292.6  205.19    4357  199.07  4409.7  195.56  4441.4  196.72
  4451.9  195.84  4501.9   196.4  4567.9  196.52  4757.6  199.13  4905.2  198.51
    4979  196.97  5014.8  190.02    5019  177.96  5020.5  176.96  5087.3  176.96
  5088.8  177.96  5092.9   187.2  5117.2  187.29  5152.2  189.72  5247.8  193.52
  5301.6  198.09  5313.7  200.43  5445.7  209.98  5469.9  212.76  5538.6  216.75
#Mann= 7 ,-1 , 0
  4051.4     .05       0  4148.7    .035       0  4187.9     .05       0
  4292.6    .035       0  4501.9     .12       0    5019     .05       0
  5088.8     .12       0
Bank Sta=5019,5088.8
XS Rating Curve= 0 ,0
Exp/Cntr=0.3,0.1

Type RM Length L Ch R = 1 ,12049   ,680,680,680
BEGIN DESCRIPTION:
CLEAR CREEK 16.0
END DESCRIPTION:
XS GIS Cut Line= 3
       2475257.7     13606850.72        2475725.       13605325.
      2475637.97     13603838.23
#Sta/Elev= 30
  3408.9  226.89    3691  218.66  3761.7  214.35  3892.8  210.09  4240.2  202.54
  4345.7  201.11  4546.8  202.12    4732  201.67  4868.6  197.62  4931.4  191.39
  4950.2  193.69  4955.4  191.01    4983  195.39  4988.2  193.19  5002.2  197.01
  5024.6  201.42  5034.6  201.28  5044.7  189.09  5049.7  177.18  5051.2  176.18
  5119.7  177.18  5124.8  185.99  5214.9  186.56  5280.4  190.63  5415.3  197.46
  5755.9  200.17  6054.4  218.12  6306.8  230.66  6463.8  233.92  6493.9  234.18
#Mann= 10 ,-1 , 0
  3408.9     .05       0  4240.2     .12       0  4546.8    .035       0
    4732     .12       0  5002.2      .1       0  5049.7     .05       0
  5119.7      .1       0  5280.4     .12       0  6054.4     .07       0
  6463.8    .035       0
Bank Sta=5049.7,5119.7
XS Rating Curve= 0 ,0
Exp/Cntr=0.3,0.1

Type RM Length L Ch R = 1 ,11369   ,703,703,703
BEGIN DESCRIPTION:
CLEAR CREEK 15.0
END DESCRIPTION:
XS GIS Cut Line= 3
      2475787.24     13606925.37        2476325.       13605575.
      2476337.11     13603898.76
#Sta/Elev= 30
    3547  223.03  3681.8  219.81  3693.8  219.47  3798.6   217.5  3845.4  215.85
  4037.5  209.72  4091.8  207.58  4343.9  198.91  4532.7  199.32  4637.5  200.81
  4745.6  200.57  4847.3  194.88  4952.1  182.56  4961.4  184.57  4962.8  176.25
  4964.3  175.25  5032.8  176.25  5040.5  180.26  5090.5  187.35  5152.1  189.29
  5270.5   194.7  5617.5  197.79  5736.3  197.64  5828.6  198.88  5930.5  198.13
  6033.4  202.74  6131.3  206.62  6210.5     211  6370.6   213.2  6676.8  219.52
#Mann= 20 ,-1 , 0
    3547     .05       0  3681.8     .07       0  3693.8     .05       0
  3798.6     .07       0  3845.4     .05       0  4037.5     .12       0
  4091.8     .05       0  4532.7     .05       0  4637.5     .07       0
  4847.3     .12       0  4952.1      .1       0  4962.8     .05       0
  5032.8      .1       0  5152.1     .12       0  5617.5    .035       0
  5736.3     .12       0  5828.6    .035       0  6033.4     .05       0
  6131.3     .07       0  6370.6     .05       0
Bank Sta=4962.8,5032.8
XS Rating Curve= 0 ,0
Exp/Cntr=0.3,0.1

Type RM Length L Ch R = 1 ,10666   ,727,727,727
BEGIN DESCRIPTION:
CLEAR CREEK 14.0
END DESCRIPTION:
XS GIS Cut Line= 3
      2477518.38     13606708.18        2476875.       13605175.
      2476662.99     13604243.84
#Sta/Elev= 30
  3337.3  228.64  3794.6   224.9  4112.3  218.11  4470.2  200.37  4650.2   195.8
  4749.8  190.48  4755.2  186.32    4779  186.69  4784.4  183.05  4802.8  188.85
  4808.2  184.44  4815.6  190.01  4826.5  192.05  4869.9   190.5  4873.6  175.95
  4875.1  174.95  4943.7  175.95  4945.8  184.09  4956.2  186.23  5030.8  186.83
  5049.5  186.72  5110.2  192.83  5134.3  191.75    5236  193.11  5307.7  196.82
  5443.4  198.83  5642.8  205.12  5877.7  211.35  5889.8  211.44    5955  212.06
#Mann= 13 ,-1 , 0
  3337.3     .05       0  4470.2     .12       0  4650.2      .1       0
  4873.6     .05       0  4943.7      .1       0  5030.8     .12       0
  5049.5    .035       0  5134.3     .12       0    5236    .035       0
  5443.4     .12       0  5642.8     .05       0  5877.7    .035       0
  5889.8     .05       0
Bank Sta=4873.6,4943.7
XS Rating Curve= 0 ,0
Exp/Cntr=0.3,0.1

Type RM Length L Ch R = 1 ,9939    ,1424,1424,1424
BEGIN DESCRIPTION:
CLEAR CREEK 13.0
END DESCRIPTION:
XS GIS Cut Line= 3
        2477725.     13605524.99        2477325.       13604625.
      2476924.98     13604324.99
#Sta/Elev= 30
  4015.1  209.36  4140.1  203.42  4327.1  193.44  4400.2  191.99    4491  194.29
  4539.7  193.92  4614.9  191.09  4713.4  193.82  4759.2  193.87  4840.9  189.61
  4901.5  188.36  4933.6  186.64  4945.3  184.46  4962.4  183.27  4967.8  182.08
  4972.2  175.26  4973.7  174.26  5040.9  174.26  5042.4  175.26    5050  186.76
  5063.5  186.74  5078.1  188.05  5107.3  194.99  5113.5  195.63  5146.5  195.23
  5199.1  195.33  5292.7  197.87  5392.7  202.51  5486.4  208.95    5500  208.88
#Mann= 9 ,-1 , 0
  4015.1     .05       0  4140.1     .12       0  4327.1      .1       0
    4491     .12       0  4840.9      .1       0  4972.2     .05       0
  5042.4      .1       0  5146.5     .12       0  5199.1    .035       0
Bank Sta=4972.2,5042.4
XS Rating Curve= 0 ,0
Exp/Cntr=0.3,0.1

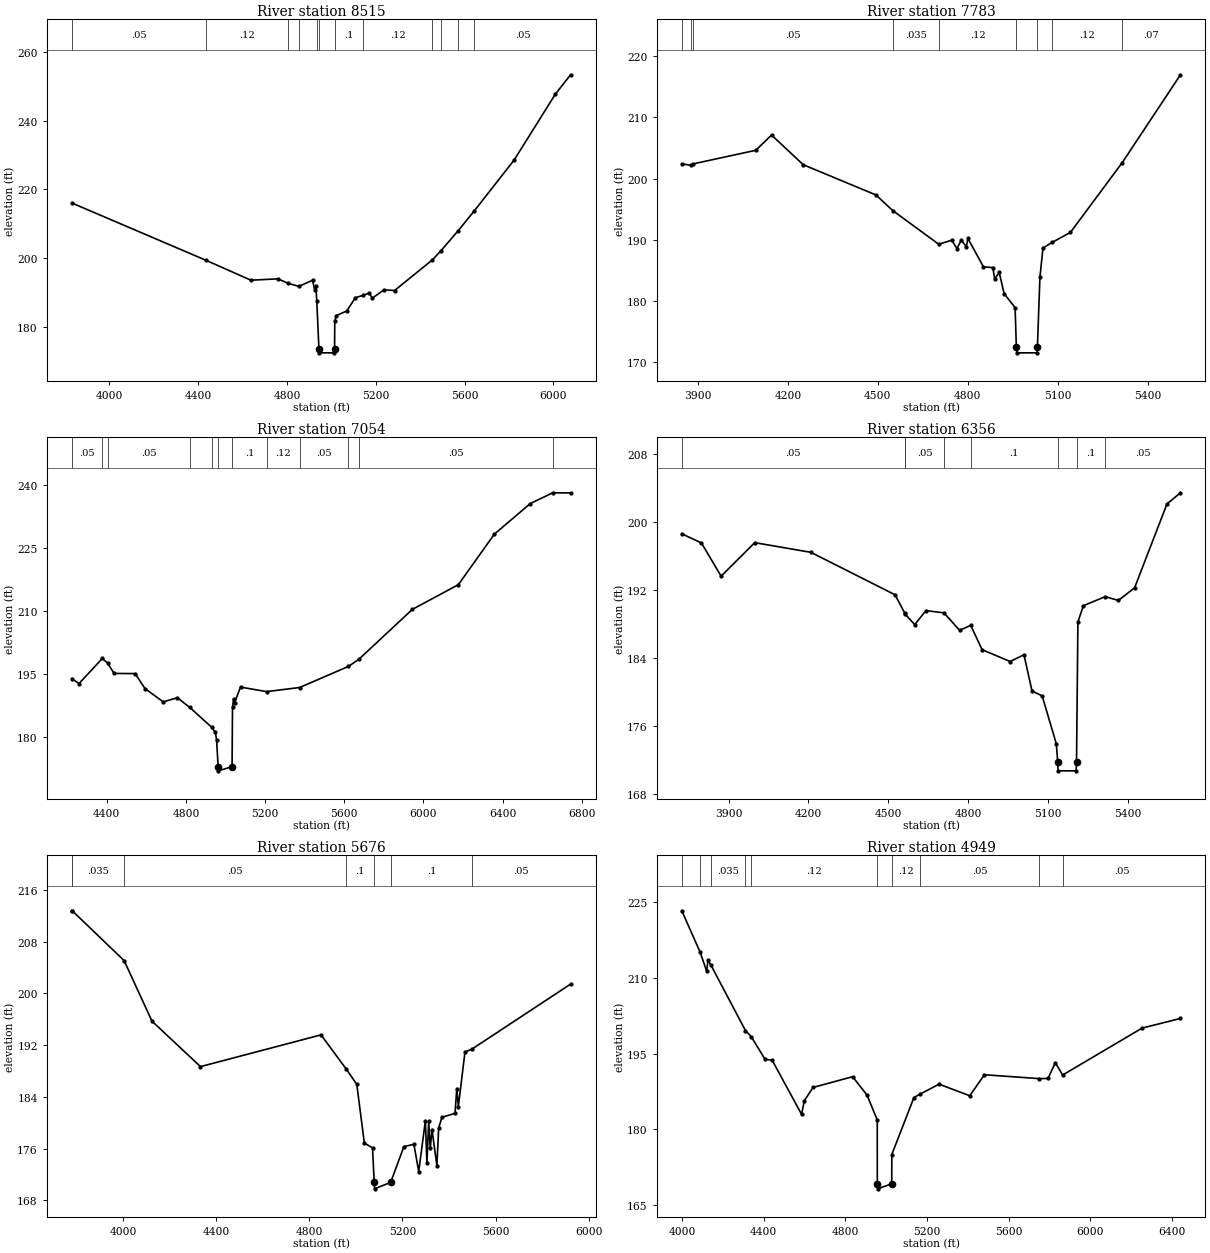
Type RM Length L Ch R = 1 ,8515    ,732,732,732
BEGIN DESCRIPTION:
CLEAR CREEK 12.0
END DESCRIPTION:
XS GIS Cut Line= 3
      2477966.45     13605920.64        2478375.       13604825.
      2478775.01     13603824.97
#Sta/Elev= 30
  3831.1  216.05  4434.8  199.38  4637.4  193.57  4758.7  193.97  4806.6  192.63
  4853.6  191.78  4915.1  193.56  4924.6  190.81    4930  191.92  4934.1   187.6
  4943.9  173.42  4945.4  172.42  5012.8  172.42  5014.3  173.42  5015.2  181.71
    5022  183.25  5069.1  184.61  5108.1  188.49  5140.5  189.13  5171.4  189.83
  5183.5  188.32  5237.4  190.77  5284.5  190.57  5455.3  199.51    5493  202.12
  5571.5  208.02  5643.5  213.75    5823  228.56  6008.8  247.76  6077.5   253.4
#Mann= 12 ,-1 , 0
  3831.1     .05       0  4434.8     .12       0  4806.6      .1       0
  4853.6     .12       0  4934.1      .1       0  4943.9     .05       0
  5014.3      .1       0  5140.5     .12       0  5455.3     .07       0
    5493     .05       0  5571.5     .07       0  5643.5     .05       0
Bank Sta=4943.9,5014.3
XS Rating Curve= 0 ,0
Exp/Cntr=0.3,0.1

Type RM Length L Ch R = 1 ,7783    ,729,729,729
BEGIN DESCRIPTION:
CLEAR CREEK 11.0
END DESCRIPTION:
XS GIS Cut Line= 3
      2478706.41     13605818.85        2479075.       13604725.
        2478975.     13604224.99
#Sta/Elev= 30
  3845.7  202.42    3878  202.18  3884.5  202.43  4092.5  204.64  4145.2  207.13
  4250.8  202.29  4493.5  197.35  4549.4  194.81  4703.2   189.3  4746.7  189.96
  4763.8   188.6  4778.4  189.96  4795.3   188.9  4800.6  190.24  4852.3  185.62
  4883.9  185.48  4889.8  183.63    4905  184.69  4921.3  181.24    4958  178.96
  4962.1  172.57  4963.6  171.57    5031  171.57  5032.5  172.57  5040.8  183.91
    5051  188.69  5081.1  189.59  5142.8  191.24  5315.1   202.6  5509.9  216.97
#Mann= 9 ,-1 , 0
  3845.7     .05       0    3878    .035       0  3884.5     .05       0
  4549.4    .035       0  4703.2     .12       0  4962.1     .05       0
  5032.5     .12       0  5081.1     .12       0  5315.1     .07       0
Bank Sta=4962.1,5032.5
XS Rating Curve= 0 ,0
Exp/Cntr=0.3,0.1

Type RM Length L Ch R = 1 ,7054    ,698,698,698
BEGIN DESCRIPTION:
CLEAR CREEK 10.0
END DESCRIPTION:
XS GIS Cut Line= 3
      2479174.96     13605325.03        2479775.       13604825.
      2479534.65     13603103.27
#Sta/Elev= 30
  4223.8  193.92  4259.6  192.75  4377.3  198.72  4403.7  197.66  4436.7  195.17
  4543.4  195.12  4592.9  191.57  4685.3  188.39  4756.9  189.38  4819.4  187.06
  4929.6  182.37  4948.3  181.15  4954.8  179.31  4962.5  172.98    4964  171.98
  5032.9  172.98  5035.2  187.08  5040.6  189.14  5045.7  188.21  5075.6  191.91
  5207.5  190.84    5374  191.81  5620.6  196.83  5672.4  198.48  5943.9  210.41
  6176.1  216.28  6357.9   228.3  6539.6  235.59  6653.1  238.16  6743.3  238.12
#Mann= 12 ,-1 , 0
  4223.8     .05       0  4377.3    .035       0  4403.7     .05       0
  4819.4     .07       0  4929.6      .1       0  4962.5     .05       0
  5032.9      .1       0  5207.5     .12       0    5374     .05       0
  5620.6     .12       0  5672.4     .05       0  6653.1     .07       0
Bank Sta=4962.5,5032.9
XS Rating Curve= 0 ,0
Exp/Cntr=0.3,0.1

Type RM Length L Ch R = 1 ,6356    ,680,680,680
BEGIN DESCRIPTION:
CLEAR CREEK 9.0
END DESCRIPTION:
XS GIS Cut Line= 3
      2479175.02     13605474.99        2480375.       13605075.
      2480975.04     13604974.99
#Sta/Elev= 30
  3724.4  198.57  3798.2  197.49    3872  193.59  3998.4  197.53  4209.3  196.39
  4525.5   191.4  4561.2  189.28  4563.3  189.12  4599.3   187.9  4641.4  189.54
  4709.2  189.28  4767.9  187.22  4809.7  187.81  4852.3  184.95  4957.7  183.56
  5009.6  184.35    5040  180.09    5078  179.52  5131.2  173.89  5136.5  171.71
    5138  170.71  5205.6  170.71  5207.1  171.71  5212.3   188.2  5232.6  190.11
  5314.4  191.18  5364.4  190.74  5425.2  192.22  5546.9  202.08  5597.6  203.39
#Mann= 8 ,-1 , 0
  3724.4     .05       0  4561.2     .07       0  4563.3     .05       0
  4709.2     .12       0  4809.7      .1       0  5136.5     .05       0
  5207.1      .1       0  5314.4     .05       0
Bank Sta=5136.5,5207.1
XS Rating Curve= 0 ,0
Exp/Cntr=0.3,0.1

Type RM Length L Ch R = 1 ,5676    ,727,727,727
BEGIN DESCRIPTION:
CLEAR CREEK 8.0
END DESCRIPTION:
XS GIS Cut Line= 3
      2479574.98     13606625.03        2480275.       13605625.
      2480974.97     13605025.03
#Sta/Elev= 30
    3780  212.78  3781.4  212.78  4004.4  205.07    4124  195.71  4332.4  188.68
  4850.3  193.59  4957.5  188.36    5004  185.94  5036.4  176.87  5071.5  176.11
  5078.9  170.78  5080.4  169.78  5149.6  170.78  5206.5  176.32  5249.3  176.66
  5270.1  172.46  5298.7  180.32  5305.3   173.7  5312.9   180.2  5319.5  176.03
  5327.2   178.9  5348.1  173.38  5355.8  179.18  5369.5  180.84    5426  181.45
  5433.7  185.29  5440.3  182.51  5468.8  190.94  5499.3   191.4  5922.6  201.44
#Mann= 7 ,-1 , 0
    3780     .05       0  3781.4    .035       0  4004.4     .05       0
  4957.5      .1       0  5078.9     .05       0  5149.6      .1       0
  5499.3     .05       0
Bank Sta=5078.9,5149.6
XS Rating Curve= 0 ,0
Exp/Cntr=0.3,0.1

Type RM Length L Ch R = 1 ,4949    ,695,695,695
BEGIN DESCRIPTION:
CLEAR CREEK 7.0
END DESCRIPTION:
XS GIS Cut Line= 3
        2479875.     13607075.01        2480475.       13606275.
      2481274.98     13605075.02
#Sta/Elev= 30
  3999.2  223.27  4088.2  215.15  4121.1  211.28  4127.3  213.52  4140.7   212.6
  4311.1  199.54  4339.5  198.33  4406.5  193.87  4441.9  193.66  4585.7  182.96
  4599.2  185.65  4641.9  188.28  4835.7  190.41  4906.5  186.76  4956.5  181.82
  4956.6   169.2  4958.1   168.2  5027.3   169.2  5027.8     175  5135.9  186.28
  5167.1  186.98  5259.1  188.93  5409.3  186.64  5481.4   190.8  5748.2  190.03
  5792.4  190.06  5828.5  193.18  5864.4  190.74  6253.6  200.04  6441.4  201.95
#Mann= 10 ,-1 , 0
  3999.2     .07       0  4088.2     .05       0  4140.7    .035       0
  4311.1     .05       0  4339.5     .12       0  4956.6     .05       0
  5027.3     .12       0  5167.1     .05       0  5748.2    .035       0
  5864.4     .05       0
Bank Sta=4956.6,5027.3
XS Rating Curve= 0 ,0
Exp/Cntr=0.3,0.1

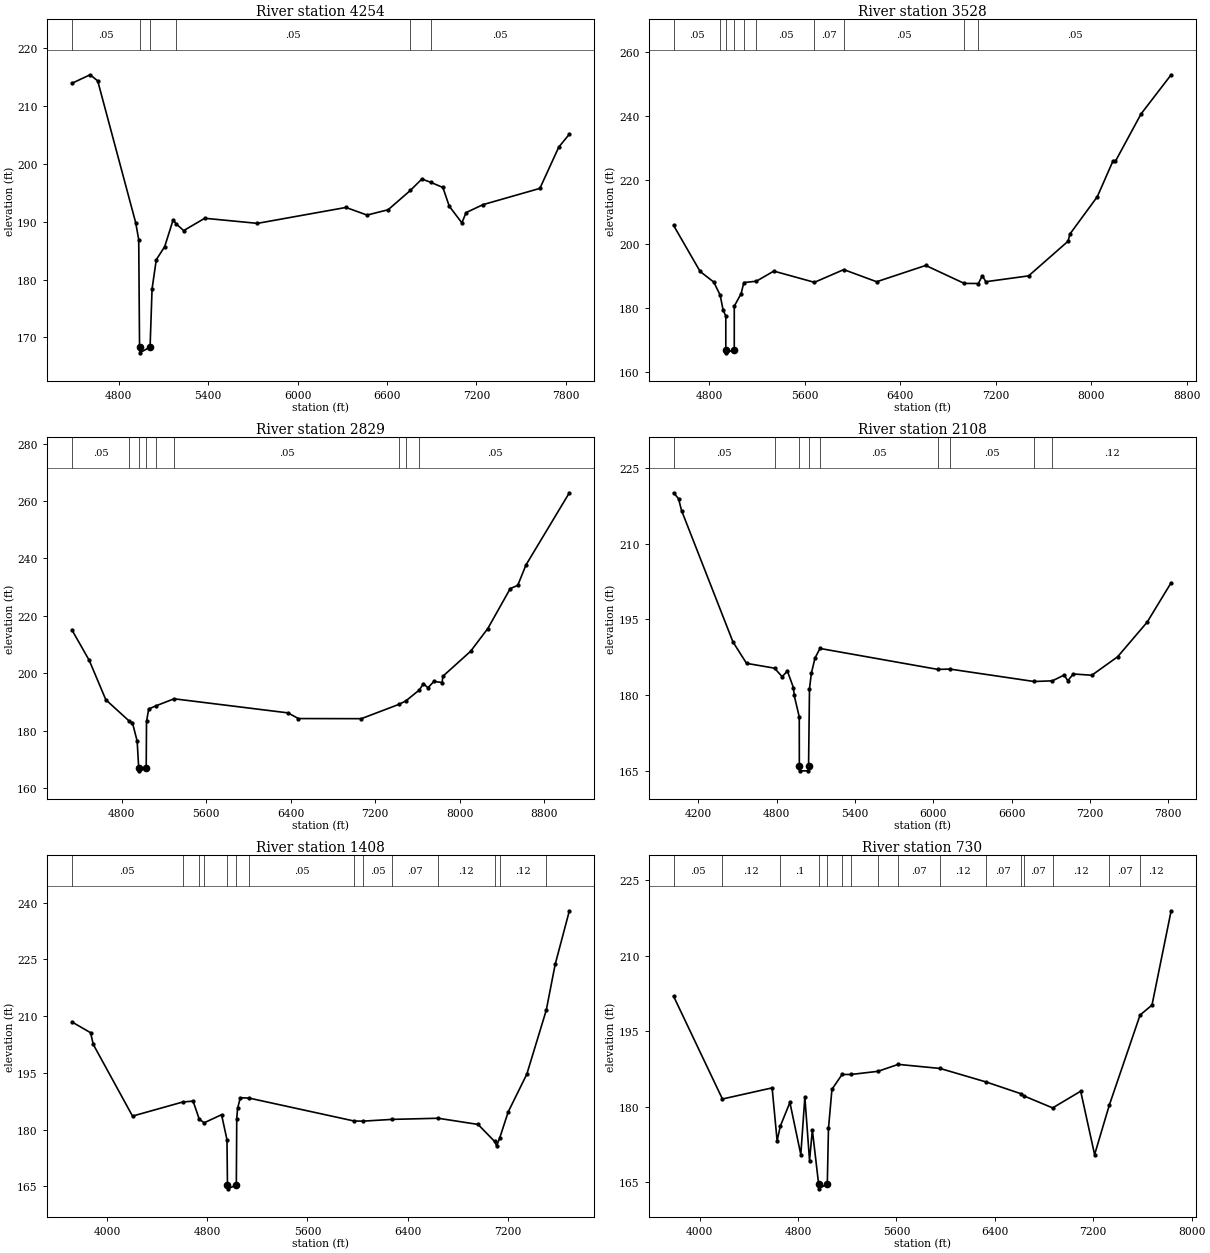
Type RM Length L Ch R = 1 ,4254    ,726,726,726
BEGIN DESCRIPTION:
CLEAR CREEK 6.0
END DESCRIPTION:
XS GIS Cut Line= 3
      2480124.97     13607025.01        2480625.       13606925.
      2482625.03     13604924.97
#Sta/Elev= 30
  4485.3   213.9  4607.7  215.38  4658.7  214.33  4913.6  189.83    4934  186.91
  4939.5  168.34    4941  167.34  5010.2  168.34  5023.5  178.38  5051.8  183.43
  5108.4   185.7  5164.9  190.31  5185.8  189.61  5235.6  188.46  5377.1  190.59
  5730.6  189.71  6324.6  192.46    6466  191.14  6607.4  192.06  6756.4  195.39
  6833.7  197.37  6891.9  196.82  6975.1  195.91  7017.6  192.68  7102.4   189.8
  7130.7  191.57  7243.8  192.94  7625.7  195.75  7752.9   202.9  7823.7  205.12
#Mann= 6 ,-1 , 0
  4485.3     .05       0  4939.5     .05       0  5010.2     .05       0
  5185.8     .05       0  6756.4    .035       0  6891.9     .05       0
Bank Sta=4939.5,5010.2
XS Rating Curve= 0 ,0
Exp/Cntr=0.3,0.1

Type RM Length L Ch R = 1 ,3528    ,699,699,699
BEGIN DESCRIPTION:
CLEAR CREEK 5.0
END DESCRIPTION:
XS GIS Cut Line= 3
      2480924.97     13607675.04        2481225.       13607275.
      2483324.99     13604275.01
#Sta/Elev= 30
  4504.3  205.86  4726.2  191.47  4840.8  188.14  4893.7  184.07  4917.9  179.44
  4940.8  177.52  4940.9  167.02  4942.4  166.02  5011.6  167.02  5011.8  180.65
  5068.4  184.47  5091.8     188  5196.5  188.43  5342.2  191.59  5682.1  188.08
  5927.8  192.06  6202.8  188.26  6613.4  193.36  6935.7  187.74  7053.6  187.71
  7086.9  190.14  7116.1  188.27    7474   190.1  7804.4  200.95  7819.3  203.17
  8048.6  214.86  8178.1   225.9  8200.3  225.96  8414.8  240.77  8666.3  253.01
#Mann= 10 ,-1 , 0
  4504.3     .05       0  4893.7      .1       0  4940.9     .05       0
  5011.6      .1       0  5091.8     .12       0  5196.5     .05       0
  5682.1     .07       0  5927.8     .05       0  6935.7    .035       0
  7053.6     .05       0
Bank Sta=4940.9,5011.6
XS Rating Curve= 0 ,0
Exp/Cntr=0.3,0.1

Type RM Length L Ch R = 1 ,2829    ,721,721,721
BEGIN DESCRIPTION:
CLEAR CREEK 4.0
END DESCRIPTION:
XS GIS Cut Line= 3
        2481525.       13608175.        2481825.       13607575.
        2484525.       13604575.
#Sta/Elev= 30
  4329.2  215.13  4494.1  204.44  4650.6  190.73  4869.3  183.39  4902.2  182.72
  4946.9  176.36  4961.8  166.95  4963.3  165.95  5032.6  166.95  5035.5  183.16
  5056.4  187.52  5123.7   188.6  5296.5  191.07  6373.4  186.16  6472.8  184.18
  7067.8  184.14  7424.4  189.14    7488  190.31  7617.3  194.16  7655.2  196.36
  7697.8  194.91  7754.6  197.12  7832.4  196.75  7839.1  198.92  8101.4  207.63
  8264.4  215.57  8476.7   229.5  8547.7  230.62  8625.4  237.73  9036.1  262.91
#Mann= 9 ,-1 , 0
  4329.2     .05       0  4869.3      .1       0  4961.8     .05       0
  5032.6      .1       0  5123.7     .12       0  5296.5     .05       0
  7424.4     .12       0    7488    .035       0  7617.3     .05       0
Bank Sta=4961.8,5032.6
XS Rating Curve= 0 ,0
Exp/Cntr=0.3,0.1

Type RM Length L Ch R = 1 ,2108    ,700,700,700
BEGIN DESCRIPTION:
CLEAR CREEK 3.0
END DESCRIPTION:
XS GIS Cut Line= 3
      2481525.03     13608324.99        2482425.       13607925.
      2484425.02     13605924.98
#Sta/Elev= 30
  4010.1   220.1  4047.7  218.93  4070.9  216.58  4464.9  190.54  4568.8  186.29
  4783.8  185.33  4841.7  183.64  4882.1  184.76  4928.6  181.46  4934.1  179.96
  4973.1  175.67  4973.7  165.98  4975.2  164.98    5043  164.98  5044.5  165.98
  5051.5  181.25  5065.7   184.3  5093.9  187.36  5132.1  189.24  6034.8  185.09
  6128.1  185.15  6772.6  182.69  6913.1  182.82  7003.1  183.96  7031.4  182.85
  7073.8  184.18  7215.3  183.93  7413.3  187.59  7639.5  194.45  7823.4  202.27
#Mann= 9 ,-1 , 0
  4010.1     .05       0  4783.8      .1       0  4973.7     .05       0
  5044.5      .1       0  5132.1     .05       0  6034.8    .035       0
  6128.1     .05       0  6772.6    .035       0  6913.1     .12       0
Bank Sta=4973.7,5044.5
XS Rating Curve= 0 ,0
Exp/Cntr=0.3,0.1

Type RM Length L Ch R = 1 ,1408    ,678,678,678
BEGIN DESCRIPTION:
CLEAR CREEK 2.0
END DESCRIPTION:
XS GIS Cut Line= 3
      2481974.97     13609125.03        2482975.       13608325.
      2484975.01     13606524.99
#Sta/Elev= 30
  3719.3  208.48    3869  205.62  3889.8  202.55  4203.6  183.59  4603.4   187.3
    4687  187.56  4736.7  182.73  4776.1  181.83  4914.3  183.96  4957.5  177.36
  4961.4  165.37  4962.9  164.37  5032.2  165.37  5035.5   182.9  5042.2  185.62
  5063.9  188.43  5133.9  188.35  5972.4  182.29  6045.4  182.26  6275.3  182.72
  6643.4  183.02  6961.6  181.39  7094.2  176.89  7110.3   175.7  7135.7  177.91
  7202.2  184.68    7351  194.67    7506  211.55  7577.5  223.69  7690.7  237.84
#Mann= 14 ,-1 , 0
  3719.3     .05       0  4603.4     .12       0  4736.7     .05       0
  4776.1      .1       0  4961.4     .05       0  5032.2      .1       0
  5133.9     .05       0  5972.4    .035       0  6045.4     .05       0
  6275.3     .07       0  6643.4     .12       0  7094.2     .07       0
  7135.7     .12       0    7506     .07       0
Bank Sta=4961.4,5032.2
XS Rating Curve= 0 ,0
Exp/Cntr=0.3,0.1

Type RM Length L Ch R = 1 ,730     ,0,0,0
BEGIN DESCRIPTION:
CLEAR CREEK 1.0
END DESCRIPTION:
XS GIS Cut Line= 3
      2482124.96     13609075.01        2483325.       13608875.
      2485324.99     13606875.01
#Sta/Elev= 30
  3788.1  201.96  4184.9  181.56    4589  183.77  4629.6  173.25  4655.4  176.16
  4733.5  180.87  4822.2  170.52  4855.2  181.94  4893.2  169.32    4916   175.4
  4966.8  164.71  4968.3  163.71  5037.6  164.71  5047.1   175.7  5075.4  183.49
  5157.8  186.44  5228.4  186.43  5449.3  187.06  5614.1  188.44  5954.6  187.63
  6327.9  184.95  6609.5  182.63  6636.3  182.17  6869.8  179.79  7097.7  183.11
  7210.9  170.51  7330.2  180.33  7580.5  198.24  7677.6  200.23  7833.1  218.96
#Mann= 16 ,-1 , 0
  3788.1     .05       0  4184.9     .12       0  4655.4      .1       0
  4966.8     .05       0  5037.6      .1       0  5157.8     .12       0
  5228.4    .035       0  5449.3     .12       0  5614.1     .07       0
  5954.6     .12       0  6327.9     .07       0  6609.5      .1       0
  6636.3     .07       0  6869.8     .12       0  7330.2     .07       0
  7580.5     .12       0
Bank Sta=4966.8,5037.6
XS Rating Curve= 0 ,0
Exp/Cntr=0.3,0.1

Chan Stop Cuts=-1
Use User Specified Reach Order=0
Composite Channel Slope=5