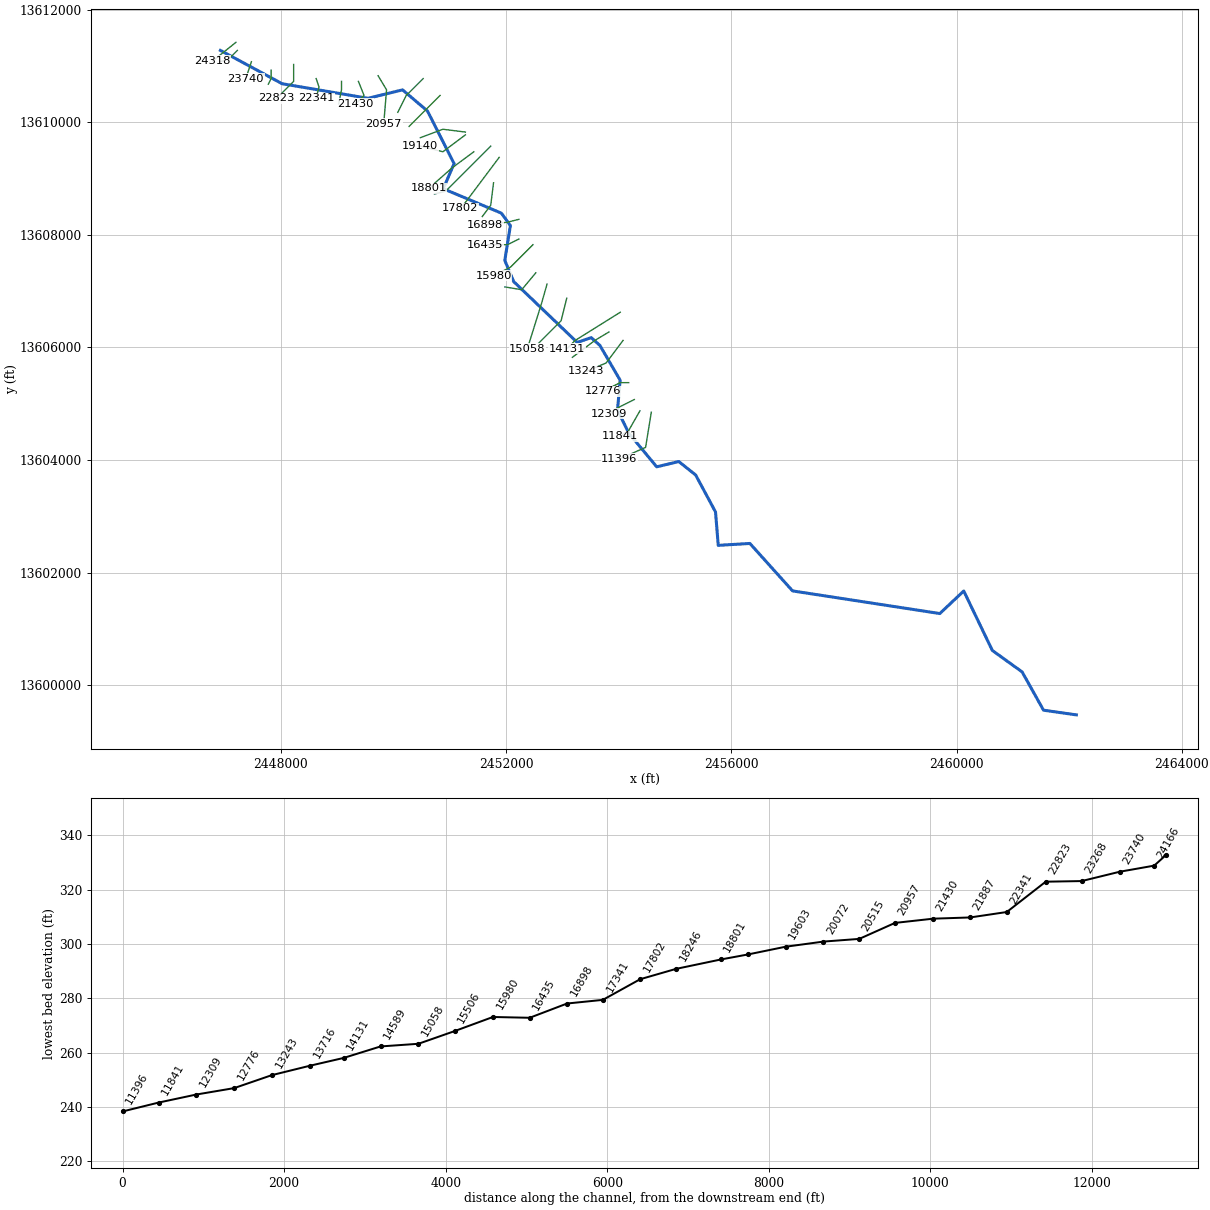
--- COOPER CREEK.prj (project) ---

Proj Title=COOPER CREEK Base Level Engineering
Current Plan=p01
Default Exp/Contr=0.3,0.1
English Units
Geom File=g01
Flow File=f01
Plan File=p01
Y Axis Title=Elevation
X Axis Title(PF)=Main Channel Distance
X Axis Title(XS)=Station
BEGIN DESCRIPTION:
COOPER CREEK
END DESCRIPTION:
DSS Export Rating Curves= 0
DSS Export Rating Curve Sorted= 0
DSS Export Volume Flow Curves= 0
DXF OffsetX= 0
DXF OffsetY= 0
DXF ScaleX= 1
DXF ScaleY= 10

--- COOPER CREEK.p01 (plan) ---

Plan Title=Multiple Run
Short Identifier=Multiple
Geom File=g01
Flow File=f01
Subcritical Flow
K Sum by GR= 0
Std Step Tol= 0.01
Critical Tol= 0.01
Num of Std Step Trials= 20
Max Error Tol= 0.3
Flow Tol Ratio= 0.001
Split Flow NTrial= 30
Split Flow Tol= 0.02
Split Flow Ratio= 0.02
Log Output Level= 0
Friction Slope Method= 1
Unsteady Friction Slope Method= 2
Unsteady Bridges Friction Slope Method= 1
Parabolic Critical Depth
Global Vel Dist=  1 , 1 , 1
Global Log Level= 0
CheckData=True
Encroach Param= -1, 0, 0, 0
BEGIN DESCRIPTION:
Multiple Run
END DESCRIPTION:

--- COOPER CREEK.f01 (steady flow) ---

Flow Title=Multiple
Number of Profiles=7
Profile Names=10-year,25-year,50-year,1pct_min,100-year,1pct_plu,500-year
River Rch & RM= COOPER CREEK,Reach-1,24318
     595     966    1303     853    1702    3397    2875
River Rch & RM= COOPER CREEK,Reach-1,20515
     894    1483    2032    1349    2691    5369    4675
River Rch & RM= COOPER CREEK,Reach-1,19140
     998    1660    2275    1509    3012    6009    5229
River Rch & RM= COOPER CREEK,Reach-1,15058
    1564    2657    3697    2485    4958    9892    8840
River Rch & RM= COOPER CREEK,Reach-1,10470
    2023    3458    4827    3252    6489   12947   11627
River Rch & RM= COOPER CREEK,Reach-1,3159
    2338    4007    5603    3778    7538   15040   13530
Boundary for River Rch & Prof#=COOPER CREEK,Reach-1,1
Up Type=0
Dn Type=3
Dn Slope=0.005
Boundary for River Rch & Prof#=COOPER CREEK,Reach-1,2
Up Type=0
Dn Type=3
Dn Slope=0.005
Boundary for River Rch & Prof#=COOPER CREEK,Reach-1,3
Up Type=0
Dn Type=3
Dn Slope=0.005
Boundary for River Rch & Prof#=COOPER CREEK,Reach-1,4
Up Type=0
Dn Type=3
Dn Slope=0.005
Boundary for River Rch & Prof#=COOPER CREEK,Reach-1,5
Up Type=0
Dn Type=3
Dn Slope=0.005
Boundary for River Rch & Prof#=COOPER CREEK,Reach-1,6
Up Type=0
Dn Type=3
Dn Slope=0.005
Boundary for River Rch & Prof#=COOPER CREEK,Reach-1,7
Up Type=0
Dn Type=3
Dn Slope=0.005

--- COOPER CREEK.g01 (geometry) ---

Geom Title=Existing Conditions
Program Version=4.10

River Reach=COOPER CREEK    ,Reach-1
Reach XY= 30
        2446925.       13611275.       2448021.7     13610683.08
       2449545.2     13610424.63      2450159.16     13610574.35
      2450601.88     13610198.73      2451074.07     13609264.52
      2450882.69     13608818.52      2451914.23      13608384.7
      2452074.07     13608164.52      2451974.79     13607545.05
      2452133.14     13607168.94       2453261.6      13606088.5
      2453509.78     13606174.76      2453664.48     13606034.79
      2454022.76     13605419.07      2453976.08     13604885.54
      2454180.52     13604472.56      2454672.48     13603880.31
       2455064.5      13603973.8      2455364.48     13603734.79
      2455716.96     13603078.32      2455765.19     13602485.51
      2456327.28     13602519.18       2457085.5     13601676.22
      2459700.04      13601274.5        2460125.       13601675.
      2460632.86     13600618.83      2461161.38     13600238.24
      2461541.64     13599558.29        2462125.       13599475.

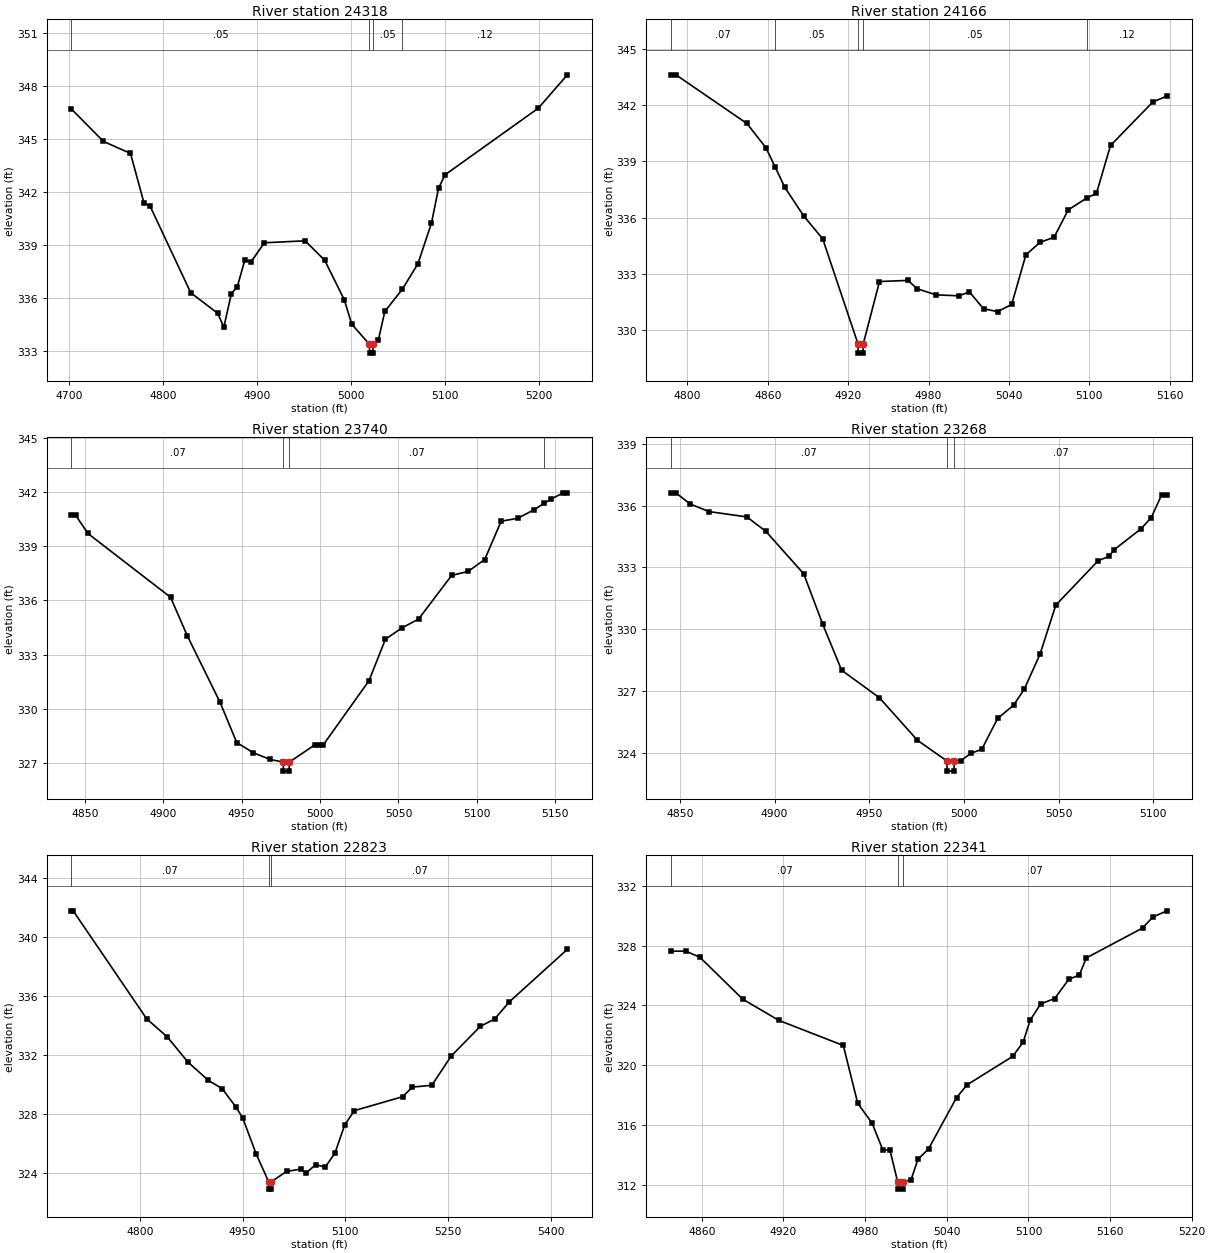
Type RM Length L Ch R = 1 ,24318   ,152,152,152
BEGIN DESCRIPTION:
X18507
END DESCRIPTION:
XS GIS Cut Line= 2
      2447200.23     13611418.29      2446787.97     13611089.06
#Sta/Elev= 30
  4702.2  346.68  4736.2  344.85    4765  344.17  4779.4  341.36  4785.8  341.19
  4829.1  336.28  4857.9  335.11  4864.3  334.33  4872.3  336.22  4878.7  336.63
  4886.7  338.14  4893.1  338.02  4907.5  339.11  4950.8  339.22  4971.6  338.12
  4992.4  335.89  5000.4   334.5  5019.2  333.36  5019.5  332.86    5023  332.86
  5023.2  333.36  5028.8  333.62  5035.6  335.22  5054.1  336.47  5070.8  337.92
  5085.2  340.22  5092.8  342.21  5099.7  342.96  5198.9  346.73  5229.8  348.62
#Mann= 4 ,-1 , 0
  4702.2     .05       0  5019.2     .05       0  5023.2     .05       0
  5054.1     .12       0
Bank Sta=5019.2,5023.2
XS Rating Curve= 0 ,0
Exp/Cntr=0.3,0.1

Type RM Length L Ch R = 1 ,24166   ,426,426,426
BEGIN DESCRIPTION:
COOPER CREEK 49.0
END DESCRIPTION:
XS GIS Cut Line= 3
      2447225.03     13611275.03        2447075.       13611125.
      2446924.99       13611075.
#Sta/Elev= 30
  4787.8   343.6  4791.4   343.6  4844.4  341.01  4858.6  339.72  4865.5  338.69
  4872.7  337.61  4886.8  336.09    4901  334.87  4927.3  329.29  4927.5  328.79
    4931  328.79  4931.3  329.29  4943.4   332.6  4964.6  332.66  4971.7  332.21
  4985.8  331.89  5002.6  331.84  5010.5  332.05  5021.1  331.15  5031.6     331
  5042.1  331.38  5052.7  334.02  5063.2  334.68  5073.8  334.96  5084.3  336.41
  5098.5  337.06  5105.4  337.29  5115.9  339.84  5147.6  342.16  5158.1  342.47
#Mann= 5 ,-1 , 0
  4787.8     .07       0  4865.5     .05       0  4927.3     .05       0
  4931.3     .05       0  5098.5     .12       0
Bank Sta=4927.3,4931.3
XS Rating Curve= 0 ,0
Exp/Cntr=0.3,0.1

Type RM Length L Ch R = 1 ,23740   ,472,472,472
BEGIN DESCRIPTION:
COOPER CREEK 48.0
END DESCRIPTION:
XS GIS Cut Line= 3
      2447474.99     13611074.97        2447425.       13610925.
        2447375.     13610774.99
#Sta/Elev= 30
  4841.5  340.72  4844.1  340.72    4852   339.7  4904.7  336.17  4915.3  334.05
  4936.3  330.35  4946.9  328.13  4957.4  327.57    4968   327.2  4976.5  327.05
  4976.7  326.55  4980.2  326.55  4980.5  327.05  4996.9  328.02  4999.6  328.02
  5002.2  328.02  5031.2  331.55  5041.7  333.85  5052.3  334.48  5062.8  334.96
  5083.9  337.38  5094.4   337.6    5105  338.26  5115.5  340.38  5126.1  340.54
  5136.6  341.02  5143.1  341.38  5147.2   341.6  5155.1  341.95  5157.7  341.95
#Mann= 4 ,-1 , 0
  4841.5     .07       0  4976.5     .05       0  4980.5     .07       0
  5143.1    .035       0
Bank Sta=4976.5,4980.5
XS Rating Curve= 0 ,0
Exp/Cntr=0.3,0.1

Type RM Length L Ch R = 1 ,23268   ,445,445,445
BEGIN DESCRIPTION:
COOPER CREEK 47.0
END DESCRIPTION:
XS GIS Cut Line= 3
        2447825.     13610925.04        2447825.       13610775.
      2447775.02     13610675.03
#Sta/Elev= 30
  4845.4  336.62  4847.9  336.62  4855.4  336.08  4865.4  335.71  4885.4  335.45
  4895.4  334.75  4915.4  332.69  4925.4  330.25  4935.4  328.01  4955.4  326.67
  4975.4  324.61  4990.9  323.61  4991.2  323.11  4994.7  323.11  4994.9  323.61
  4998.2  323.61  5003.8  323.98  5009.4  324.17  5017.8  325.67  5026.2  326.31
  5031.8  327.08  5040.2   328.8  5048.5  331.17  5070.9  333.33  5076.5  333.53
  5079.3  333.86  5093.3  334.86  5098.9  335.42  5104.4  336.53  5107.2  336.53
#Mann= 3 ,-1 , 0
  4845.4     .07       0  4990.9     .05       0  4994.9     .07       0
Bank Sta=4990.9,4994.9
XS Rating Curve= 0 ,0
Exp/Cntr=0.3,0.1

Type RM Length L Ch R = 1 ,22823   ,482,482,482
BEGIN DESCRIPTION:
COOPER CREEK 46.0
END DESCRIPTION:
XS GIS Cut Line= 3
        2448225.     13611025.01        2448225.       13610725.
      2447924.98     13610424.98
#Sta/Elev= 30
  4700.1  341.75  4702.6  341.75  4810.1  334.42  4840.1   333.2  4870.1   331.5
  4900.1  330.25  4920.1   329.7  4940.1  328.46  4950.1  327.72  4970.1  325.24
  4988.1  323.38  4988.4  322.88  4991.9  322.88  4992.1  323.38  5014.2  324.08
  5035.5  324.24  5042.5  323.95  5056.7  324.54  5070.8  324.37    5085  325.33
  5099.1  327.22  5113.2   328.2    5184  329.15  5198.1   329.8  5226.4  329.92
  5254.7   331.9  5297.1  333.91  5318.3  334.42  5339.5  335.57  5424.4  339.14
#Mann= 3 ,-1 , 0
  4700.1     .07       0  4988.1     .05       0  4992.1     .07       0
Bank Sta=4988.1,4992.1
XS Rating Curve= 0 ,0
Exp/Cntr=0.3,0.1

Type RM Length L Ch R = 1 ,22341   ,454,454,454
BEGIN DESCRIPTION:
COOPER CREEK 45.0
END DESCRIPTION:
XS GIS Cut Line= 3
      2448624.99     13610775.02        2448675.       13610625.
        2448625.     13610424.99
#Sta/Elev= 30
  4837.5  327.62  4848.1  327.63  4858.6  327.22  4890.2  324.41  4916.6     323
    4964  321.32  4974.6  317.45  4985.1  316.14    4993  314.34  4998.2  314.34
  5003.9  312.22  5004.2  311.72  5007.7  311.72  5007.9  312.22  5013.7  312.33
  5018.8  313.71  5026.6  314.41  5047.2  317.84  5054.9  318.69  5088.4  320.59
  5096.1  321.54  5101.3  323.02    5109   324.1  5119.3  324.46  5129.6  325.74
  5137.4  326.03  5142.5  327.17  5183.8  329.17  5191.5  329.91  5201.8  330.32
#Mann= 3 ,-1 , 0
  4837.5     .07       0  5003.9     .05       0  5007.9     .07       0
Bank Sta=5003.9,5007.9
XS Rating Curve= 0 ,0
Exp/Cntr=0.3,0.1

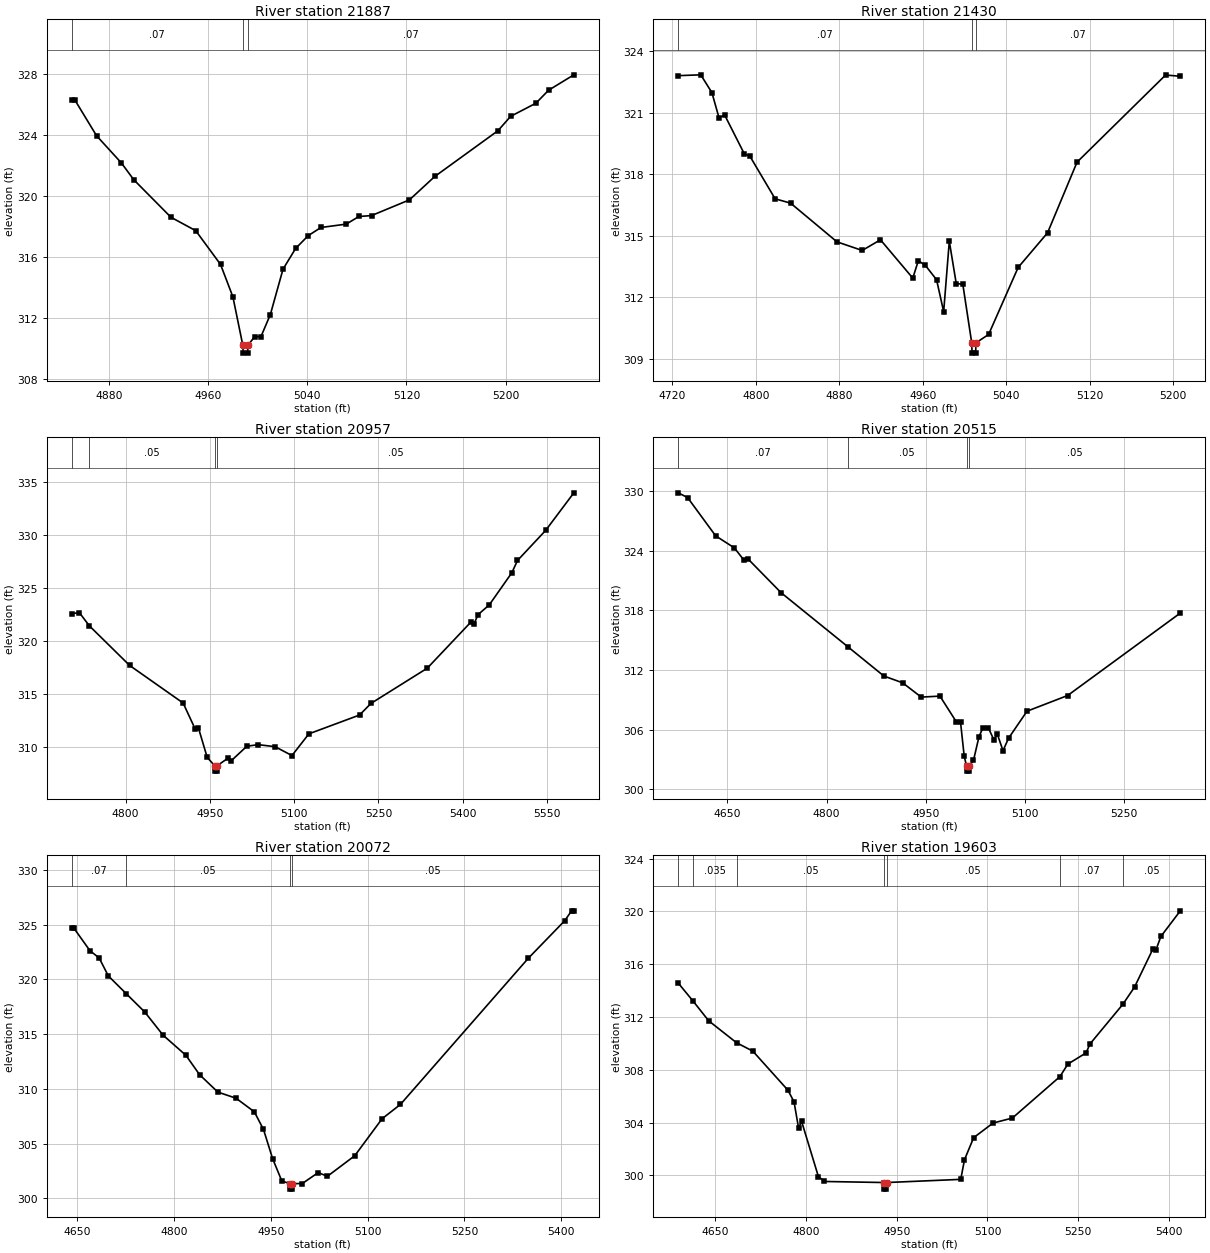
Type RM Length L Ch R = 1 ,21887   ,457,457,457
BEGIN DESCRIPTION:
COOPER CREEK 44.0
END DESCRIPTION:
XS GIS Cut Line= 3
        2449075.     13610725.03        2449075.       13610575.
        2449025.     13610324.98
#Sta/Elev= 30
    4850   326.3  4852.5   326.3    4870  323.96    4890  322.18    4900  321.08
    4930  318.62    4950  317.74    4970  315.53    4980   313.4    4988  310.22
  4988.3  309.72  4991.8  309.72    4992  310.22  4997.5   310.8  5002.6   310.8
  5010.2  312.25  5020.4  315.22  5030.6  316.58  5040.8  317.42    5051  317.95
  5071.4  318.17  5081.6  318.67  5091.8  318.73  5122.4  319.76  5142.8  321.29
  5193.8  324.29    5204  325.23  5224.4  326.09  5234.6  326.94    5255  327.95
#Mann= 3 ,-1 , 0
    4850     .07       0    4988     .05       0    4992     .07       0
Bank Sta=4988,4992
XS Rating Curve= 0 ,0
Exp/Cntr=0.3,0.1

Type RM Length L Ch R = 1 ,21430   ,473,473,473
BEGIN DESCRIPTION:
COOPER CREEK 43.0
END DESCRIPTION:
XS GIS Cut Line= 3
      2449374.99     13610725.03        2449475.       13610475.
      2449325.01     13610325.01
#Sta/Elev= 30
  4725.6  322.81  4747.2  322.85  4757.9  321.98  4764.7  320.75  4770.1  320.89
  4788.9     319  4794.3  318.88  4818.5   316.8  4833.3  316.59  4877.8   314.7
    4902  314.28  4919.5   314.8  4950.5  312.93  4955.8  313.78  4962.6  313.55
  4973.3  312.85  4980.1  311.29  4985.5  314.73  4992.2  312.65  4998.4  312.65
    5007  309.77  5007.3  309.27  5010.8  309.27    5011  309.77  5023.2  310.18
  5051.5  313.45  5079.7  315.14    5108  318.59  5192.9  322.84    5207  322.78
#Mann= 3 ,-1 , 0
  4725.6     .07       0    5007     .05       0    5011     .07       0
Bank Sta=5007,5011
XS Rating Curve= 0 ,0
Exp/Cntr=0.3,0.1

Type RM Length L Ch R = 1 ,20957   ,442,442,442
BEGIN DESCRIPTION:
COOPER CREEK 42.0
END DESCRIPTION:
XS GIS Cut Line= 3
      2449725.01     13610824.98        2449875.       13610575.
        2449825.     13609975.01
#Sta/Elev= 30
  4704.1  322.59  4717.7  322.67  4735.4  321.43  4807.1  317.69  4902.3  314.14
  4923.7  311.69  4929.5   311.8  4945.1  309.01  4958.6  308.21  4958.9  307.71
  4962.4  307.71  4962.6  308.21    4982  308.93  4987.9  308.69  5015.7  310.06
  5035.8  310.21  5065.9  310.02    5096  309.18  5126.1  311.23  5216.4  313.01
  5236.5   314.1  5336.8  317.43  5414.6  321.79  5419.6  321.56  5427.1  322.48
  5447.2  323.41  5487.3  326.44  5497.4   327.6  5547.5  330.44  5597.7  333.99
#Mann= 4 ,-1 , 0
  4704.1     .07       0  4735.4     .05       0  4958.6     .05       0
  4962.6     .05       0
Bank Sta=4958.6,4962.6
XS Rating Curve= 0 ,0
Exp/Cntr=0.3,0.1

Type RM Length L Ch R = 1 ,20515   ,443,443,443
BEGIN DESCRIPTION:
COOPER CREEK 41.0
END DESCRIPTION:
XS GIS Cut Line= 3
      2450525.03     13610775.03        2450225.       13610475.
      2450075.01     13610175.02
#Sta/Elev= 30
  4575.5  329.84  4589.7  329.36  4632.1  325.51  4660.4   324.3  4674.5   323.1
  4681.6  323.15  4731.1  319.79  4832.3  314.34  4886.7   311.4    4915  310.72
  4943.2  309.28  4971.5  309.38  4996.3  306.79  5002.6  306.79  5008.2  303.33
  5011.8  302.33    5012  301.83  5015.5  301.83  5015.8  302.33  5022.2   302.9
  5030.6   305.3  5036.1  306.13  5044.5  306.22  5052.9  305.01  5058.5  305.52
  5066.9  303.89  5075.3  305.14  5103.2  307.86  5164.7  309.44  5335.2  317.74
#Mann= 4 ,-1 , 0
  4575.5     .07       0  4832.3     .05       0  5011.8     .05       0
  5015.8     .05       0
Bank Sta=5011.8,5015.8
XS Rating Curve= 0 ,0
Exp/Cntr=0.3,0.1

Type RM Length L Ch R = 1 ,20072   ,469,469,469
BEGIN DESCRIPTION:
COOPER CREEK 40.0
END DESCRIPTION:
XS GIS Cut Line= 3
      2450824.99     13610474.99        2450575.       13610225.
        2450275.       13609925.
#Sta/Elev= 30
  4641.7  324.65  4645.2  324.65    4670   322.6  4684.1  321.95  4698.3  320.31
  4725.8   318.7  4754.8  317.01  4783.1   314.9  4818.5  313.06  4839.7  311.29
    4868   309.7  4896.2  309.14  4924.5   307.9  4938.7  306.29  4952.8  303.63
    4967   301.6  4979.1  301.34  4979.3  300.84  4982.8  300.84  4983.1  301.34
  4998.8  301.35  5023.5  302.35  5037.7  302.01  5080.1  303.89  5122.5  307.27
  5150.8  308.57  5348.8  321.91  5405.4  325.35    5416  326.25  5419.5  326.25
#Mann= 4 ,-1 , 0
  4641.7     .07       0  4725.8     .05       0  4979.1     .05       0
  4983.1     .05       0
Bank Sta=4979.1,4983.1
XS Rating Curve= 0 ,0
Exp/Cntr=0.3,0.1

Type RM Length L Ch R = 1 ,19603   ,463,463,463
BEGIN DESCRIPTION:
COOPER CREEK 39.0
END DESCRIPTION:
XS GIS Cut Line= 3
      2451274.97       13609825.        2450875.       13609875.
      2450474.99       13609725.
#Sta/Elev= 30
  4588.6  314.57  4613.1  313.21    4639  311.71    4685  310.05    4712  309.41
    4770  306.45  4780.1  305.57  4787.6  303.58  4792.6  304.09  4820.4   299.9
  4830.4  299.53  4929.2  299.45  4929.5  298.95    4933  298.95  4933.2  299.45
  5055.8  299.69    5062  301.18  5077.1  302.85  5109.2  303.96  5141.2  304.34
  5219.8  307.48  5232.9  308.43  5263.1  309.28  5269.4  309.95  5323.8  312.96
  5343.2  314.27  5373.5  317.15  5378.8  317.11  5386.8  318.11  5418.9  320.05
#Mann= 7 ,-1 , 0
  4588.6     .07       0  4613.1    .035       0    4685     .05       0
  4929.2     .05       0  4933.2     .05       0  5219.8     .07       0
  5323.8     .05       0
Bank Sta=4929.2,4933.2
XS Rating Curve= 0 ,0
Exp/Cntr=0.3,0.1

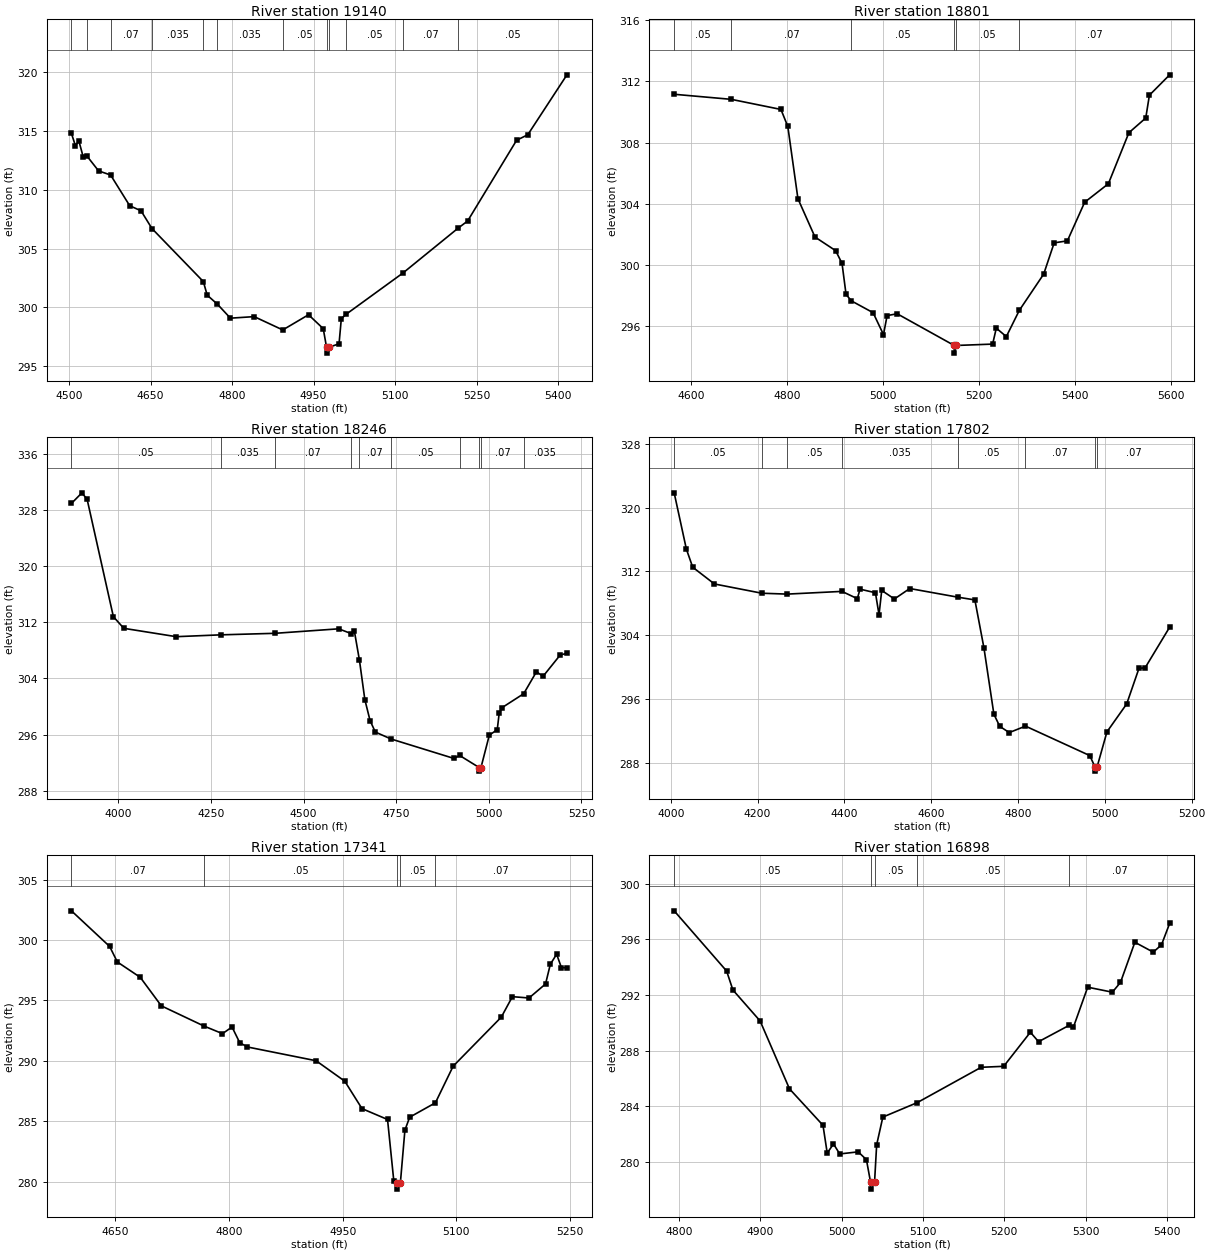
Type RM Length L Ch R = 1 ,19140   ,339,339,339
BEGIN DESCRIPTION:
COOPER CREEK 38.0
END DESCRIPTION:
XS GIS Cut Line= 3
      2451275.01     13609775.01        2450875.       13609475.
      2450475.02     13609574.99
#Sta/Elev= 30
  4504.1  314.78  4511.4  313.74  4517.7  314.15    4526  312.75    4532   312.9
  4554.1   311.6  4576.2  311.25  4611.4  308.64  4632.2  308.21  4652.4   306.7
  4746.9   302.2  4754.1  301.04  4772.8  300.28  4796.8  299.09  4840.6  299.22
  4893.2  298.09  4940.6  299.38  4967.7   298.2  4973.8  296.62  4974.1  296.12
  4978.1  296.62  4996.8  296.91    5001  299.05  5010.1  299.43  5114.3  302.92
  5216.4  306.75  5233.5  307.34  5323.7   314.2  5344.3  314.67  5416.4  319.76
#Mann= 12 ,-1 , 0
  4504.1     .07       0    4532    .035       0  4576.2     .07       0
  4652.4    .035       0  4746.9     .05       0  4772.8    .035       0
  4893.2     .05       0  4973.8    .035       0  4978.1     .05       0
  5010.1     .05       0  5114.3     .07       0  5216.4     .05       0
Bank Sta=4973.8,4978.1
XS Rating Curve= 0 ,0
Exp/Cntr=0.3,0.1

Type RM Length L Ch R = 1 ,18801   ,555,555,555
BEGIN DESCRIPTION:
COOPER CREEK 37.0
END DESCRIPTION:
XS GIS Cut Line= 3
      2451425.02     13609475.01      2451034.03     13609185.04
        2450625.       13608825.
#Sta/Elev= 30
  4565.2  311.15    4684  310.82  4787.5  310.16  4801.8  309.05  4822.9  304.33
  4858.4  301.83  4901.4  300.94  4914.7  300.11  4923.1  298.08  4934.3  297.66
  4979.4  296.89    5001  295.46  5008.6   296.7  5029.5  296.82  5148.3  294.75
  5148.6  294.25  5152.8  294.75  5228.3  294.84  5235.9  295.88  5256.8  295.33
  5283.8  297.04  5334.6  299.41  5356.4  301.45  5383.9  301.58  5419.9   304.1
  5469.3  305.31    5512  308.64  5547.1   309.6  5554.7  311.09  5596.9  312.42
#Mann= 6 ,-1 , 0
  4565.2     .05       0    4684     .07       0  4934.3     .05       0
  5148.3     .05       0  5152.8     .05       0  5283.8     .07       0
Bank Sta=5148.3,5152.8
XS Rating Curve= 0 ,0
Exp/Cntr=0.3,0.1

Type RM Length L Ch R = 1 ,18246   ,444,444,444
BEGIN DESCRIPTION:
COOPER CREEK 36.0
END DESCRIPTION:
XS GIS Cut Line= 3
      2451725.01     13609575.01        2450925.       13608775.
      2450725.04     13608725.01
#Sta/Elev= 30
  3873.2  328.96  3901.5  330.47  3915.6  329.53  3986.4  312.81  4014.6  311.15
  4156.1  309.96  4275.9  310.22  4423.1  310.44  4594.5  311.08  4627.9  310.41
  4636.9  310.76  4650.7  306.57  4665.2  300.98  4679.3  297.99  4693.5  296.36
    4736  295.37  4905.6   292.6  4921.2  293.02  4974.1  291.29  4974.4  290.79
  4978.6  291.29  5001.1  295.91  5022.6  296.71  5027.8  299.03  5035.5  299.84
    5094  301.83  5128.3  304.95  5146.3  304.31  5192.7  307.36  5210.7  307.58
#Mann= 10 ,-1 , 0
  3873.2     .05       0  4275.9    .035       0  4423.1     .07       0
  4627.9     .05       0  4650.7     .07       0    4736     .05       0
  4921.2     .07       0  4974.1     .05       0  4978.6     .07       0
    5094    .035       0
Bank Sta=4974.1,4978.6
XS Rating Curve= 0 ,0
Exp/Cntr=0.3,0.1

Type RM Length L Ch R = 1 ,17802   ,461,461,461
BEGIN DESCRIPTION:
COOPER CREEK 35.0
END DESCRIPTION:
XS GIS Cut Line= 3
      2451875.01     13609375.01        2451275.       13608575.
      2451175.03     13608475.03
#Sta/Elev= 30
  4007.8  321.85  4035.9   314.8  4050.5  312.53  4100.5  310.43  4209.8  309.27
  4268.1  309.16  4394.3   309.5  4429.7  308.59  4435.9  309.78  4471.4  309.33
  4479.7  306.58  4485.9  309.62  4515.1  308.55  4550.5  309.86  4660.8  308.78
  4700.5  308.43  4721.4  302.41  4744.3  294.11  4757.8  292.59  4779.7  291.81
  4817.1  292.62  4965.1  288.93  4977.4  287.48  4977.7  286.98  4981.9  287.48
  5004.7   291.9  5050.2   295.4  5078.5  299.86  5092.7  299.93  5149.2  305.02
#Mann= 8 ,-1 , 0
  4007.8     .05       0  4209.8     .07       0  4268.1     .05       0
  4394.3    .035       0  4660.8     .05       0  4817.1     .07       0
  4977.4     .05       0  4981.9     .07       0
Bank Sta=4977.4,4981.9
XS Rating Curve= 0 ,0
Exp/Cntr=0.3,0.1

Type RM Length L Ch R = 1 ,17341   ,443,443,443
BEGIN DESCRIPTION:
COOPER CREEK 34.0
END DESCRIPTION:
XS GIS Cut Line= 3
      2451775.01     13608925.04        2451725.       13608525.
      2451574.97     13608324.96
#Sta/Elev= 30
  4592.5  302.41  4642.9  299.46    4653  298.18  4683.2  296.91    4711  294.55
  4767.2  292.88  4791.6  292.25  4804.2   292.8  4814.3  291.51  4824.3  291.15
    4915  290.01  4952.8  288.32  4975.5  286.05  5009.2  285.15  5017.5  280.04
  5021.5  279.89  5021.8  279.39  5026.1  279.89  5032.1  284.27  5038.4  285.34
  5072.3  286.53  5095.7  289.56  5159.2  293.62  5173.8  295.31  5195.7   295.2
  5217.5  296.36  5223.8  297.99  5232.1  298.82  5238.4  297.72  5245.7  297.69
#Mann= 5 ,-1 , 0
  4592.5     .07       0  4767.2     .05       0  5021.5     .05       0
  5026.1     .05       0  5072.3     .07       0
Bank Sta=5021.5,5026.1
XS Rating Curve= 0 ,0
Exp/Cntr=0.3,0.1

Type RM Length L Ch R = 1 ,16898   ,463,463,463
BEGIN DESCRIPTION:
COOPER CREEK 33.0
END DESCRIPTION:
XS GIS Cut Line= 3
      2452225.03     13608275.01        2452025.       13608225.
        2451625.       13608175.
#Sta/Elev= 30
  4794.1  298.06  4858.6  293.73  4866.3  292.37  4899.8  290.14  4935.9  285.26
  4977.1  282.64  4982.3  280.64    4990   281.3  4997.7  280.58  5020.4  280.73
  5030.5  280.17  5035.6  278.55    5036  278.05  5040.5  278.55  5043.1  281.24
  5050.7  283.23    5093  284.27  5171.6  286.81  5199.3  286.88  5232.1  289.33
  5242.2  288.65  5279.9  289.83    5285  289.69  5302.6  292.57  5332.9  292.21
  5342.9  292.91  5360.6   295.8  5383.2  295.09  5393.3  295.61  5403.4  297.16
#Mann= 5 ,-1 , 0
  4794.1     .05       0  5035.6     .05       0  5040.5     .05       0
    5093     .05       0  5279.9     .07       0
Bank Sta=5035.6,5040.5
XS Rating Curve= 0 ,0
Exp/Cntr=0.3,0.1

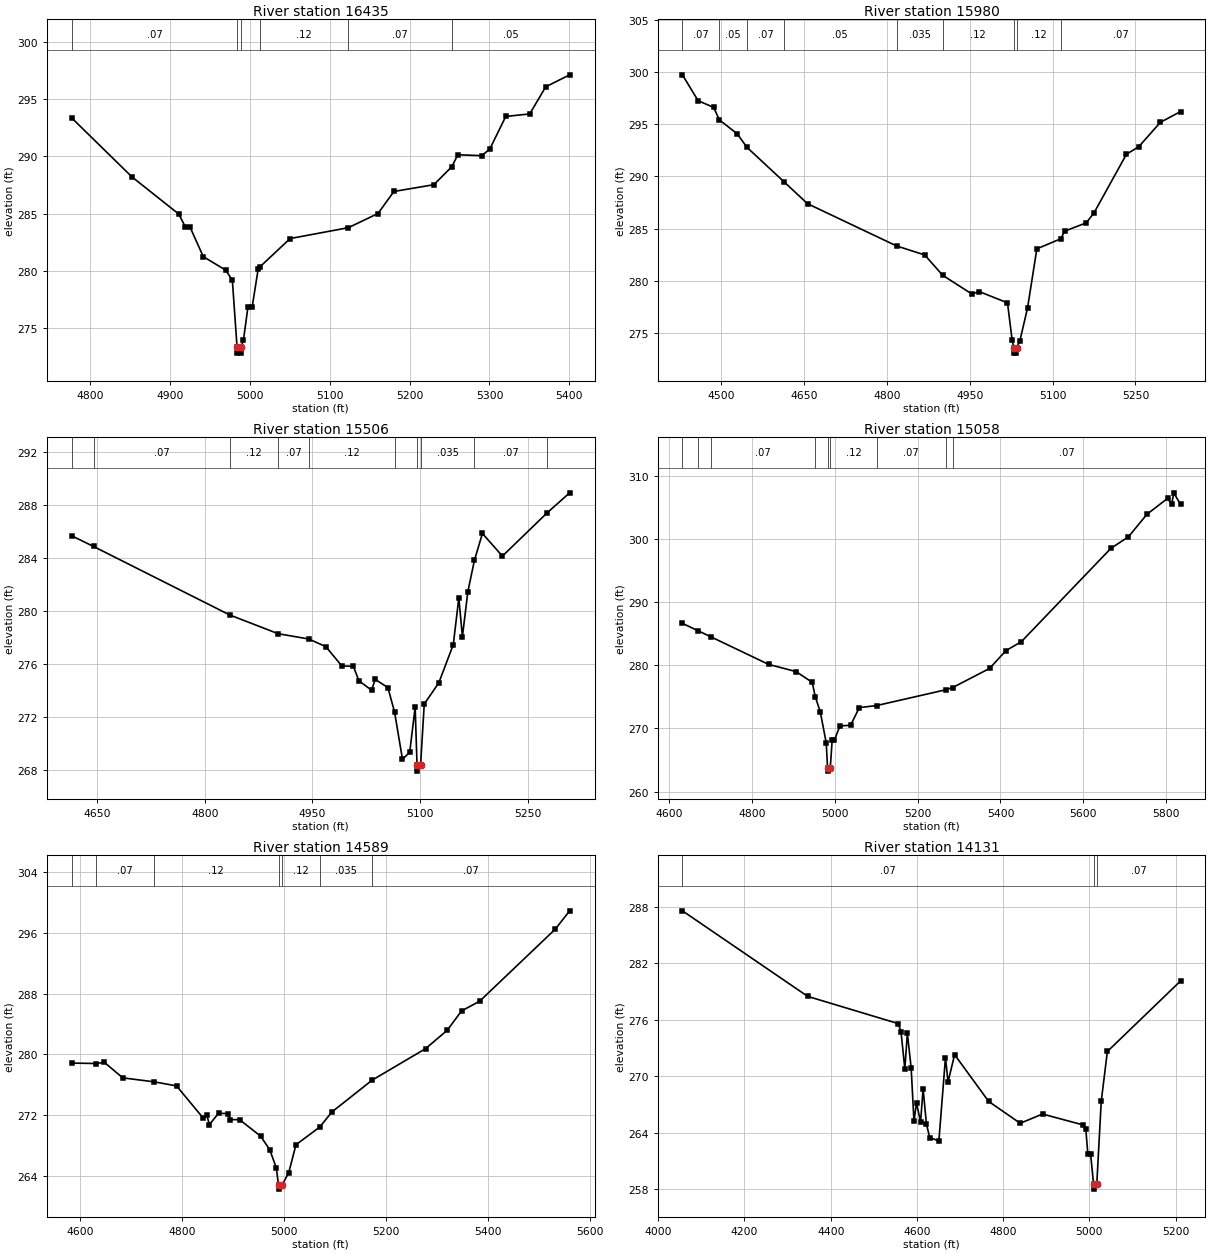
Type RM Length L Ch R = 1 ,16435   ,455,455,455
BEGIN DESCRIPTION:
COOPER CREEK 32.0
END DESCRIPTION:
XS GIS Cut Line= 3
      2452225.01     13607925.01        2452025.       13607825.
      2451625.02       13607825.
#Sta/Elev= 30
  4776.8  293.38  4852.3  288.22    4911  284.96  4919.4  283.82    4925  283.84
  4941.7  281.24  4969.7  280.06  4978.1  279.18    4984   273.3  4984.3   272.8
  4988.5   272.8  4988.9   273.3    4992  273.94  4997.6  276.83  5002.9  276.83
  5010.4  280.15  5012.4  280.33  5050.4  282.82  5123.3  283.77  5160.4  285.01
  5180.4  286.94  5230.4  287.53  5252.8   289.1  5260.4  290.15  5290.4  290.07
  5300.4  290.65  5320.4   293.5  5350.4  293.72  5370.4  296.09  5400.4  297.14
#Mann= 6 ,-1 , 0
  4776.8     .07       0    4984     .05       0  4988.9     .07       0
  5012.4     .12       0  5123.3     .07       0  5252.8     .05       0
Bank Sta=4984,4988.9
XS Rating Curve= 0 ,0
Exp/Cntr=0.3,0.1

Type RM Length L Ch R = 1 ,15980   ,474,474,474
BEGIN DESCRIPTION:
COOPER CREEK 31.0
END DESCRIPTION:
XS GIS Cut Line= 3
      2452475.03     13607825.03        2452075.       13607425.
      2451775.03     13607275.01
#Sta/Elev= 30
  4430.4  299.72  4458.7  297.25    4487   296.6  4497.2  295.41  4529.4  294.08
  4547.2  292.78  4614.3  289.48  4656.7  287.39  4817.7  283.35  4868.8  282.48
  4901.2  280.54  4953.7  278.76  4967.8  278.97  5018.5   277.9  5026.9  274.34
    5030  273.59  5030.4  273.09  5034.6  273.09    5035  273.59  5040.8  274.25
  5054.8  277.42  5071.6  283.07  5114.8  284.03  5121.9  284.76    5161  285.56
    5175  286.51  5233.7  292.12  5256.1  292.85  5295.2  295.18  5331.5   296.2
#Mann= 9 ,-1 , 0
  4430.4     .07       0  4497.2     .05       0  4547.2     .07       0
  4614.3     .05       0  4817.7    .035       0  4901.2     .12       0
    5030     .05       0    5035     .12       0  5114.8     .07       0
Bank Sta=5030,5035
XS Rating Curve= 0 ,0
Exp/Cntr=0.3,0.1

Type RM Length L Ch R = 1 ,15506   ,448,448,448
BEGIN DESCRIPTION:
COOPER CREEK 30.0
END DESCRIPTION:
XS GIS Cut Line= 3
        2452525.       13607325.        2452275.       13607025.
      2451974.96     13607075.01
#Sta/Elev= 30
  4614.1  285.68  4644.7  284.87  4834.9  279.69  4902.2  278.28  4944.9  277.88
  4968.8   277.3  4990.9  275.85  5007.2  275.81  5014.8  274.73  5032.5  274.01
  5037.6  274.83  5055.3  274.21  5064.6  272.36  5075.6   268.8  5085.7  269.32
  5093.3  272.74  5095.9   268.4  5096.2   267.9  5100.9   268.4    5106  272.97
  5126.3  274.57  5146.5  277.46  5154.2  280.98  5159.2  278.06  5166.8  281.45
  5175.9  283.81  5187.1  285.85    5215  284.14  5277.4  287.41  5308.8  288.92
#Mann= 10 ,-1 , 0
  4614.1     .05       0  4644.7     .07       0  4834.9     .12       0
  4902.2     .07       0  4944.9     .12       0  5064.6    .035       0
  5095.9     .05       0  5100.9    .035       0  5175.9     .07       0
  5277.4     .05       0
Bank Sta=5095.9,5100.9
XS Rating Curve= 0 ,0
Exp/Cntr=0.3,0.1

Type RM Length L Ch R = 1 ,15058   ,469,469,469
BEGIN DESCRIPTION:
COOPER CREEK 29.0
END DESCRIPTION:
XS GIS Cut Line= 3
        2452725.     13607124.99        2452625.       13606775.
      2452375.01     13605975.05
#Sta/Elev= 30
  4632.4  286.61  4669.7  285.46  4700.5   284.5  4840.4  280.12  4906.7  278.98
  4945.7  277.28  4953.2  274.96  4965.2  272.59  4979.5  267.69  4982.7  263.73
  4983.2  263.23  4989.2  263.73  4993.8   268.1    4999   268.1  5012.6  270.38
  5038.3  270.49  5059.3  273.28  5101.4  273.61  5267.7   276.1  5284.8  276.46
  5373.6  279.48  5412.9  282.28  5450.6  283.73  5666.9  298.51  5708.8   300.3
  5753.4  303.87  5803.1  306.38  5813.1  305.49  5818.3  307.27  5834.5  305.43
#Mann= 9 ,-1 , 0
  4632.4     .07       0  4669.7     .05       0  4700.5     .07       0
  4953.2     .12       0  4982.7     .05       0  4989.2     .12       0
  5101.4     .07       0  5267.7    .035       0  5284.8     .07       0
Bank Sta=4982.7,4989.2
XS Rating Curve= 0 ,0
Exp/Cntr=0.3,0.1

Type RM Length L Ch R = 1 ,14589   ,458,458,458
BEGIN DESCRIPTION:
COOPER CREEK 28.0
END DESCRIPTION:
XS GIS Cut Line= 3
      2453074.99     13606874.98        2452975.       13606475.
      2452574.98     13606074.98
#Sta/Elev= 30
  4582.9  278.87  4630.5  278.81  4647.3  278.96  4683.4  276.92  4744.4   276.4
    4789  275.86  4840.6  271.68  4848.3  272.05  4853.5  270.77  4871.5  272.24
  4889.5  272.22  4894.7  271.41  4912.7  271.41    4954  269.24    4972  267.45
  4984.9  265.05  4989.3  262.75  4989.8  262.25  4995.9  262.75  5009.3  264.42
  5023.5   268.1  5070.1  270.43  5094.2  272.43  5173.1  276.62    5278  280.77
  5320.5  283.19  5348.7  285.75  5384.1  287.02  5532.6  296.52  5560.9  298.94
#Mann= 7 ,-1 , 0
  4582.9     .05       0  4630.5     .07       0  4744.4     .12       0
  4989.3     .05       0  4995.9     .12       0  5070.1    .035       0
  5173.1     .07       0
Bank Sta=4989.3,4995.9
XS Rating Curve= 0 ,0
Exp/Cntr=0.3,0.1

Type RM Length L Ch R = 1 ,14131   ,415,415,415
BEGIN DESCRIPTION:
COOPER CREEK 27.0
END DESCRIPTION:
XS GIS Cut Line= 3
      2454025.04     13606625.02        2453225.       13606125.
      2453074.98     13605974.98
#Sta/Elev= 30
    4056  287.55  4346.7  278.47  4556.6  275.58  4563.1  274.74    4572  270.77
  4577.9  274.54  4586.7  270.88  4593.2  265.19  4599.1  267.18  4608.5  265.13
  4614.4  268.67  4622.1  264.92  4629.7  263.49    4651  263.12  4666.3  271.98
  4672.2  269.38  4687.5  272.28  4766.5  267.32  4839.7     265  4891.5  265.98
  4985.9  264.82  4991.8  264.43  4996.5  261.78    5003  261.78  5009.9  258.51
  5010.4  258.01  5017.3  258.51  5027.7  267.33  5041.9  272.62  5211.6   280.1
#Mann= 3 ,-1 , 0
    4056     .07       0  5009.9     .05       0  5017.3     .07       0
Bank Sta=5009.9,5017.3
XS Rating Curve= 0 ,0
Exp/Cntr=0.3,0.1

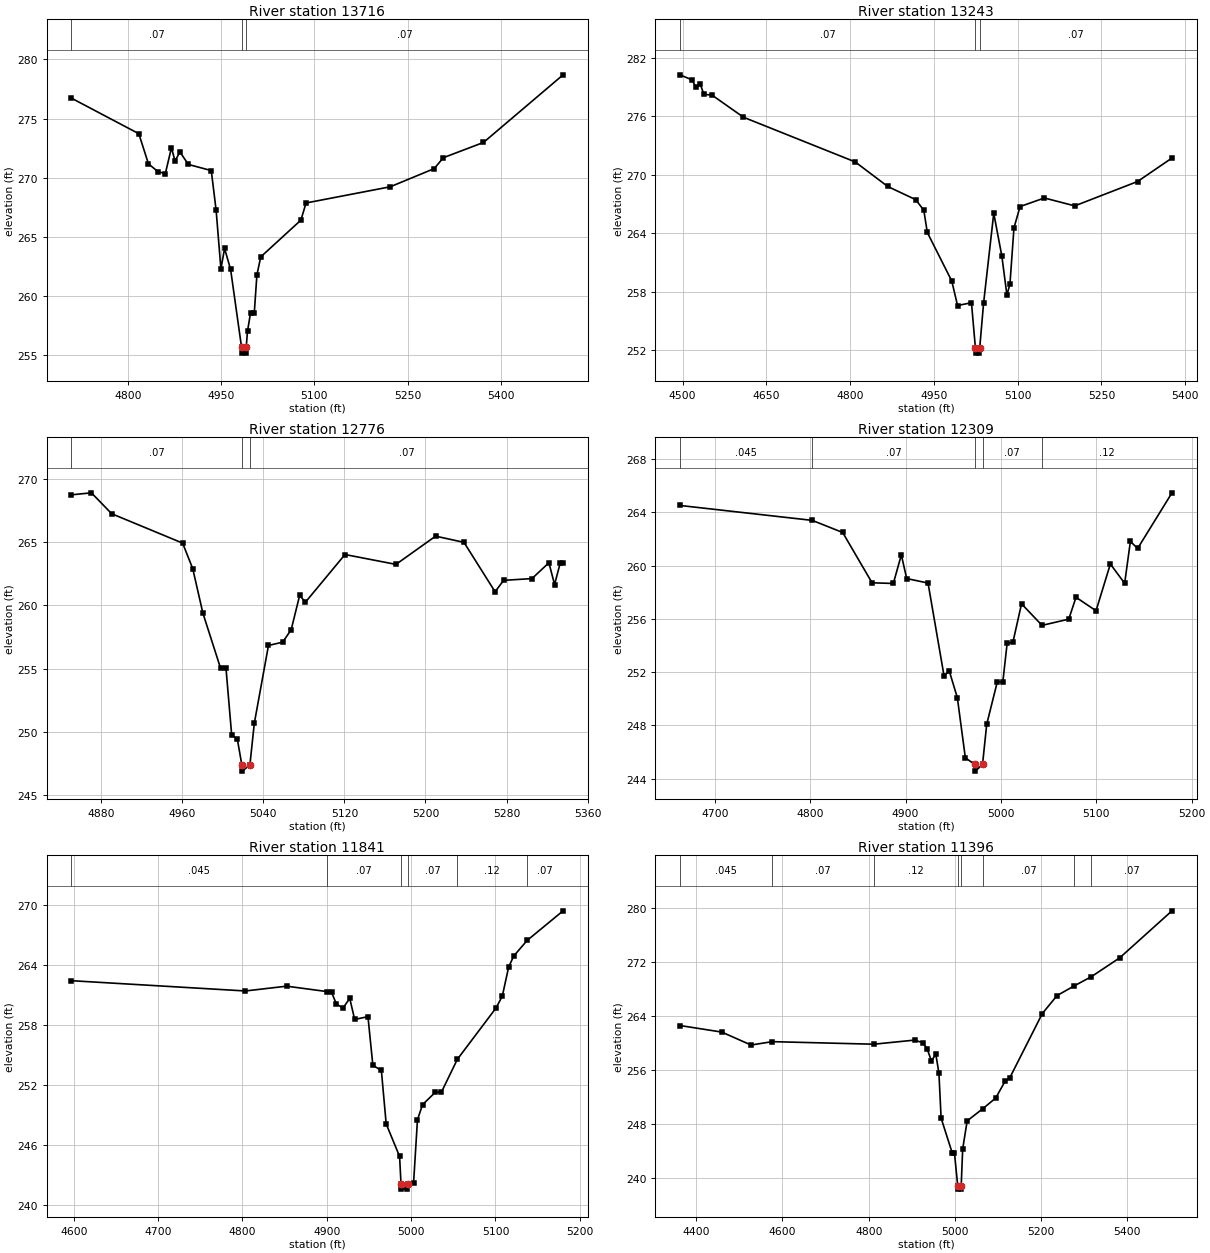
Type RM Length L Ch R = 1 ,13716   ,473,473,473
BEGIN DESCRIPTION:
COOPER CREEK 26.0
END DESCRIPTION:
XS GIS Cut Line= 3
      2453825.03     13606275.02        2453575.       13606125.
      2453174.98     13605824.99
#Sta/Elev= 30
  4708.7  276.74  4817.6  273.72  4833.1  271.17  4848.7   270.5  4860.3  270.35
  4870.1  272.53  4875.9  271.41  4883.7  272.18  4897.3  271.12  4934.2   270.6
    4942  267.24  4949.7  262.29  4955.6  264.01  4965.3  262.24  4982.9  255.66
  4983.4  255.16  4989.9  255.16  4990.4  255.66  4992.5  257.02  4997.4  258.57
  5003.4  258.57  5007.6  261.77  5013.8   263.3  5078.4  266.41  5086.7  267.86
  5222.2  269.23    5293  270.77  5307.6  271.69  5372.2  272.98  5500.3   278.7
#Mann= 3 ,-1 , 0
  4708.7     .07       0  4982.9     .05       0  4990.4     .07       0
Bank Sta=4982.9,4990.4
XS Rating Curve= 0 ,0
Exp/Cntr=0.3,0.1

Type RM Length L Ch R = 1 ,13243   ,467,467,467
BEGIN DESCRIPTION:
COOPER CREEK 25.0
END DESCRIPTION:
XS GIS Cut Line= 3
      2454075.02     13606125.02        2453775.       13605725.
      2453425.02     13605575.01
#Sta/Elev= 30
  4495.4  280.23  4517.3   279.7  4523.6  278.94  4531.9  279.24  4538.1  278.23
  4552.7  278.15    4609  275.88    4809   271.3  4867.3  268.78  4917.3  267.43
  4931.9  266.34  4938.1  264.07  4981.9  259.09  4992.3  256.57  5017.2  256.86
  5024.3  252.19  5024.8  251.69  5031.4  251.69  5031.9  252.19  5038.9  256.81
  5057.1  266.03  5071.6  261.64  5080.7  257.64  5086.1  258.78  5093.3  264.54
  5104.2  266.72  5147.7   267.6  5202.1  266.79  5314.6  269.29  5376.2   271.7
#Mann= 3 ,-1 , 0
  4495.4     .07       0  5024.3     .05       0  5031.9     .07       0
Bank Sta=5024.3,5031.9
XS Rating Curve= 0 ,0
Exp/Cntr=0.3,0.1

Type RM Length L Ch R = 1 ,12776   ,467,467,467
BEGIN DESCRIPTION:
COOPER CREEK 24.0
END DESCRIPTION:
XS GIS Cut Line= 3
        2454175.       13605375.        2454025.       13605375.
      2453725.01     13605225.01
#Sta/Elev= 30
  4850.4  268.72  4870.4  268.88  4890.4  267.23  4960.4  264.91  4970.4  262.89
  4980.4  259.38  4997.9  255.02  5003.2  255.02  5008.8  249.76  5014.4  249.43
  5018.8  247.41  5019.3  246.91  5026.8  247.41  5031.1  250.67  5045.1  256.83
  5059.1  257.09  5067.5  258.07  5075.9  260.79  5081.5  260.24  5120.6  264.01
  5170.9  263.23    5210  265.46    5238  264.97  5268.7  261.07  5277.1  261.97
  5305.1  262.11  5321.8  263.36  5327.4  261.64    5333  263.35  5335.8  263.35
#Mann= 3 ,-1 , 0
  4850.4     .07       0  5018.8     .05       0  5026.8     .07       0
Bank Sta=5018.8,5026.8
XS Rating Curve= 0 ,0
Exp/Cntr=0.3,0.1

Type RM Length L Ch R = 1 ,12309   ,468,468,468
BEGIN DESCRIPTION:
COOPER CREEK 23.0
END DESCRIPTION:
XS GIS Cut Line= 3
      2454275.02     13605075.01        2453975.       13604925.
      2453825.01     13604825.01
#Sta/Elev= 30
  4663.6  264.52  4802.2   263.4  4834.1  262.49  4864.9  258.71  4887.2  258.66
  4895.6  260.81  4901.2  259.03  4923.6  258.69  4940.3  251.74  4945.9  252.07
  4954.3  250.08  4962.7  245.56  4972.6  245.06  4973.1  244.56  4980.7  245.06
  4985.1  248.08  4996.2  251.27    5002  251.27  5006.5  254.16  5012.6  254.26
  5021.6  257.13  5043.1  255.51  5071.1  255.98  5078.7  257.62  5099.7  256.61
  5114.7  260.12  5129.7  258.67  5135.7  261.82  5143.3  261.29  5179.3  265.47
#Mann= 5 ,-1 , 0
  4663.6    .045       0  4802.2     .07       0  4972.6     .05       0
  4980.7     .07       0  5043.1     .12       0
Bank Sta=4972.6,4980.7
XS Rating Curve= 0 ,0
Exp/Cntr=0.3,0.1

Type RM Length L Ch R = 1 ,11841   ,445,445,445
BEGIN DESCRIPTION:
COOPER CREEK 22.0
END DESCRIPTION:
XS GIS Cut Line= 3
      2454375.01     13604875.02        2454175.       13604525.
      2454025.01     13604425.01
#Sta/Elev= 30
  4596.8  262.45  4803.4  261.42  4852.4   261.9  4900.1  261.36  4905.6   261.3
  4911.4   260.1  4919.3  259.72  4927.2  260.68    4933  258.57  4948.8  258.85
  4954.6  253.98  4964.7  253.47  4970.4  248.12  4986.3  244.86    4988  242.09
  4988.5  241.59  4995.6  241.59  4996.1  242.09  5002.9  242.21  5007.5  248.53
  5013.5  250.04  5028.5  251.27    5036  251.31  5054.8  254.58  5100.6  259.71
  5108.1   260.9  5115.6   263.8  5121.6  264.91  5137.6  266.48  5180.2  269.44
#Mann= 6 ,-1 , 0
  4596.8    .045       0  4900.1     .07       0    4988     .05       0
  4996.1     .07       0  5054.8     .12       0  5137.6     .07       0
Bank Sta=4988,4996.1
XS Rating Curve= 0 ,0
Exp/Cntr=0.3,0.1

Type RM Length L Ch R = 1 ,11396   ,372,372,372
BEGIN DESCRIPTION:
COOPER CREEK 21.0
END DESCRIPTION:
XS GIS Cut Line= 3
      2454576.79     13604850.45        2454475.       13604225.
      2454010.81     13604020.55
#Sta/Elev= 30
  4362.4  262.59  4459.1  261.62  4527.1   259.7  4576.3   260.2  4811.9  259.82
  4906.3  260.43  4925.2  260.04  4935.3  259.17  4945.4  257.35  4955.6  258.33
  4962.8  255.56  4967.9  248.86  4993.6  243.71  4998.8  243.71  5006.4  238.83
  5006.9  238.33    5014  238.33  5014.5  238.83  5017.9  244.27  5028.3  248.45
    5064  250.23  5094.4  251.83  5116.3  254.33  5127.1  254.83  5202.6  264.37
  5236.9  267.04  5277.2  268.49  5316.5  269.84  5382.3  272.64  5503.3   279.6
#Mann= 8 ,-1 , 0
  4362.4    .045       0  4576.3     .07       0  4811.9     .12       0
  5006.4     .05       0  5014.5     .12       0    5064     .07       0
  5277.2     .12       0  5316.5     .07       0
Bank Sta=5006.4,5014.5
XS Rating Curve= 0 ,0
Exp/Cntr=0.3,0.1