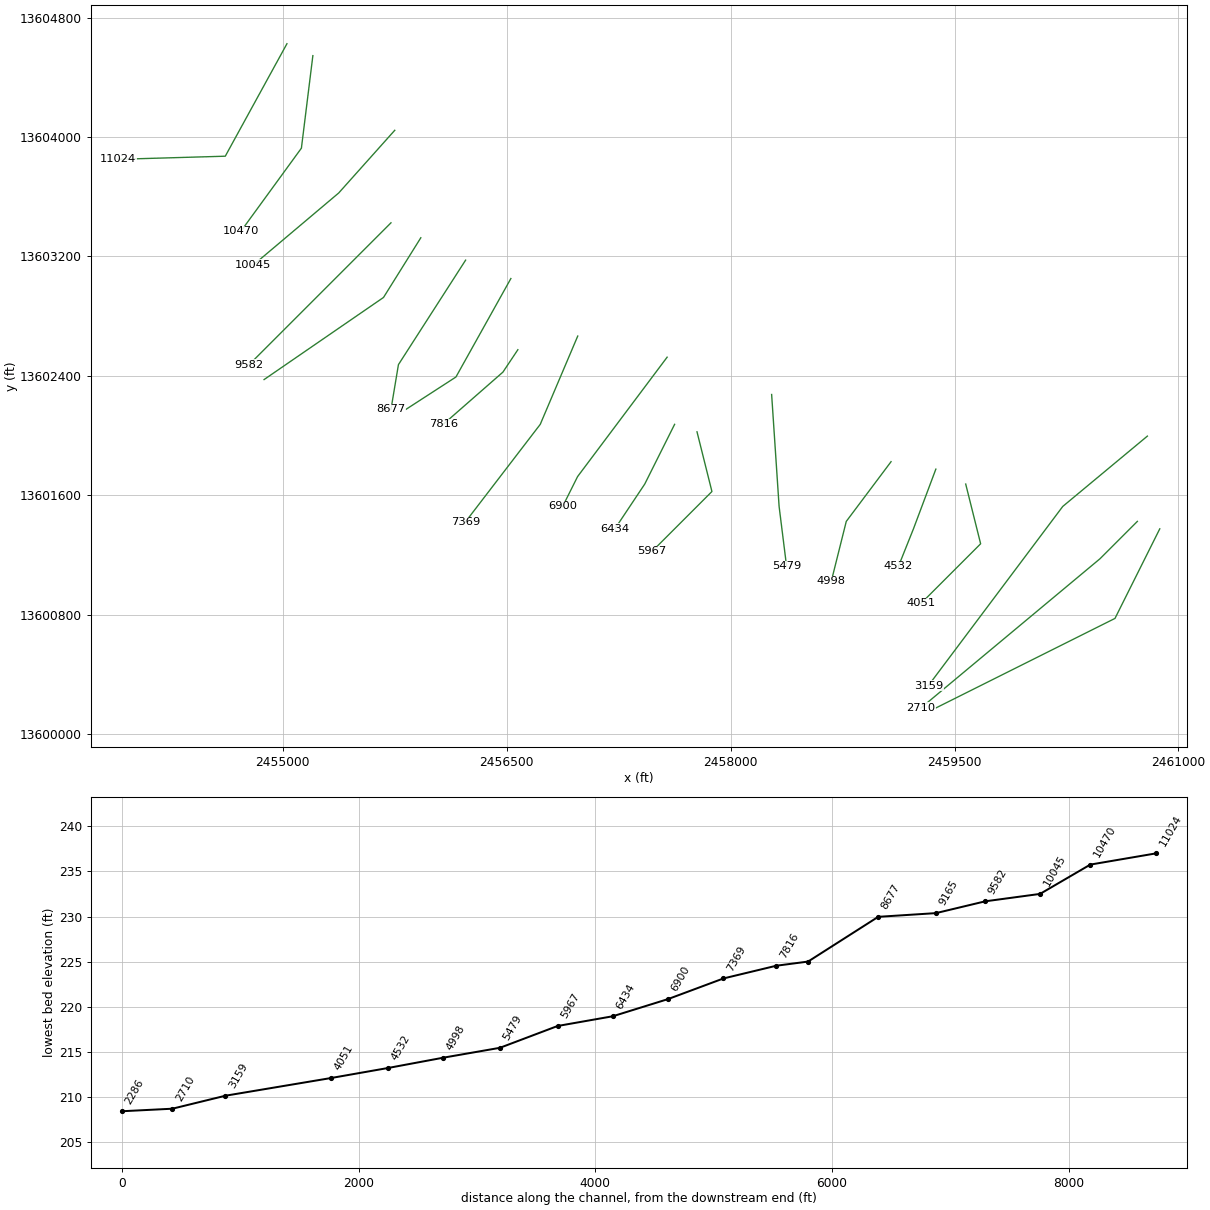
HEC-RAS study COOPER CREEK.prj: COOPER CREEK Base Level Engineering

--- COOPER CREEK.g01 (geometry) --- (continued)

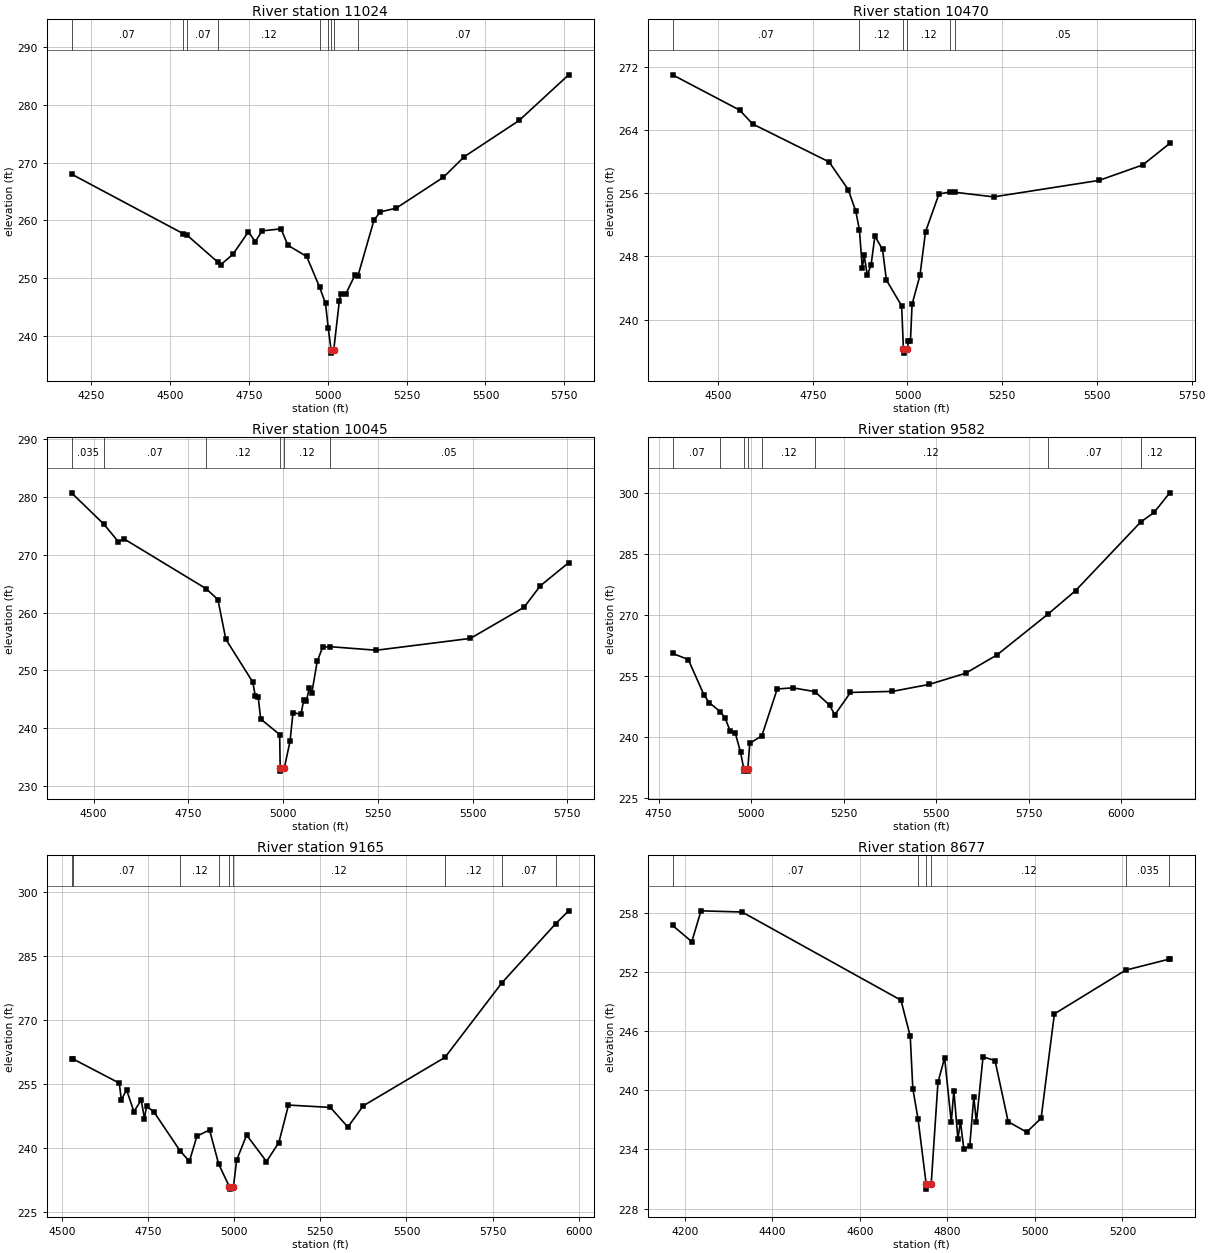
Type RM Length L Ch R = 1 ,11024   ,554,554,554
BEGIN DESCRIPTION:
X18508
END DESCRIPTION:
XS GIS Cut Line= 3
      2455028.16     13604624.69      2454614.98     13603871.25
      2453898.08     13603850.47
#Sta/Elev= 30
  4187.4  268.04  4540.8  257.74  4554.5  257.42  4650.9   252.8  4661.1  252.36
    4699  254.12  4748.3  258.04  4770.1  256.33  4791.9   258.2  4851.7  258.55
  4873.5   255.7  4933.2  253.76  4973.9  248.46  4992.9  245.61  5001.4  241.35
  5010.6   237.5  5011.1     237  5018.8   237.5  5036.5  245.96  5041.7  247.34
  5056.7  247.22  5085.7  250.47  5095.5  250.36  5146.7   260.1  5166.7  261.49
  5216.7  262.13  5366.8   267.5  5433.3  271.08  5606.9  277.35  5763.9  285.26
#Mann= 9 ,-1 , 0
  4187.4     .07       0  4540.8     .12       0  4554.5     .07       0
  4650.9     .12       0  4973.9     .07       0  5001.4     .12       0
  5010.6     .05       0  5018.8     .12       0  5095.5     .07       0
Bank Sta=5010.6,5018.8
XS Rating Curve= 0 ,0
Exp/Cntr=0.3,0.1

Type RM Length L Ch R = 1 ,10470   ,425,425,425
BEGIN DESCRIPTION:
COOPER CREEK 20.0
END DESCRIPTION:
XS GIS Cut Line= 3
      2455201.79     13604544.89        2455125.       13603925.
      2454720.37     13603369.46
#Sta/Elev= 30
  4380.2  271.01  4556.9  266.55  4591.7  264.78  4793.2  259.98  4843.6  256.48
  4863.8  253.72  4873.3  251.35  4880.8  246.58  4885.9  248.13    4894  245.62
  4904.1  246.95  4914.1  250.58  4934.3  248.89  4944.4  245.02  4984.7  241.75
  4989.4  236.26  4989.9  235.76    5000  236.26  5002.3  237.27  5007.9  237.27
  5012.2  241.94    5033  245.61  5047.7  251.13  5083.2  255.91  5112.4  256.17
  5125.9  256.13  5227.5  255.55  5505.9  257.64    5621   259.6  5692.1  262.32
#Mann= 6 ,-1 , 0
  4380.2     .07       0  4873.3     .12       0  4989.4     .05       0
    5000     .12       0  5112.4     .07       0  5125.9     .05       0
Bank Sta=4989.4,5000
XS Rating Curve= 0 ,0
Exp/Cntr=0.3,0.1

Type RM Length L Ch R = 1 ,10045   ,463,463,463
BEGIN DESCRIPTION:
COOPER CREEK 19.0
END DESCRIPTION:
XS GIS Cut Line= 3
      2455750.39     13604044.86        2455375.       13603625.
      2454802.48     13603142.08
#Sta/Elev= 30
  4441.6  280.74  4527.6  275.26  4565.5  272.25  4579.7  272.78  4796.8  264.13
    4828  262.24  4848.9  255.36    4920  247.94  4926.7  245.51  4934.2  245.42
  4940.9  241.54    4991  238.85  4992.4  233.01  4992.9  232.51  5003.1  233.01
  5018.5  237.73  5026.2  242.67  5047.1  242.35  5054.8  244.92  5061.4  244.68
  5069.1  246.83  5075.7  246.01    5090  251.51  5104.3  253.97  5123.6  254.08
    5246  253.46  5494.4  255.51  5636.1  260.91    5679  264.63  5753.8  268.63
#Mann= 6 ,-1 , 0
  4441.6    .035       0  4527.6     .07       0  4796.8     .12       0
  4992.4     .05       0  5003.1     .12       0  5123.6     .05       0
Bank Sta=4992.4,5003.1
XS Rating Curve= 0 ,0
Exp/Cntr=0.3,0.1

Type RM Length L Ch R = 1 ,9582    ,417,417,417
BEGIN DESCRIPTION:
COOPER CREEK 18.0
END DESCRIPTION:
XS GIS Cut Line= 3
      2455724.99     13603424.99        2455575.       13603275.
        2454775.       13602475.
#Sta/Elev= 30
  4787.9  260.59  4830.3   259.1  4872.7  250.42  4886.9  248.52    4917  246.26
  4929.3  244.82  4943.5  241.57  4957.6  240.98  4971.7  236.29  4980.5  232.19
    4981  231.69  4990.7  231.69  4991.2  232.19  4996.5  238.53  5029.2  240.36
  5070.7  251.86  5113.2  252.14  5172.6  251.21  5212.2  247.88  5226.3  245.51
  5268.7  251.01  5381.9  251.27  5480.9  252.97  5579.9  255.73  5664.7  260.23
  5801.8   270.2  5876.8     276  6052.9  292.85    6089   295.2  6131.4  300.03
#Mann= 8 ,-1 , 0
  4787.9     .07       0    4917     .12       0  4980.5     .05       0
  4991.2     .12       0  5029.2     .12       0  5172.6     .12       0
  5801.8     .07       0  6052.9     .12       0
Bank Sta=4980.5,4991.2
XS Rating Curve= 0 ,0
Exp/Cntr=0.3,0.1

Type RM Length L Ch R = 1 ,9165    ,488,488,488
BEGIN DESCRIPTION:
COOPER CREEK 17.0
END DESCRIPTION:
XS GIS Cut Line= 3
        2455925.       13603325.        2455675.       13602925.
      2454875.02     13602375.01
#Sta/Elev= 30
  4528.2  260.98  4531.6  260.95  4666.8  255.24  4672.7  251.31    4688  253.65
  4709.2  248.56  4730.4  251.26  4739.9  246.91  4745.8   249.8    4767  248.53
  4843.5  239.32  4870.2  236.91    4892   242.8  4928.6  244.27  4955.2  236.26
  4986.5  230.88    4987  230.38  4997.9  230.88  5007.3  237.18  5036.3  243.06
  5093.9  236.85  5129.8  241.31  5157.7  250.09  5279.3  249.54    5330  244.93
  5374.7  249.92  5611.7  261.27  5776.7  278.73    5933  292.62  5970.7  295.64
#Mann= 9 ,-1 , 0
  4528.2     .05       0  4531.6     .07       0  4843.5     .12       0
  4955.2     .12       0  4986.5     .05       0  4997.9     .12       0
  5611.7     .12       0  5776.7     .07       0    5933     .05       0
Bank Sta=4986.5,4997.9
XS Rating Curve= 0 ,0
Exp/Cntr=0.3,0.1

Type RM Length L Ch R = 1 ,8677    ,593,593,593
BEGIN DESCRIPTION:
COOPER CREEK 16.0
END DESCRIPTION:
XS GIS Cut Line= 3
      2456224.97     13603174.96        2455775.       13602475.
      2455724.99     13602174.96
#Sta/Elev= 30
  4171.9  256.71  4215.8  255.06  4236.9  258.19  4330.7  258.07  4693.9  249.13
  4715.1  245.48    4721  240.17    4733  237.07  4751.6  230.47  4752.1  229.97
    4763  230.47  4778.5   240.8  4793.7  243.29  4808.9  236.76  4814.8  239.97
    4824  235.09    4830  236.77  4837.6  234.04  4851.1  234.32  4860.4  239.34
  4866.3  236.74  4881.5  243.38  4908.9  243.01    4939  236.81  4981.2  235.75
  5014.2  237.15  5044.6  247.74  5207.3  252.17  5307.7   253.3  5308.2   253.3
#Mann= 6 ,-1 , 0
  4171.9     .07       0    4733     .12       0  4751.6     .05       0
    4763     .12       0  5207.3    .035       0  5307.7     .07       0
Bank Sta=4751.6,4763
XS Rating Curve= 0 ,0
Exp/Cntr=0.3,0.1

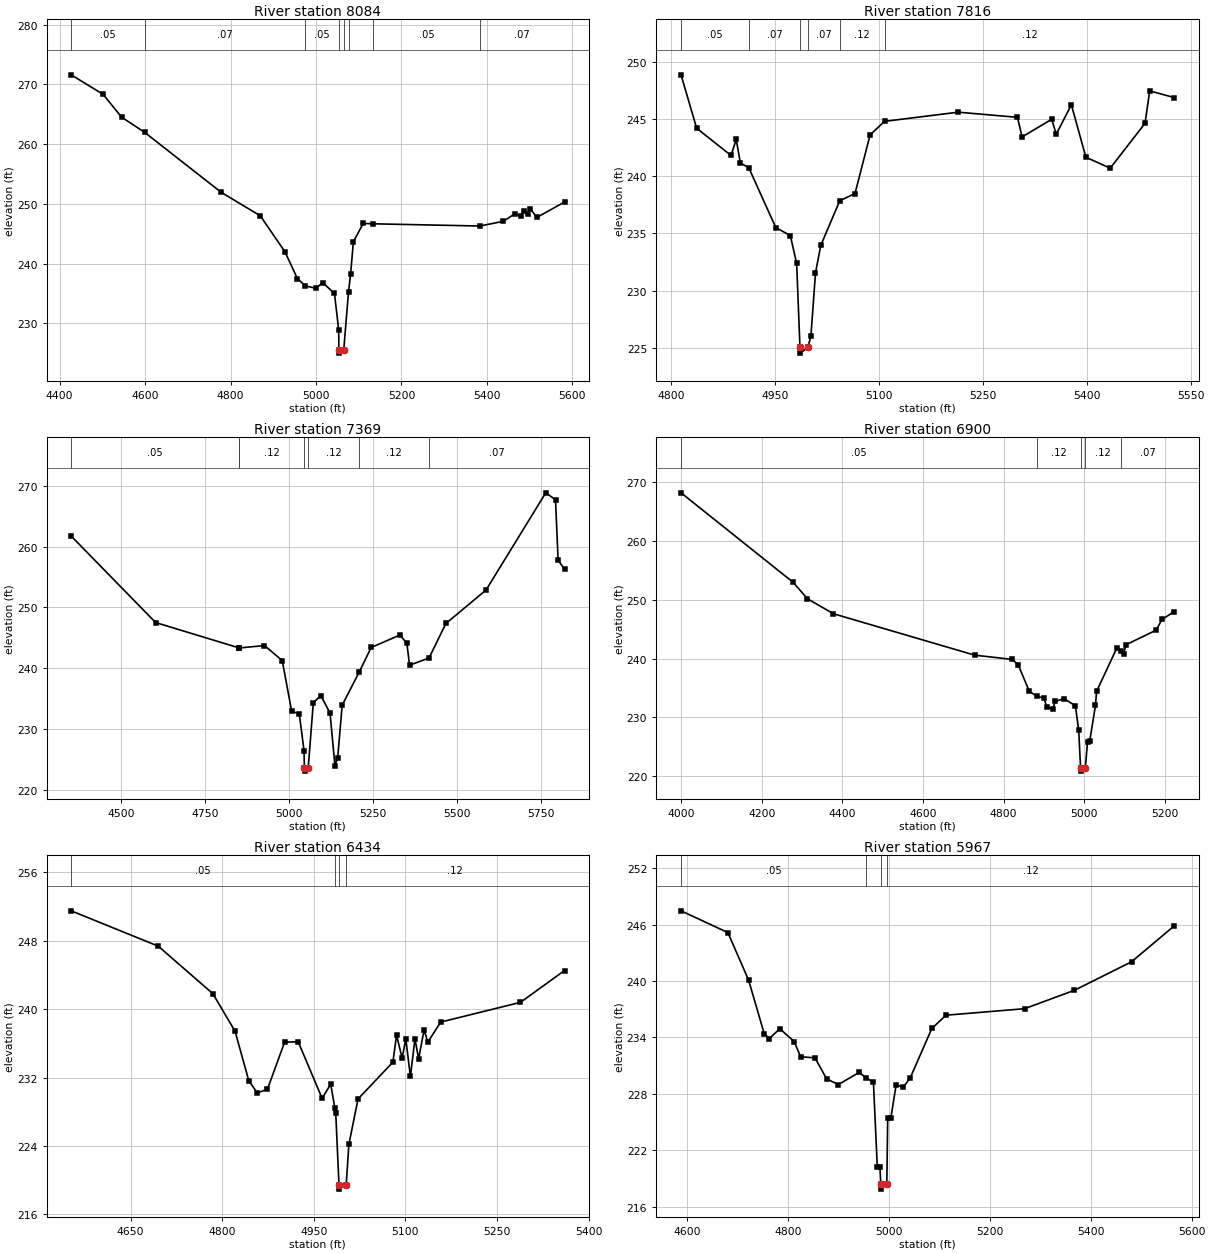
Type RM Length L Ch R = 1 ,8084    ,268,268,268
BEGIN DESCRIPTION:
COOPER CREEK 15.0
END DESCRIPTION:
XS GIS Cut Line= 3
      2456528.17      13603051.8      2456160.12     13602392.08
      2455825.02     13602175.01
#Sta/Elev= 30
    4427  271.62  4501.6  268.35    4545  264.53  4598.8  261.99  4778.3  251.93
  4869.5  248.02  4927.2     242  4956.4   237.5  4975.3  236.26  4999.8  235.88
  5015.8  236.81  5043.2  235.01  5053.1  228.91  5053.5  225.51    5054  225.01
  5064.9  225.51  5076.1  235.28  5080.9  238.19  5087.5  243.65  5110.4  246.73
  5133.8  246.67  5383.5   246.3  5438.3  247.08  5465.4  248.34  5480.5  247.95
  5486.5  248.82  5495.7  248.25  5501.6  249.22  5516.8  247.73  5581.7  250.32
#Mann= 8 ,-1 , 0
    4427     .05       0  4598.8     .07       0  4975.3     .05       0
  5053.5     .05       0  5064.9     .05       0  5076.1     .12       0
  5133.8     .05       0  5383.5     .07       0
Bank Sta=5053.5,5064.9
XS Rating Curve= 0 ,0
Exp/Cntr=0.3,0.1

Type RM Length L Ch R = 1 ,7816    ,447,447,447
BEGIN DESCRIPTION:
COOPER CREEK 14.0
END DESCRIPTION:
XS GIS Cut Line= 3
        2456575.       13602575.        2456475.       13602425.
      2456074.99     13602074.99
#Sta/Elev= 30
  4814.9  248.84  4837.4  244.18    4887   241.8  4894.5   243.2  4900.5  241.14
  4912.5  240.75  4951.6  235.51  4972.6  234.81  4981.7  232.38  4986.5  225.05
    4987  224.55  4997.9  225.05  5002.3  226.05  5008.9  231.55  5016.5  233.95
  5043.9  237.85  5065.9  238.48  5087.7   243.6  5108.5  244.78  5214.9  245.58
  5300.3  245.13    5307  243.42  5349.7  244.96  5356.3  243.66  5378.1  246.23
    5399  241.65  5434.1  240.69  5484.4  244.61  5491.1  247.44  5526.7  246.85
#Mann= 6 ,-1 , 0
  4814.9     .05       0  4912.5     .07       0  4986.5     .05       0
  4997.9     .07       0  5043.9     .12       0  5108.5     .12       0
Bank Sta=4986.5,4997.9
XS Rating Curve= 0 ,0
Exp/Cntr=0.3,0.1

Type RM Length L Ch R = 1 ,7369    ,469,469,469
BEGIN DESCRIPTION:
COOPER CREEK 13.0
END DESCRIPTION:
XS GIS Cut Line= 3
      2456976.07     13602666.34        2456725.       13602075.
      2456222.69     13601419.96
#Sta/Elev= 30
  4352.4  261.71  4603.7  247.52  4852.6  243.35  4852.9  243.35  4927.5  243.75
  4980.3  241.29  5008.4  232.97  5031.1  232.54  5045.2   226.5  5046.2  223.64
  5046.7  223.14  5057.6  223.64  5072.8  234.38  5095.5  235.53  5122.6  232.66
  5137.1  224.05  5145.4  225.35  5158.7  233.96  5209.5  239.41  5245.1  243.43
  5330.3  245.47  5351.1  244.15  5359.3  240.52  5417.2  241.71  5467.4  247.37
  5587.1  252.88  5764.4  268.81  5793.5  267.68  5801.3  257.74  5820.3   256.3
#Mann= 7 ,-1 , 0
  4352.4     .05       0  4852.6     .07       0  4852.9     .12       0
  5046.2     .05       0  5057.6     .12       0  5209.5     .12       0
  5417.2     .07       0
Bank Sta=5046.2,5057.6
XS Rating Curve= 0 ,0
Exp/Cntr=0.3,0.1

Type RM Length L Ch R = 1 ,6900    ,466,466,466
BEGIN DESCRIPTION:
COOPER CREEK 12.0
END DESCRIPTION:
XS GIS Cut Line= 3
      2457574.97     13602524.97        2456975.       13601725.
      2456874.98     13601524.97
#Sta/Elev= 30
    4000  268.19  4278.1  252.96  4313.5  250.17  4378.1  247.62  4728.1  240.58
  4821.8  239.85  4836.4  238.92  4863.5  234.46  4882.4  233.56    4900  233.29
  4907.2  231.77  4921.8   231.4  4928.1  232.71    4950  233.18  4978.1  231.96
  4986.4  227.78    4991  221.35  4991.5  220.85  5002.7  221.35  5008.3  225.87
  5013.9  226.04  5027.9  232.03  5030.7  234.42    5081   241.8  5090.9  241.34
  5097.8  240.72  5103.4  242.34  5178.8  244.84  5192.8  246.65  5223.6  247.99
#Mann= 5 ,-1 , 0
    4000     .05       0  4882.4     .12       0    4991     .05       0
  5002.7     .12       0  5090.9     .07       0
Bank Sta=4991,5002.7
XS Rating Curve= 0 ,0
Exp/Cntr=0.3,0.1

Type RM Length L Ch R = 1 ,6434    ,467,467,467
BEGIN DESCRIPTION:
COOPER CREEK 11.0
END DESCRIPTION:
XS GIS Cut Line= 3
        2457625.       13602075.        2457425.       13601675.
      2457224.98     13601374.97
#Sta/Elev= 30
  4552.8  251.49  4695.3  247.36  4784.8   241.8  4821.1  237.41  4843.5  231.65
  4857.5  230.19  4874.2  230.64  4902.2  236.13  4924.5  236.18  4963.7  229.56
  4977.7  231.23  4984.5  228.43    4986  227.81  4991.3  219.45  4991.8  218.95
  5003.1  219.45  5007.5  224.18  5022.5  229.49  5079.6   233.8  5085.6  236.95
  5094.7  234.26  5100.7  236.53  5108.2  232.12  5115.7  236.51  5121.7  234.19
  5130.7  237.59  5136.7  236.13  5157.8  238.48  5288.5  240.79  5360.6  244.51
#Mann= 4 ,-1 , 0
  4552.8     .05       0  4984.5     .12       0  4991.3     .05       0
  5003.1     .12       0
Bank Sta=4991.3,5003.1
XS Rating Curve= 0 ,0
Exp/Cntr=0.3,0.1

Type RM Length L Ch R = 1 ,5967    ,488,488,488
BEGIN DESCRIPTION:
COOPER CREEK 10.0
END DESCRIPTION:
XS GIS Cut Line= 3
        2457775.     13602024.99        2457875.       13601625.
      2457474.99     13601224.99
#Sta/Elev= 30
  4587.7  247.47  4680.5  245.16  4721.7  240.09  4752.6   234.4  4762.9  233.89
  4783.5  234.93  4811.9  233.57  4824.8  231.94  4853.1  231.84  4876.3   229.6
  4899.5  228.99  4940.7  230.28  4955.2  229.69  4969.1  229.22  4976.8  220.18
    4982  220.21  4983.7  218.37  4984.2  217.87  4995.6  218.37  4997.4  225.39
  5003.5  225.39  5014.1  228.96  5028.3  228.72  5042.4  229.74  5084.9  234.96
  5113.1  236.37  5268.7  237.06  5367.7  239.02  5480.8  242.05  5565.7  245.88
#Mann= 4 ,-1 , 0
  4587.7     .05       0  4955.2     .12       0  4983.7     .05       0
  4995.6     .12       0
Bank Sta=4983.7,4995.6
XS Rating Curve= 0 ,0
Exp/Cntr=0.3,0.1

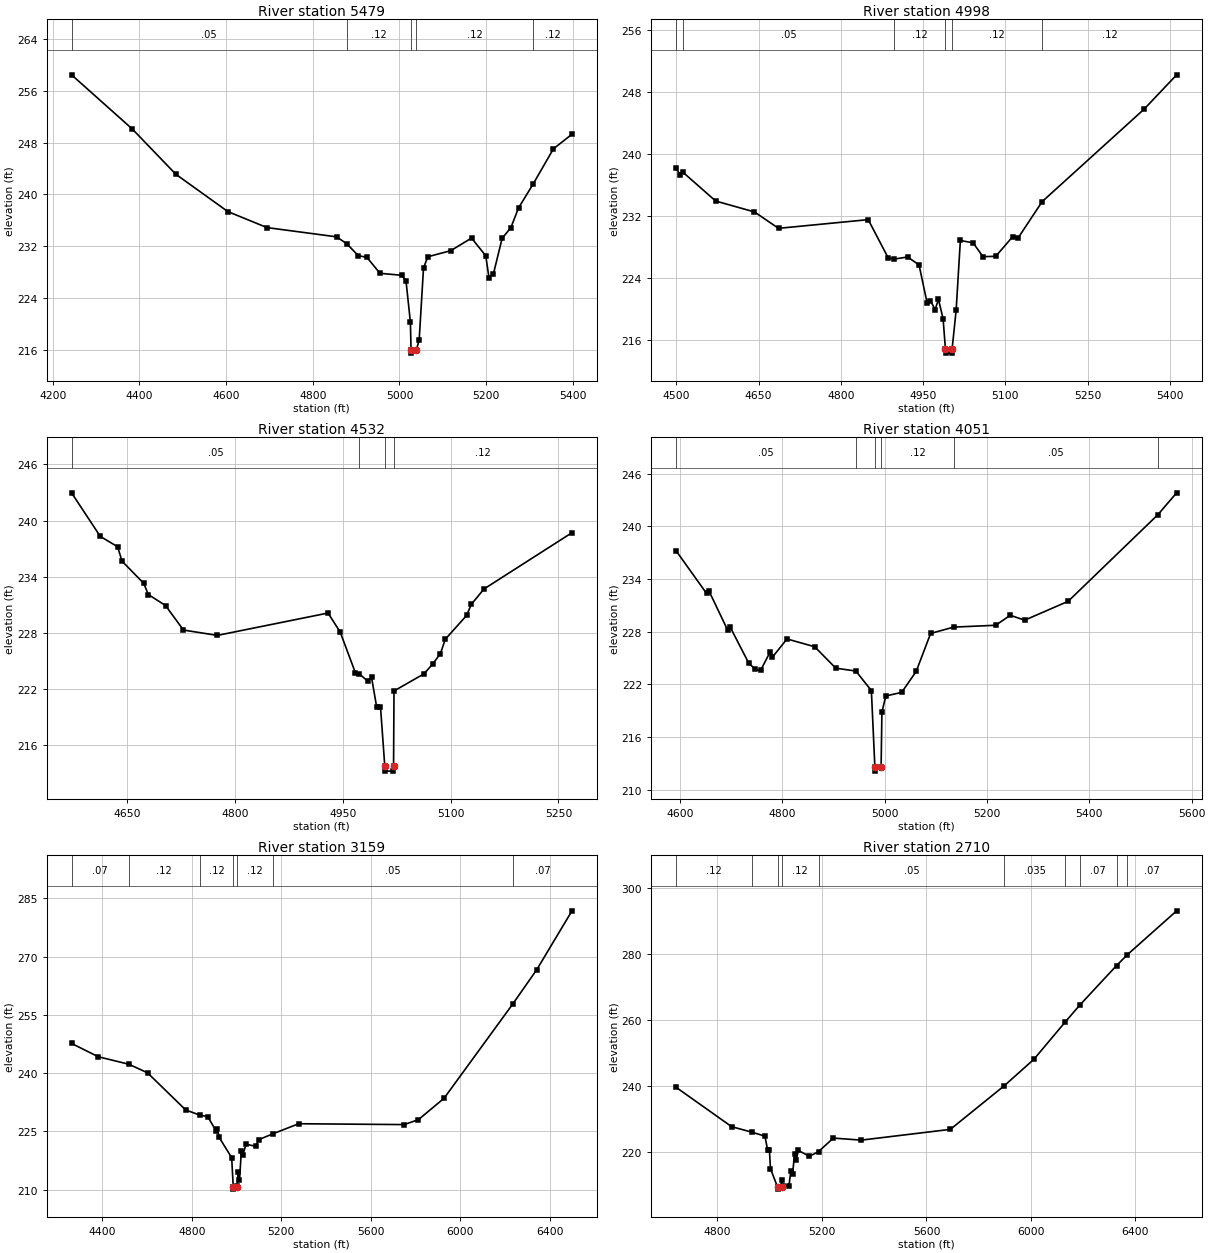
Type RM Length L Ch R = 1 ,5479    ,481,481,481
BEGIN DESCRIPTION:
COOPER CREEK 9.0
END DESCRIPTION:
XS GIS Cut Line= 3
        2458275.     13602275.03        2458325.       13601525.
        2458375.     13601125.01
#Sta/Elev= 30
  4243.3   258.5  4383.6  250.11  4483.9  243.12  4604.1  237.34  4694.3  234.87
  4854.7  233.44  4878.7  232.36  4904.8  230.53  4924.8  230.27  4954.9   227.8
  5005.1  227.49  5015.1   226.6  5025.2  220.25  5026.7  215.95  5027.2  215.45
  5038.8  215.95  5045.4  217.44  5055.5  228.64  5065.5  230.36  5118.4   231.3
  5166.3  233.25  5199.1  230.51  5206.6  227.09  5216.7  227.68  5236.9  233.21
    5257  234.85  5274.7  237.91  5308.1  241.57  5355.3  247.06  5398.1  249.31
#Mann= 5 ,-1 , 0
  4243.3     .05       0  4878.7     .12       0  5026.7     .05       0
  5038.8     .12       0  5308.1     .12       0
Bank Sta=5026.7,5038.8
XS Rating Curve= 0 ,0
Exp/Cntr=0.3,0.1

Type RM Length L Ch R = 1 ,4998    ,466,466,466
BEGIN DESCRIPTION:
COOPER CREEK 8.0
END DESCRIPTION:
XS GIS Cut Line= 3
        2459075.     13601825.01        2458775.       13601425.
        2458675.     13601025.02
#Sta/Elev= 30
  4499.9  238.17  4507.2  237.28  4512.2  237.64  4571.8  233.94  4642.6  232.53
  4686.4  230.42  4849.9  231.54  4886.4  226.61  4897.3  226.46  4921.8  226.73
  4942.6  225.71  4957.2  220.84  4963.4   221.1  4971.8  219.96    4978  221.26
  4986.4  218.79  4990.7  214.85  4991.2  214.35  5002.3  214.35  5002.8  214.85
  5010.2  219.87  5017.9  228.86  5041.1  228.55  5059.2  226.77  5082.4  226.82
  5113.3  229.35  5123.6  229.23    5167  233.86  5352.9  245.77  5412.2  250.19
#Mann= 6 ,-1 , 0
  4499.9     .07       0  4512.2     .05       0  4897.3     .12       0
  4990.7     .05       0  5002.8     .12       0    5167     .12       0
Bank Sta=4990.7,5002.8
XS Rating Curve= 0 ,0
Exp/Cntr=0.3,0.1

Type RM Length L Ch R = 1 ,4532    ,481,481,481
BEGIN DESCRIPTION:
COOPER CREEK 7.0
END DESCRIPTION:
XS GIS Cut Line= 3
      2459374.99     13601774.97        2459225.       13601375.
      2459125.01     13601125.02
#Sta/Elev= 30
  4572.5  242.96  4612.5   238.3  4636.5   237.2  4642.8  235.65    4673  233.28
  4679.3  232.09  4703.3  230.91  4728.2  228.29  4775.4  227.72  4929.4  230.11
  4946.3  228.08  4967.6   223.7    4973   223.6  4984.5  222.84  4989.9  223.26
    4997   220.1  5002.4   220.1  5008.4  213.71  5008.9  213.21  5020.1  213.21
  5020.6  213.71  5021.2  221.78  5062.9  223.61  5075.1  224.66  5085.8  225.78
  5092.6  227.31  5122.2  229.85  5128.9  231.05  5146.4  232.68  5268.9   238.7
#Mann= 4 ,-1 , 0
  4572.5     .05       0    4973     .12       0  5008.4     .05       0
  5020.6     .12       0
Bank Sta=5008.4,5020.6
XS Rating Curve= 0 ,0
Exp/Cntr=0.3,0.1

Type RM Length L Ch R = 1 ,4051    ,892,892,892
BEGIN DESCRIPTION:
COOPER CREEK 6.0
END DESCRIPTION:
XS GIS Cut Line= 3
        2459575.       13601675.        2459675.       13601275.
        2459275.       13600875.
#Sta/Elev= 30
  4592.7   237.2    4652  232.36  4657.1  232.59  4693.2  228.18  4698.4  228.49
  4734.4  224.42  4747.3  223.69  4757.6  223.58  4775.7  225.63  4780.8   225.1
  4809.2  227.17  4863.3  226.28  4904.5  223.84  4943.8  223.51  4974.1  221.28
  4980.9   212.6  4981.4   212.1  4993.1   212.6  4994.7  218.85  5002.4  220.67
  5033.3  221.08  5061.6  223.46  5089.9   227.8    5135  228.52  5217.1  228.73
  5245.4  229.87  5273.7  229.31  5358.6  231.46  5533.9  241.33  5570.7  243.83
#Mann= 6 ,-1 , 0
  4592.7     .05       0  4943.8     .12       0  4980.9     .05       0
  4993.1     .12       0    5135     .05       0  5533.9     .12       0
Bank Sta=4980.9,4993.1
XS Rating Curve= 0 ,0
Exp/Cntr=0.3,0.1

Type RM Length L Ch R = 1 ,3159    ,449,449,449
BEGIN DESCRIPTION:
COOPER CREEK 5.0
END DESCRIPTION:
XS GIS Cut Line= 3
      2460792.04     13601996.22        2460225.       13601525.
      2459324.99     13600324.98
#Sta/Elev= 30
  4262.7  247.66  4382.2  244.23  4518.4  242.31  4602.2   240.1  4772.8  230.54
    4836   229.2  4871.7  228.81  4908.2  225.17  4914.7  225.67    4922  223.51
  4978.5  218.25  4985.6  210.64  4986.1  210.14  5000.1  210.64  5003.1  210.82
  5007.3  214.55  5013.5  212.54  5021.9  219.96  5028.1  218.89  5042.7  221.69
  5086.4  221.18    5100  222.89  5162.8  224.39  5278.1  226.98    5750  226.76
  5813.5  228.04  5928.1  233.54  6234.6  257.77  6342.7  266.68    6500  281.81
#Mann= 7 ,-1 , 0
  4262.7     .07       0  4518.4     .12       0    4836     .12       0
  4985.6     .05       0  5000.1     .12       0  5162.8     .05       0
  6234.6     .07       0
Bank Sta=4985.6,5000.1
XS Rating Curve= 0 ,0
Exp/Cntr=0.3,0.1

Type RM Length L Ch R = 1 ,2710    ,424,424,424
BEGIN DESCRIPTION:
COOPER CREEK 4.0
END DESCRIPTION:
XS GIS Cut Line= 3
      2460724.98     13601424.98        2460475.       13601175.
      2459274.98     13600174.99
#Sta/Elev= 30
  4642.1  239.51  4854.2  227.62  4933.1  225.91  4981.5  224.76  4992.1  220.53
  4998.9  220.53  5002.8   214.9  5030.6   209.2  5031.1   208.7  5045.2   209.2
  5045.7  211.54  5052.3  209.69  5073.7  209.66  5080.9   214.3  5087.4  213.22
  5095.2  219.37  5101.7   217.6  5109.5  220.42  5151.8  218.64  5186.8  220.07
  5243.6  224.16  5350.3  223.54  5691.4   226.8  5898.1  240.03    6011     248
  6131.9  259.39    6186  264.36  6327.5   276.4  6369.4  279.73  6557.7  292.99
#Mann= 10 ,-1 , 0
  4642.1     .12       0  4933.1     .12       0  5030.6     .05       0
  5045.2     .12       0  5186.8     .05       0  5898.1    .035       0
  6131.9     .05       0    6186     .07       0  6327.5    .035       0
  6369.4     .07       0
Bank Sta=5030.6,5045.2
XS Rating Curve= 0 ,0
Exp/Cntr=0.3,0.1

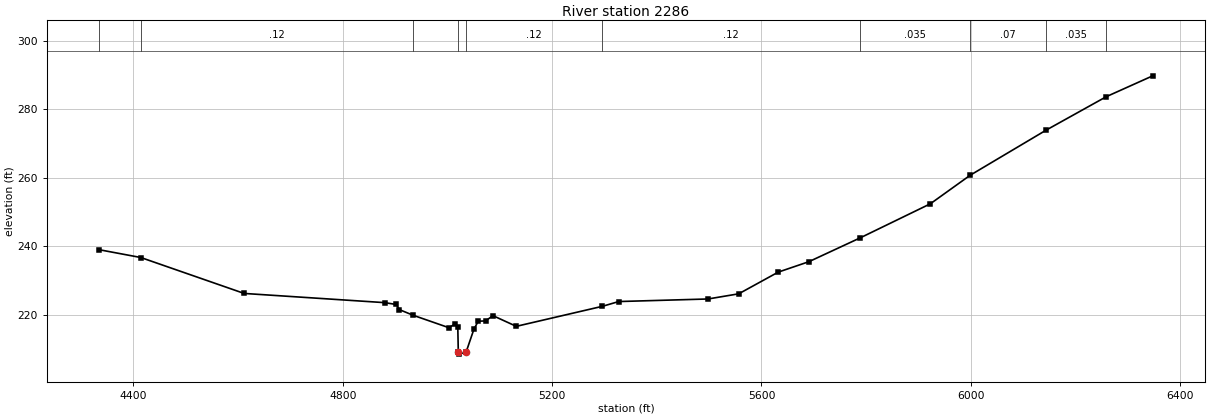
Type RM Length L Ch R = 1 ,2286    ,452,452,452
BEGIN DESCRIPTION:
COOPER CREEK 3.0
END DESCRIPTION:
XS GIS Cut Line= 3
      2460875.01     13601375.02        2460575.       13600775.
      2459374.98     13600174.99
#Sta/Elev= 30
    4335  238.95  4414.2  236.68  4611.7  226.17  4880.1  223.48  4902.4  222.94
    4908  221.45  4934.8  219.77    5003  216.14  5014.2  217.24  5019.8  216.48
  5020.8  208.92  5021.3  208.42  5035.5  208.92  5050.6  215.71  5058.9  218.05
  5072.9  218.13  5086.9  219.68  5131.6  216.55  5296.2  222.41  5327.3   223.8
  5497.8  224.55  5556.5  226.06  5631.9   232.4  5690.6  235.46  5788.5  242.42
  5922.6  252.39  5998.8  260.75  6144.1  273.96    6259  283.74  6347.5  289.82
#Mann= 10 ,-1 , 0
    4335     .07       0  4414.2     .12       0  4934.8     .12       0
  5020.8     .05       0  5035.5     .12       0  5296.2     .12       0
  5788.5    .035       0  5998.8     .07       0  6144.1    .035       0
    6259     .07       0
Bank Sta=5020.8,5035.5
XS Rating Curve= 0 ,0
Exp/Cntr=0.3,0.1