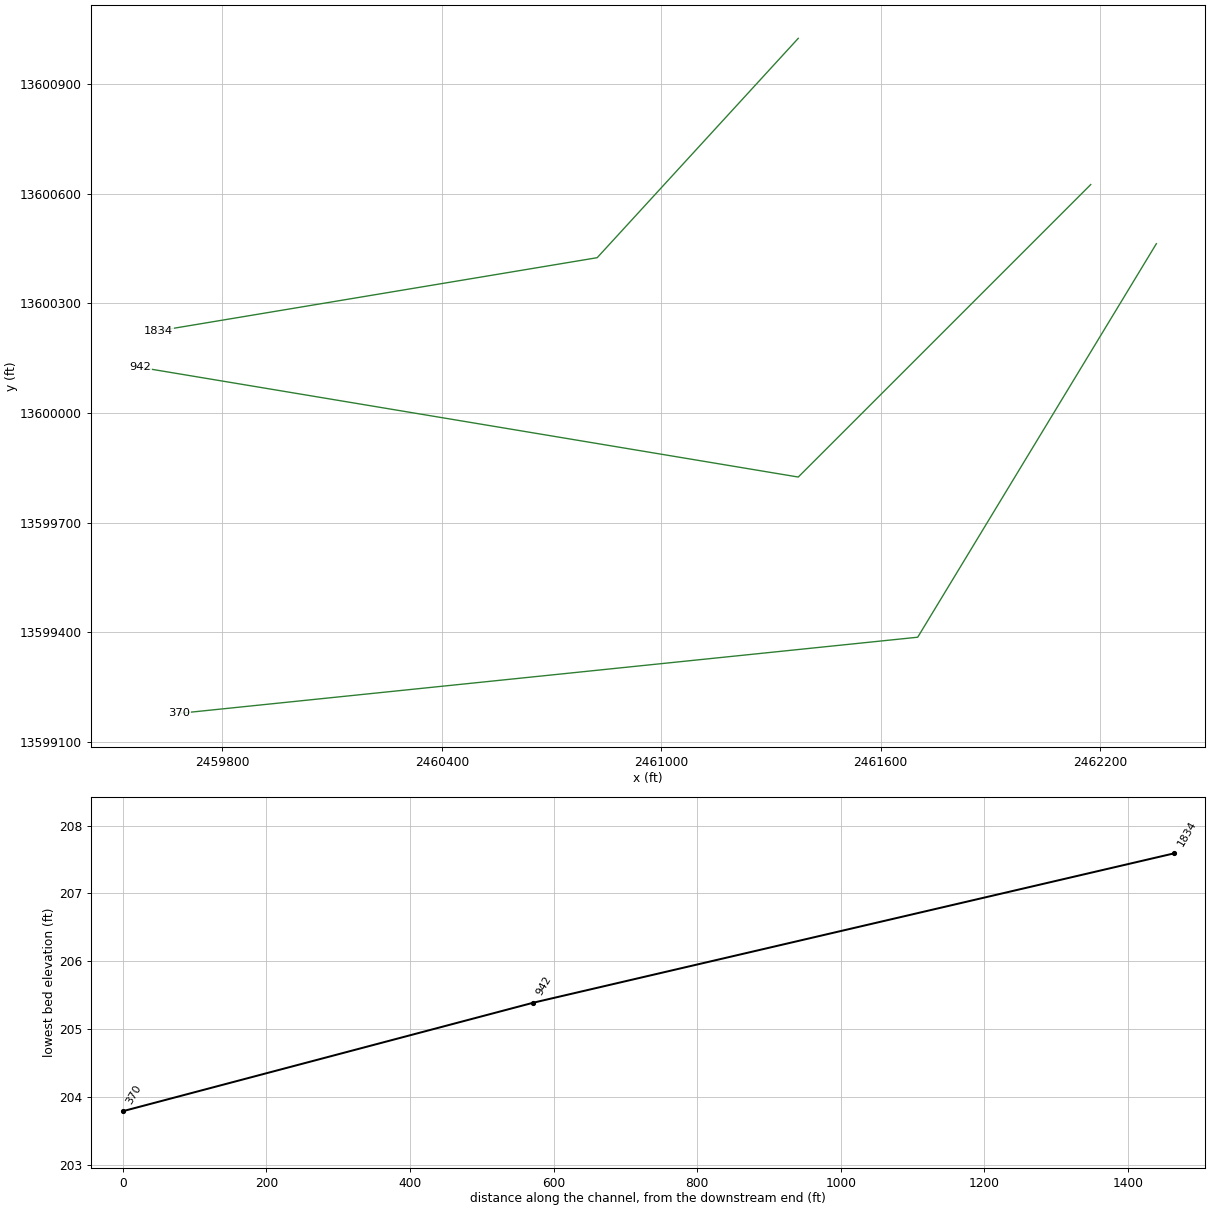
HEC-RAS study COOPER CREEK.prj: COOPER CREEK Base Level Engineering

--- COOPER CREEK.g01 (geometry) --- (continued)

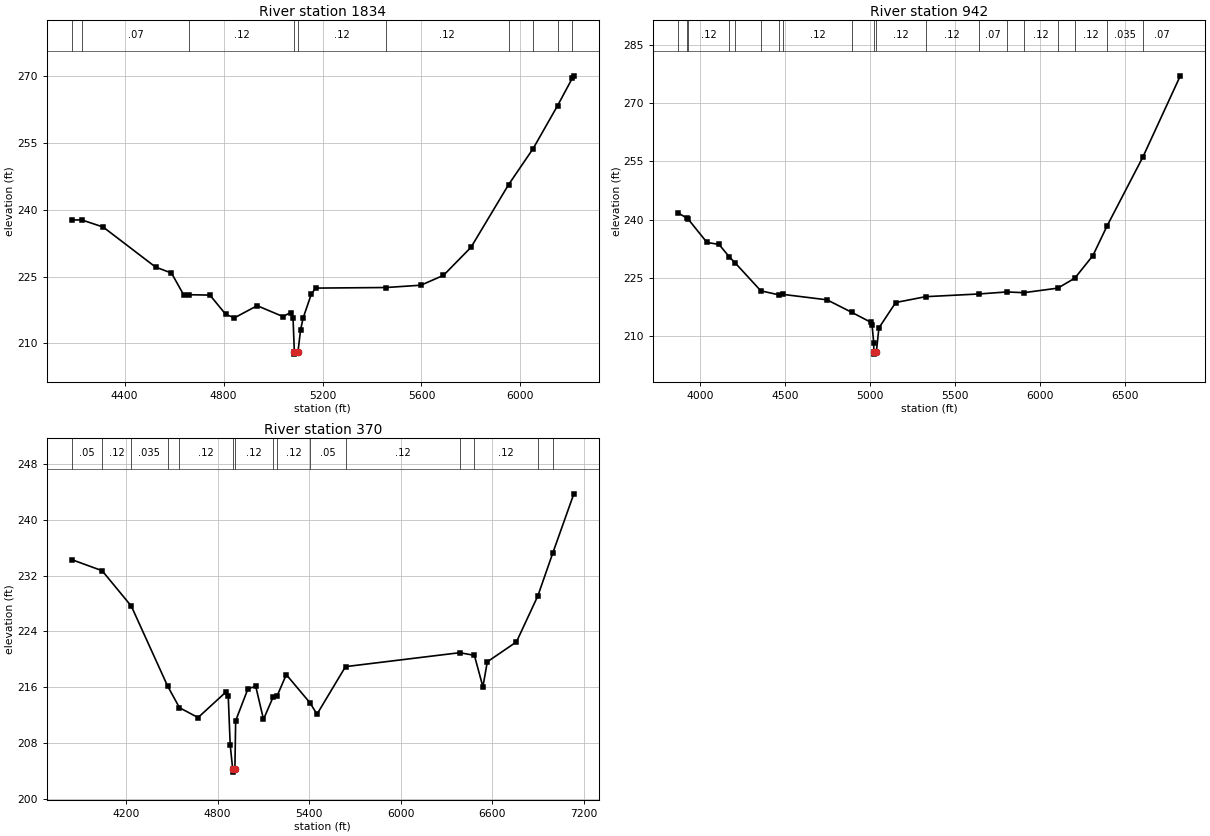
Type RM Length L Ch R = 1 ,1834    ,892,892,892
BEGIN DESCRIPTION:
COOPER CREEK 2.0
END DESCRIPTION:
XS GIS Cut Line= 3
      2461375.02     13601025.02        2460825.       13600425.
      2459625.02       13600225.
#Sta/Elev= 30
  4185.7   237.7  4226.6  237.71  4313.1  236.11  4525.2  227.12  4589.3  225.79
  4638.6  220.89  4660.4  220.92  4744.7  220.84  4808.8  216.51    4844  215.74
  4935.9  218.46  5040.2  216.02  5070.6  216.91  5080.8  215.77  5086.1  208.09
  5086.6  207.59  5100.8  208.09  5111.2  212.98  5121.3  215.64  5154.3  220.99
    5172  222.41  5457.4  222.54  5597.8  223.06  5689.1  225.27  5800.6  231.58
  5952.2  245.62  6051.5  253.71  6150.7  263.38  6210.1  269.53  6216.2  270.05
#Mann= 10 ,-1 , 0
  4185.7     .12       0  4226.6     .07       0  4660.4     .12       0
  5086.1     .05       0  5100.8     .12       0  5457.4     .12       0
  5952.2     .07       0  6051.5    .035       0  6150.7     .07       0
  6210.1    .035       0
Bank Sta=5086.1,5100.8
XS Rating Curve= 0 ,0
Exp/Cntr=0.3,0.1

Type RM Length L Ch R = 1 ,942     ,572,572,572
BEGIN DESCRIPTION:
COOPER CREEK 1.0
END DESCRIPTION:
XS GIS Cut Line= 3
      2462175.03     13600625.03        2461375.       13599825.
      2459575.04     13600124.99
#Sta/Elev= 30
  3868.6  241.74  3919.8  240.39  3925.2  240.27  4038.3  234.13  4109.1  233.62
  4170.9  230.37  4204.6  228.85  4355.5  221.68  4460.9  220.65  4487.8  220.75
  4745.5  219.36  4891.4  216.13  5002.5   213.6  5010.2  212.88  5020.3  208.18
  5020.5  205.89    5021  205.39  5035.3  205.89  5050.7  212.14  5149.5  218.67
  5325.1  220.17  5639.9  220.87  5803.1  221.39  5903.3   221.2  6103.7  222.37
  6203.9  224.94  6310.3  230.75  6393.4  238.35  6604.7  256.13  6824.8     277
#Mann= 19 ,-1 , 0
  3868.6     .05       0  3919.8    .035       0  3925.2     .12       0
  4170.9    .035       0  4204.6     .07       0  4355.5     .12       0
  4460.9     .07       0  4487.8     .12       0  4891.4     .12       0
  5020.5     .05       0  5035.3     .12       0  5325.1     .12       0
  5639.9     .07       0  5803.1    .035       0  5903.3     .12       0
  6103.7     .05       0  6203.9     .12       0  6393.4    .035       0
  6604.7     .07       0
Bank Sta=5020.5,5035.3
XS Rating Curve= 0 ,0
Exp/Cntr=0.3,0.1

Type RM Length L Ch R = 1 ,370     ,0,0,0
BEGIN DESCRIPTION:
X18509
END DESCRIPTION:
XS GIS Cut Line= 3
      2462354.55     13600463.25      2461701.78     13599386.87
      2459680.94     13599178.54
#Sta/Elev= 30
  3844.2  234.29  4043.6   232.7    4235  227.62  4472.6  216.16  4550.5  213.04
  4672.5  211.62  4854.8  215.28  4870.3  214.65    4883  207.71    4899  204.29
  4899.5  203.79  4913.8  204.29  4918.8  211.16    5000  215.79  5050.6  216.08
  5101.2  211.37  5163.9  214.55  5189.2  214.67  5250.6  217.78  5406.4  213.72
  5451.7   212.1  5638.5  218.93  6386.7  220.93    6483  220.55  6538.8  216.03
  6567.6  219.62  6758.6  222.48  6898.5  229.07  6997.1  235.26  7134.6  243.73
#Mann= 15 ,-1 , 0
  3844.2     .05       0  4043.6     .12       0    4235    .035       0
  4472.6     .12       0  4550.5     .12       0    4899     .05       0
  4913.8     .12       0  5163.9     .05       0  5189.2     .12       0
  5406.4     .05       0  5638.5     .12       0  6386.7     .05       0
    6483     .12       0  6898.5     .12       0  6997.1    .035       0
Bank Sta=4899,4913.8
XS Rating Curve= 0 ,0
Exp/Cntr=0.3,0.1

Chan Stop Cuts=-1
Use User Specified Reach Order=0
Composite Channel Slope=5