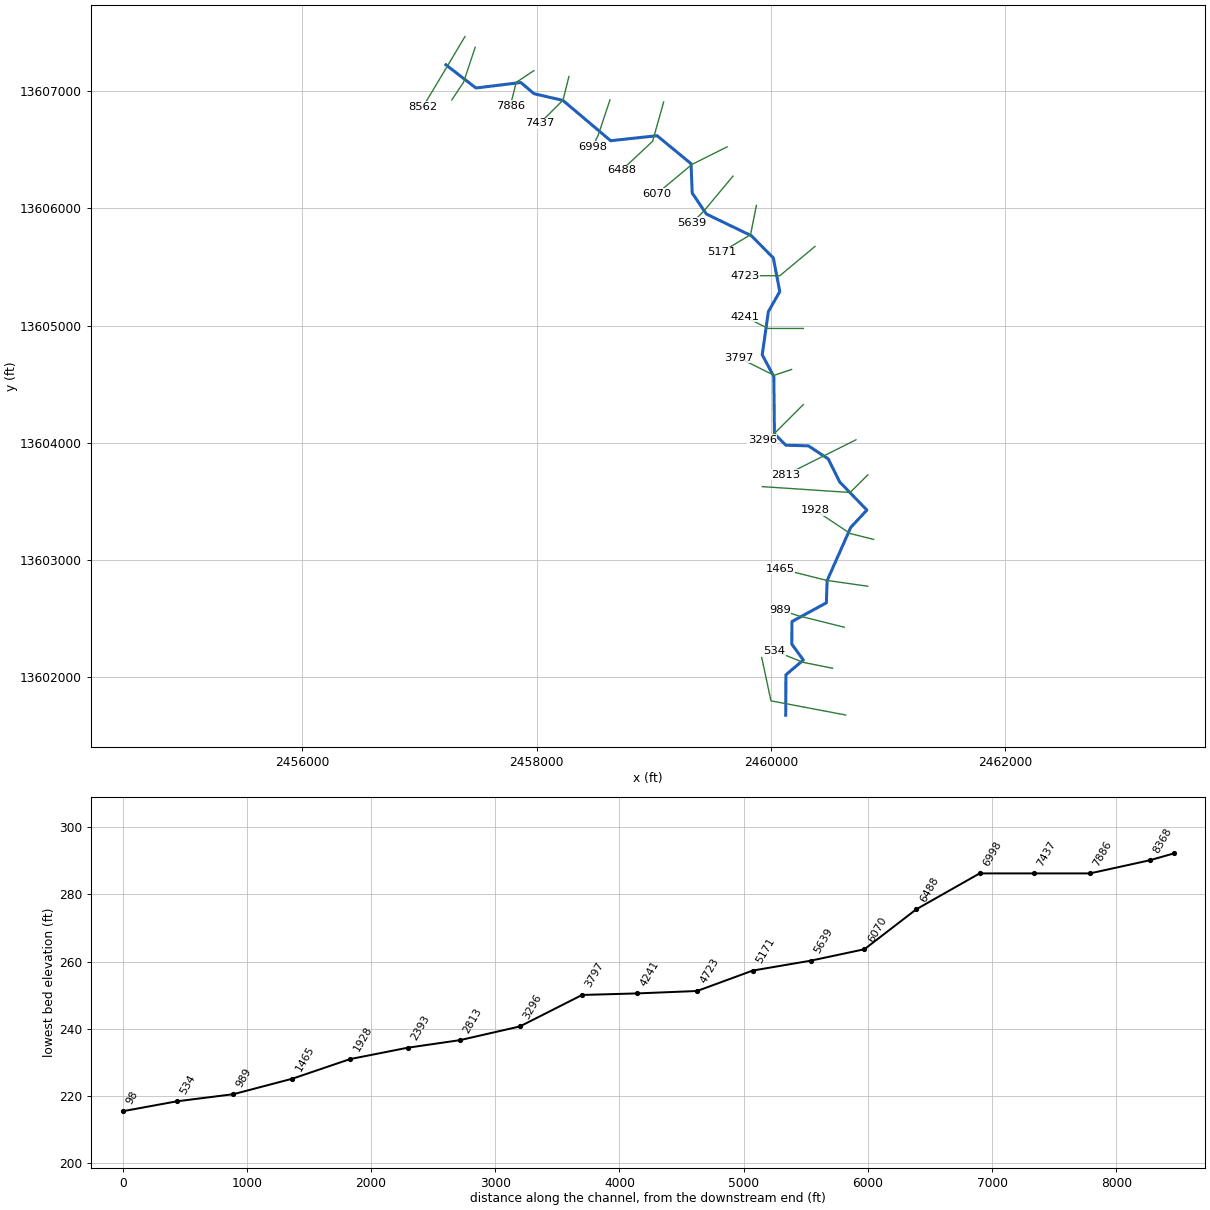
--- LITTLE COOPER CREEK.prj (project) ---

Proj Title=LITTLE COOPER CREEK Base Level Engineering
Current Plan=p01
Default Exp/Contr=0.3,0.1
English Units
Geom File=g01
Flow File=f01
Plan File=p01
BEGIN DESCRIPTION:
LITTLE COOPER CREEK
END DESCRIPTION:

--- LITTLE COOPER CREEK.p01 (plan) ---

Plan Title=Multiple Run
Short Identifier=Multiple
Geom File=g01
Flow File=f01
Subcritical Flow
K Sum by GR= 0
Std Step Tol= 0.01
Critical Tol= 0.01
Num of Std Step Trials= 20
Max Error Tol= 0.3
Flow Tol Ratio= 0.001
Split Flow NTrial= 30
Split Flow Tol= 0.02
Split Flow Ratio= 0.02
Log Output Level= 0
Friction Slope Method= 1
Unsteady Friction Slope Method= 2
Unsteady Bridges Friction Slope Method= 1
Parabolic Critical Depth
Global Vel Dist=  1 , 1 , 1
Global Log Level= 0
CheckData=True
Encroach Param= -1, 0, 0, 0
BEGIN DESCRIPTION:
Multiple Run
END DESCRIPTION:

--- LITTLE COOPER CREEK.f01 (steady flow) ---

Flow Title=Multiple
Number of Profiles=7
Profile Names=10-year,25-year,50-year,1pct_min,100-year,1pct_plu,500-year
River Rch & RM= LITTLE COOPER CR,Reach-1,8562
     779    1280    1742    1149    2293    4576    3935
River Rch & RM= LITTLE COOPER CR,Reach-1,1928
     835    1376    1877    1239    2473    4934    4254
Boundary for River Rch & Prof#=LITTLE COOPER CR,Reach-1,1
Up Type=0
Dn Type=3
Dn Slope=0.005
Boundary for River Rch & Prof#=LITTLE COOPER CR,Reach-1,2
Up Type=0
Dn Type=3
Dn Slope=0.005
Boundary for River Rch & Prof#=LITTLE COOPER CR,Reach-1,3
Up Type=0
Dn Type=3
Dn Slope=0.005
Boundary for River Rch & Prof#=LITTLE COOPER CR,Reach-1,4
Up Type=0
Dn Type=3
Dn Slope=0.005
Boundary for River Rch & Prof#=LITTLE COOPER CR,Reach-1,5
Up Type=0
Dn Type=3
Dn Slope=0.005
Boundary for River Rch & Prof#=LITTLE COOPER CR,Reach-1,6
Up Type=0
Dn Type=3
Dn Slope=0.005
Boundary for River Rch & Prof#=LITTLE COOPER CR,Reach-1,7
Up Type=0
Dn Type=3
Dn Slope=0.005

--- LITTLE COOPER CREEK.g01 (geometry) ---

Geom Title=Existing Conditions

River Reach=LITTLE COOPER CR,Reach-1
Reach XY= 30
      2457225.00     13607225.00      2457480.93     13607027.23
      2457864.56     13607073.95      2457976.50     13606978.62
      2458223.50     13606921.39      2458630.93     13606577.24
      2459027.29     13606619.90      2459317.19     13606381.19
      2459327.06     13606130.86      2459447.99     13605951.49
      2459831.06     13605766.86      2460019.17     13605577.30
      2460074.49     13605290.21      2459977.24     13605119.07
      2459924.59     13604750.00      2460023.80     13604564.50
      2460028.53     13604076.45      2460126.45     13603978.53
      2460319.14     13603972.93      2460488.24     13603861.38
      2460585.52     13603665.21      2460817.93     13603425.00
      2460680.52     13603277.43      2460478.75     13602823.45
      2460471.94     13602633.28      2460178.53     13602473.55
      2460177.07     13602280.86      2460275.51     13602145.06
      2460126.98     13602019.33      2460125.00     13601675.00

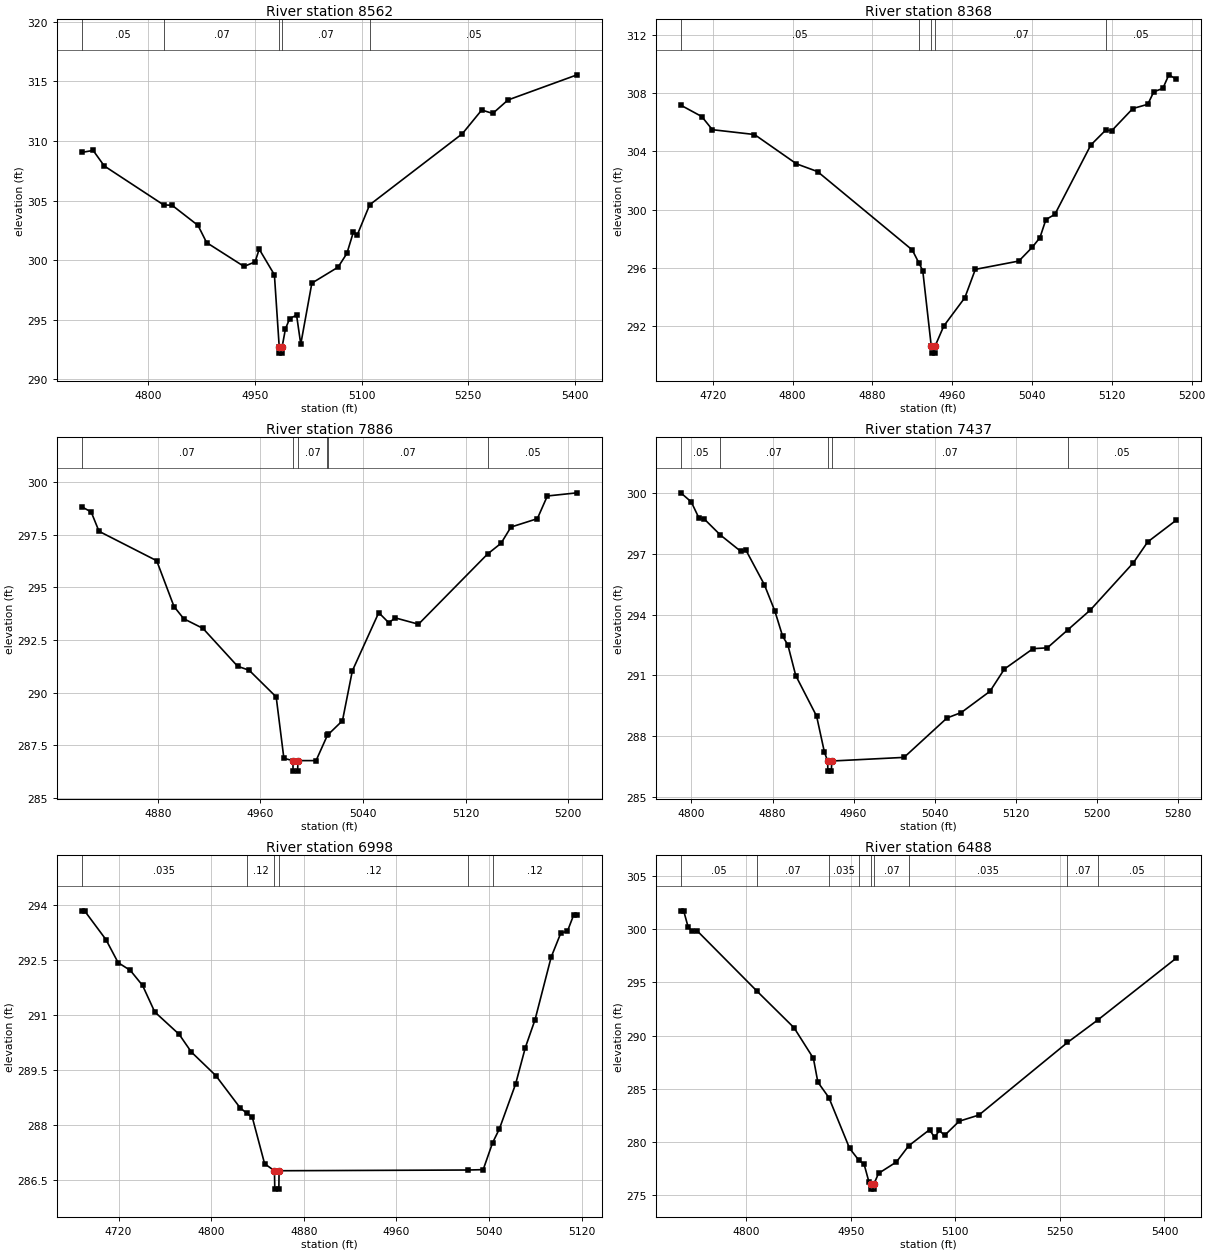
Type RM Length L Ch R = 1,8562,194,194,194
BEGIN DESCRIPTION:
A19650
END DESCRIPTION:
XS GIS Cut Line= 3
      2457387.27     13607465.84      2457210.10     13607168.05
      2457029.57     13606867.17
#Sta/Elev= 30
  4705.9  309.04  4722.2  309.21  4737.8  307.91  4821.4  304.64  4833.3  304.61
  4869.8  302.92  4881.9  301.48  4934.5  299.48  4950.1  299.86  4955.9  300.93
  4977.3  298.78  4984.1  292.71  4984.4  292.21  4987.9  292.21  4988.1  292.71
  4992.9  294.26  4998.8  295.10  5008.5  295.40  5014.4  292.96  5030.0  298.08
  5066.9  299.42  5079.3  300.57  5088.3  302.33  5094.1  302.15  5111.4  304.65
  5241.8  310.61  5269.1  312.60  5284.6  312.31  5306.0  313.44  5403.3  315.55
#Mann=5,-1,0
  4705.9    0.05       0  4821.4    0.07       0  4984.1    0.05       0
  4988.1    0.07       0  5111.4    0.05       0
Bank Sta=4984.1,4988.1
Exp/Cntr=0.3,0.1

Type RM Length L Ch R = 1,8368,482,482,482
BEGIN DESCRIPTION:
LITTLE COOPER CREEK 18.0
END DESCRIPTION:
XS GIS Cut Line= 3
      2457474.99     13607374.97      2457375.00     13607075.00
      2457274.98     13606924.98
#Sta/Elev= 30
  4688.1  307.16  4709.1  306.38  4719.7  305.48  4761.9  305.15  4804.0  303.14
  4825.1  302.61  4920.0  297.24  4926.4  296.38  4930.5  295.83  4939.0  290.67
  4939.3  290.17  4942.8  290.17  4943.0  290.67  4951.6  292.03  4972.7  293.97
  4983.2  295.91  5026.8  296.48  5040.3  297.43  5047.9  298.08  5053.9  299.32
  5062.9  299.68  5098.9  304.43  5113.8  305.45  5120.0  305.42  5141.0  306.93
  5156.0  307.22  5162.0  308.08  5171.1  308.31  5177.1  309.24  5184.6  308.94
#Mann=5,-1,0
  4688.1    0.05       0  4926.4    0.07       0  4939.0    0.05       0
  4943.0    0.07       0  5113.8    0.05       0
Bank Sta=4939,4943
Exp/Cntr=0.3,0.1

Type RM Length L Ch R = 1,7886,449,449,449
BEGIN DESCRIPTION:
LITTLE COOPER CREEK 17.0
END DESCRIPTION:
XS GIS Cut Line= 3
      2457975.03     13607175.02      2457825.00     13607075.00
      2457774.99     13606874.96
#Sta/Elev= 30
  4820.5  298.84  4828.0  298.59  4834.1  297.67  4879.1  296.27  4892.6  294.09
  4900.2  293.51  4915.2  293.05  4942.2  291.25  4951.2  291.06  4972.3  289.79
  4978.3  286.87  4985.3  286.76  4985.5  286.26  4989.0  286.26  4989.3  286.76
  5003.4  286.76  5012.2  287.96  5013.0  288.01  5024.0  288.66  5031.7  291.03
  5052.3  293.80  5060.1  293.32  5065.2  293.55  5083.3  293.25  5137.2  296.59
  5147.7  297.10  5155.4  297.87  5176.0  298.27  5183.8  299.35  5207.0  299.50
#Mann=6,-1,0
  4820.5    0.07       0  4985.3    0.05       0  4989.3    0.07       0
  5012.2    0.05       0  5013.0    0.07       0  5137.2    0.05       0
Bank Sta=4985.3,4989.3
Exp/Cntr=0.3,0.1

Type RM Length L Ch R = 1,7437,439,439,439
BEGIN DESCRIPTION:
LITTLE COOPER CREEK 16.0
END DESCRIPTION:
XS GIS Cut Line= 3
      2458275.00     13607124.98      2458225.00     13606925.00
      2458024.99     13606724.99
#Sta/Elev= 30
  4789.5  300.03  4799.8  299.58  4807.5  298.77  4812.7  298.73  4828.6  297.94
  4848.8  297.13  4853.9  297.18  4871.9  295.49  4882.3  294.18  4890.0  292.93
  4895.1  292.51  4902.9  290.99  4923.5  288.98  4931.2  287.20  4934.4  286.76
  4934.6  286.26  4938.1  286.26  4938.4  286.76  5009.8  286.94  5052.2  288.89
  5066.3  289.16  5094.6  290.21  5108.8  291.31  5137.1  292.32  5151.2  292.36
  5171.6  293.26  5193.6  294.23  5236.1  296.57  5250.2  297.60  5278.5  298.68
#Mann=5,-1,0
  4789.5    0.05       0  4828.6    0.07       0  4934.4    0.05       0
  4938.4    0.07       0  5171.6    0.05       0
Bank Sta=4934.4,4938.4
Exp/Cntr=0.3,0.1

Type RM Length L Ch R = 1,6998,510,510,510
BEGIN DESCRIPTION:
LITTLE COOPER CREEK 15.0
END DESCRIPTION:
XS GIS Cut Line= 3
      2458624.99     13606924.96      2458525.00     13606625.00
      2458475.00     13606524.99
#Sta/Elev= 30
  4688.1  293.83  4690.7  293.83  4709.1  293.05  4719.7  292.42  4730.2  292.21
  4740.8  291.80  4751.3  291.08  4772.4  290.47  4782.9  289.99  4804.0  289.35
  4825.1  288.47  4831.0  288.32  4835.6  288.21  4846.2  286.95  4854.7  286.76
  4855.0  286.26  4858.5  286.26  4858.7  286.76  5022.3  286.78  5035.0  286.79
  5043.1  287.52  5049.0  287.90  5063.0  289.12  5071.4  290.11  5079.8  290.87
  5093.7  292.57  5102.1  293.23  5107.7  293.27  5113.3  293.73  5116.1  293.73
#Mann=6,-1,0
  4688.1   0.035       0  4831.0    0.12       0  4854.7    0.05       0
  4858.7    0.12       0  5022.3    0.12       0  5043.1    0.12       0
Bank Sta=4854.7,4858.7
Exp/Cntr=0.3,0.1

Type RM Length L Ch R = 1,6488,418,418,418
BEGIN DESCRIPTION:
LITTLE COOPER CREEK 14.0
END DESCRIPTION:
XS GIS Cut Line= 3
      2459083.46     13606907.97      2458989.22     13606572.50
      2458725.00     13606325.00
#Sta/Elev= 30
  4706.5  301.73  4710.6  301.73  4717.0  300.20  4722.2  299.82  4730.4  299.82
  4815.6  294.19  4868.9  290.74  4896.6  287.87  4903.0  285.63  4918.8  284.18
  4948.5  279.41  4961.7  278.30  4969.3  277.92  4976.3  276.24  4979.5  276.08
  4979.7  275.58  4983.2  275.58  4983.5  276.08  4990.0  277.06  5015.6  278.13
  5033.2  279.65  5063.1  281.16  5070.4  280.44  5077.3  281.10  5084.6  280.62
  5105.6  281.96  5133.9  282.54  5260.9  289.36  5304.7  291.49  5417.0  297.29
#Mann=9,-1,0
  4706.5    0.05       0  4815.6    0.07       0  4918.8   0.035       0
  4961.7    0.07       0  4979.5    0.05       0  4983.5    0.07       0
  5033.2   0.035       0  5260.9    0.07       0  5304.7    0.05       0
Bank Sta=4979.5,4983.5
Exp/Cntr=0.3,0.1

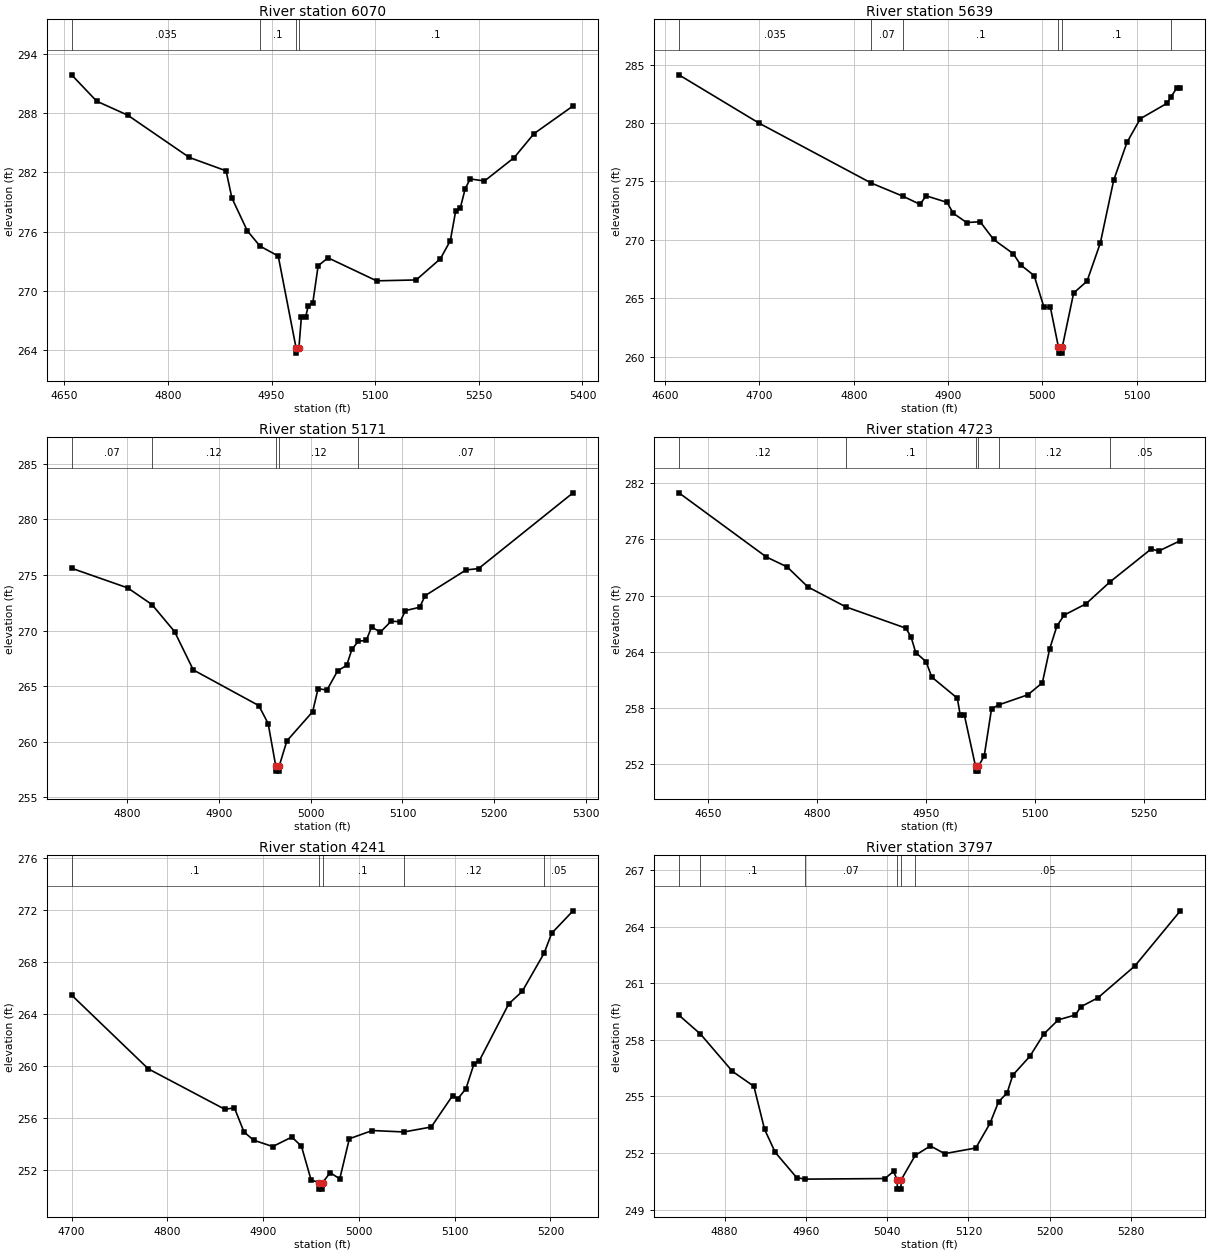
Type RM Length L Ch R = 1,6070,431,431,431
BEGIN DESCRIPTION:
LITTLE COOPER CREEK 13.0
END DESCRIPTION:
XS GIS Cut Line= 3
      2459625.00     13606525.00      2459325.00     13606375.00
      2459025.01     13606125.01
#Sta/Elev= 30
  4660.5  291.87  4696.8  289.20  4741.6  287.79  4831.0  283.50  4884.1  282.15
  4892.5  279.40  4914.8  276.08  4933.2  274.53  4959.6  273.52  4985.5  264.19
  4985.8  263.69  4989.5  264.19  4993.1  267.33  4999.2  267.33  5003.1  268.48
  5009.6  268.76  5017.4  272.54  5031.7  273.34  5102.0  271.01  5159.3  271.10
  5194.4  273.25  5208.7  275.07  5216.5  278.08  5223.1  278.37  5230.2  280.32
  5237.4  281.33  5258.2  281.12  5301.2  283.49  5329.8  285.91  5386.4  288.72
#Mann=4,-1,0
  4660.5   0.035       0  4933.2     0.1       0  4985.5    0.05       0
  4989.5     0.1       0
Bank Sta=4985.5,4989.5
Exp/Cntr=0.3,0.1

Type RM Length L Ch R = 1,5639,468,468,468
BEGIN DESCRIPTION:
LITTLE COOPER CREEK 12.0
END DESCRIPTION:
XS GIS Cut Line= 3
      2459675.03     13606275.03      2459425.00     13605975.00
      2459324.98     13605874.98
#Sta/Elev= 30
  4614.5  284.13  4699.8  279.98  4818.4  274.87  4852.6  273.72  4870.3  273.04
  4876.8  273.77  4899.0  273.21  4905.5  272.28  4919.8  271.48  4934.1  271.55
  4948.4  270.03  4969.3  268.81  4977.1  267.85  4991.4  266.94  5001.8  264.23
  5008.6  264.23  5017.2  260.80  5017.4  260.30  5020.9  260.30  5021.2  260.80
  5033.3  265.45  5047.5  266.46  5061.6  269.73  5075.8  275.11  5089.9  278.35
  5104.0  280.37  5132.3  281.69  5136.8  282.26  5142.9  283.03  5146.5  283.03
#Mann=6,-1,0
  4614.5   0.035       0  4818.4    0.07       0  4852.6     0.1       0
  5017.2    0.05       0  5021.2     0.1       0  5136.8    0.07       0
Bank Sta=5017.2,5021.2
Exp/Cntr=0.3,0.1

Type RM Length L Ch R = 1,5171,448,448,448
BEGIN DESCRIPTION:
LITTLE COOPER CREEK 11.0
END DESCRIPTION:
XS GIS Cut Line= 3
      2459875.00     13606025.02      2459825.00     13605775.00
      2459575.02     13605625.01
#Sta/Elev= 30
  4739.4  275.61  4800.6  273.84  4827.0  272.34  4851.6  269.91  4872.0  266.46
  4943.4  263.25  4953.6  261.63  4961.8  257.85  4962.0  257.35  4965.5  257.35
  4965.8  257.85  4974.0  260.07  5002.1  262.70  5008.0  264.77  5017.7  264.65
  5029.4  266.39  5039.1  266.86  5044.9  268.31  5051.9  269.05  5060.5  269.11
  5066.3  270.31  5076.0  269.87  5087.7  270.85  5097.4  270.79  5103.2  271.80
  5118.8  272.10  5124.6  273.14  5169.3  275.46  5182.9  275.58  5285.9  282.40
#Mann=5,-1,0
  4739.4    0.07       0  4827.0    0.12       0  4961.8    0.05       0
  4965.8    0.12       0  5051.9    0.07       0
Bank Sta=4961.8,4965.8
Exp/Cntr=0.3,0.1

Type RM Length L Ch R = 1,4723,482,482,482
BEGIN DESCRIPTION:
LITTLE COOPER CREEK 10.0
END DESCRIPTION:
XS GIS Cut Line= 3
      2460375.00     13605675.00      2460075.00     13605425.00
      2459775.02     13605425.00
#Sta/Elev= 30
  4610.0  280.95  4730.4  274.11  4759.0  273.05  4787.7  270.91  4840.1  268.78
  4922.4  266.52  4929.6  265.60  4936.1  263.92  4950.4  262.94  4958.2  261.30
  4993.4  259.05  4997.3  257.28  5003.0  257.28  5018.5  251.77  5018.8  251.27
  5022.3  251.27  5022.5  251.77  5030.5  252.92  5040.5  257.91  5050.2  258.33
  5090.5  259.41  5110.5  260.69  5120.5  264.29  5130.5  266.74  5140.5  267.91
  5170.5  269.11  5203.3  271.43  5260.5  274.97  5270.5  274.73  5300.5  275.85
#Mann=6,-1,0
  4610.0    0.12       0  4840.1     0.1       0  5018.5    0.05       0
  5022.5     0.1       0  5050.2    0.12       0  5203.3    0.05       0
Bank Sta=5018.5,5022.5
Exp/Cntr=0.3,0.1

Type RM Length L Ch R = 1,4241,444,444,444
BEGIN DESCRIPTION:
LITTLE COOPER CREEK 9.0
END DESCRIPTION:
XS GIS Cut Line= 3
      2460275.00     13604975.00      2459975.00     13604975.00
      2459775.01     13605074.99
#Sta/Elev= 30
  4700.0  265.45  4780.0  259.79  4860.0  256.68  4870.0  256.79  4880.0  254.94
  4890.0  254.31  4910.0  253.82  4930.0  254.55  4940.0  253.84  4950.0  251.27
  4958.0  251.05  4958.3  250.55  4961.8  250.55  4962.0  251.05  4970.0  251.81
  4980.0  251.34  4990.0  254.42  5014.0  255.05  5047.0  254.94  5075.5  255.32
  5097.8  257.73  5103.4  257.50  5111.8  258.27  5120.2  260.18  5125.8  260.42
  5156.5  264.78  5170.5  265.73  5193.4  268.67  5201.3  270.20  5223.6  271.92
#Mann=5,-1,0
  4700.0     0.1       0  4958.0    0.05       0  4962.0     0.1       0
  5047.0    0.12       0  5193.4    0.05       0
Bank Sta=4958,4962
Exp/Cntr=0.3,0.1

Type RM Length L Ch R = 1,3797,501,501,501
BEGIN DESCRIPTION:
LITTLE COOPER CREEK 8.0
END DESCRIPTION:
XS GIS Cut Line= 3
      2460174.97     13604624.99      2460025.00     13604575.00
      2459725.00     13604725.00
#Sta/Elev= 30
  4835.0  259.31  4856.2  258.31  4887.7  256.33  4908.8  255.54  4919.3  253.26
  4929.8  252.04  4950.9  250.70  4958.9  250.62  5037.8  250.65  5046.2  251.03
  5049.8  250.59  5050.0  250.09  5053.5  250.09  5053.8  250.59  5067.6  251.88
  5082.5  252.38  5096.5  251.97  5127.2  252.27  5141.2  253.58  5149.6  254.72
  5158.0  255.19  5163.6  256.13  5180.4  257.13  5194.3  258.32  5208.3  259.06
  5225.1  259.32  5230.7  259.76  5247.4  260.23  5283.8  261.92  5328.5  264.84
#Mann=6,-1,0
  4835.0    0.07       0  4856.2     0.1       0  4958.9    0.07       0
  5049.8    0.05       0  5053.8    0.07       0  5067.6    0.05       0
Bank Sta=5049.8,5053.8
Exp/Cntr=0.3,0.1

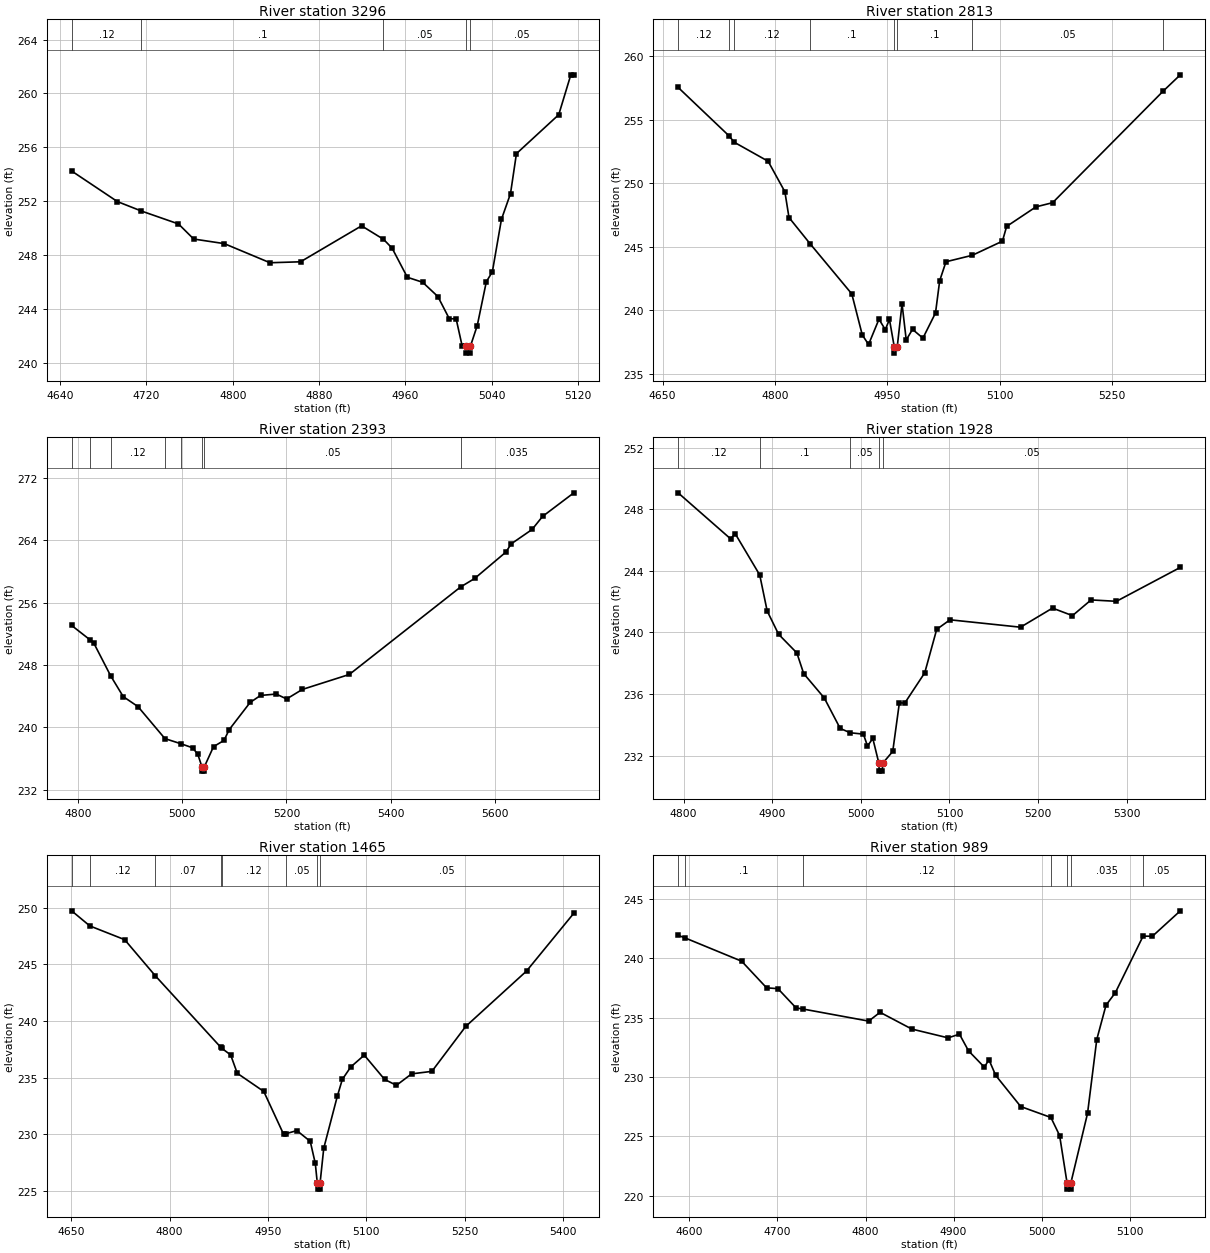
Type RM Length L Ch R = 1,3296,483,483,483
BEGIN DESCRIPTION:
LITTLE COOPER CREEK 7.0
END DESCRIPTION:
XS GIS Cut Line= 3
      2460275.00     13604325.00      2460025.00     13604075.00
      2459924.96     13604024.98
#Sta/Elev= 30
  4650.7  254.24  4693.1  251.97  4715.3  251.27  4749.7  250.31  4763.8  249.19
  4792.1  248.85  4834.5  247.43  4862.8  247.50  4919.4  250.17  4939.7  249.17
  4947.7  248.51  4961.8  246.35  4976.0  245.98  4990.1  244.92  5000.7  243.27
  5007.0  243.27  5012.6  241.25  5016.2  241.22  5016.5  240.72  5020.0  240.72
  5020.2  241.22  5026.6  242.77  5035.0  246.02  5040.6  246.76  5049.0  250.65
  5057.4  252.56  5062.9  255.53  5102.1  258.42  5113.3  261.38  5116.1  261.38
#Mann=5,-1,0
  4650.7    0.12       0  4715.3     0.1       0  4939.7    0.05       0
  5016.2    0.05       0  5020.2    0.05       0
Bank Sta=5016.2,5020.2
Exp/Cntr=0.3,0.1

Type RM Length L Ch R = 1,2813,420,420,420
BEGIN DESCRIPTION:
LITTLE COOPER CREEK 6.0
END DESCRIPTION:
XS GIS Cut Line= 3
      2460725.01     13604025.00      2460425.00     13603875.00
      2460125.03     13603725.01
#Sta/Elev= 30
  4670.7  257.55  4738.3  253.76  4745.8  253.23  4790.9  251.74  4813.3  249.34
  4818.8  247.31  4846.8  245.26  4902.7  241.30  4916.7  238.07  4925.1  237.32
  4939.0  239.31  4947.4  238.49  4953.0  239.29  4959.4  237.14  4959.6  236.64
  4963.4  237.14  4969.8  240.52  4975.4  237.68  4983.8  238.51  4997.7  237.82
  5014.5  239.80  5020.1  242.34  5028.5  243.83  5063.7  244.34  5103.9  245.45
  5109.5  246.61  5148.7  248.15  5171.0  248.48  5318.3  257.24  5341.5  258.54
#Mann=8,-1,0
  4670.7    0.12       0  4738.3     0.1       0  4745.8    0.12       0
  4846.8     0.1       0  4959.4    0.05       0  4963.4     0.1       0
  5063.7    0.05       0  5318.3   0.035       0
Bank Sta=4959.4,4963.4
Exp/Cntr=0.3,0.1

Type RM Length L Ch R = 1,2393,465,465,465
BEGIN DESCRIPTION:
LITTLE COOPER CREEK 5.0
END DESCRIPTION:
XS GIS Cut Line= 3
      2460825.02     13603725.02      2460675.00     13603575.00
      2459925.03     13603625.00
#Sta/Elev= 30
  4787.8  253.06  4823.4  251.20  4830.3  250.80  4862.7  246.60  4886.8  243.94
  4915.1  242.66  4966.8  238.56  4997.9  237.89  5020.0  237.38  5030.0  236.53
  5038.1  234.89  5038.3  234.39  5041.8  234.39  5042.1  234.89  5060.1  237.53
  5080.1  238.32  5090.2  239.71  5130.3  243.19  5150.3  244.09  5180.4  244.27
  5200.4  243.64  5230.5  244.86  5320.7  246.78  5534.4  258.00  5561.2  259.08
  5621.3  262.47  5631.4  263.52  5671.4  265.36  5691.5  267.03  5751.6  270.06
#Mann=8,-1,0
  4787.8    0.07       0  4823.4     0.1       0  4862.7    0.12       0
  4966.8     0.1       0  4997.9    0.05       0  5038.1    0.05       0
  5042.1    0.05       0  5534.4   0.035       0
Bank Sta=5038.1,5042.1
Exp/Cntr=0.3,0.1

Type RM Length L Ch R = 1,1928,463,463,463
BEGIN DESCRIPTION:
LITTLE COOPER CREEK 4.0
END DESCRIPTION:
XS GIS Cut Line= 3
      2460874.99     13603175.00      2460675.00     13603225.00
      2460375.00     13603425.00
#Sta/Elev= 30
  4793.8  249.06  4853.1  246.07  4858.2  246.41  4885.9  243.73  4894.3  241.39
  4907.2  239.88  4927.8  238.67  4935.5  237.33  4958.7  235.75  4976.7  233.77
  4988.0  233.49  5002.9  233.40  5007.5  232.63  5013.5  233.12  5020.4  231.50
  5020.7  231.00  5024.3  231.00  5024.5  231.50  5036.0  232.28  5043.5  235.44
  5049.5  235.41  5072.1  237.38  5085.6  240.20  5100.6  240.82  5180.2  240.34
  5216.3  241.58  5238.8  241.09  5259.8  242.11  5288.4  242.02  5360.5  244.22
#Mann=5,-1,0
  4793.8    0.12       0  4885.9     0.1       0  4988.0    0.05       0
  5020.4    0.05       0  5024.5    0.05       0
Bank Sta=5020.4,5024.5
Exp/Cntr=0.3,0.1

Type RM Length L Ch R = 1,1465,476,476,476
BEGIN DESCRIPTION:
LITTLE COOPER CREEK 3.0
END DESCRIPTION:
XS GIS Cut Line= 3
      2460825.02     13602775.00      2460475.00     13602825.00
      2460074.98     13602925.00
#Sta/Elev= 30
  4650.7  249.71  4678.4  248.38  4731.5  247.17  4778.2  243.99  4878.0  237.69
  4879.5  237.60  4893.2  237.01  4903.3  235.39  4943.7  233.79  4974.0  230.01
  4977.8  230.07  4994.2  230.34  5014.6  229.39  5022.3  227.44  5025.4  225.68
  5025.7  225.18  5029.3  225.18  5029.5  225.68  5035.2  228.79  5055.8  233.35
  5063.5  234.85  5076.4  235.95  5097.0  236.99  5128.0  234.85  5146.0  234.33
  5169.2  235.34  5200.1  235.56  5251.7  239.52  5344.4  244.40  5416.6  249.50
#Mann=8,-1,0
  4650.7    0.07       0  4678.4    0.12       0  4778.2    0.07       0
  4878.0     0.1       0  4879.5    0.12       0  4977.8    0.05       0
  5025.4    0.05       0  5029.5    0.05       0
Bank Sta=5025.4,5029.5
Exp/Cntr=0.3,0.1

Type RM Length L Ch R = 1,989,455,455,455
BEGIN DESCRIPTION:
LITTLE COOPER CREEK 2.0
END DESCRIPTION:
XS GIS Cut Line= 3
      2460625.04     13602424.99      2460225.00     13602525.00
      2460074.97     13602575.01
#Sta/Elev= 30
  4587.1  241.92  4595.0  241.70  4659.3  239.74  4687.6  237.50  4700.5  237.43
  4721.1  235.81  4729.4  235.71  4803.6  234.70  4816.5  235.44  4852.6  234.03
  4893.8  233.29  4906.7  233.60  4917.0  232.20  4935.0  230.82  4940.2  231.45
  4947.9  230.13  4976.3  227.51  5010.6  226.59  5020.5  225.07  5029.0  221.06
  5029.2  220.56  5032.9  220.56  5033.2  221.06  5052.2  226.93  5062.7  233.15
  5073.2  236.04  5083.8  237.09  5115.3  241.85  5125.9  241.84  5157.6  243.98
#Mann=7,-1,0
  4587.1   0.035       0  4595.0     0.1       0  4729.4    0.12       0
  5010.6   0.035       0  5029.0    0.05       0  5033.2   0.035       0
  5115.3    0.05       0
Bank Sta=5029,5033.2
Exp/Cntr=0.3,0.1

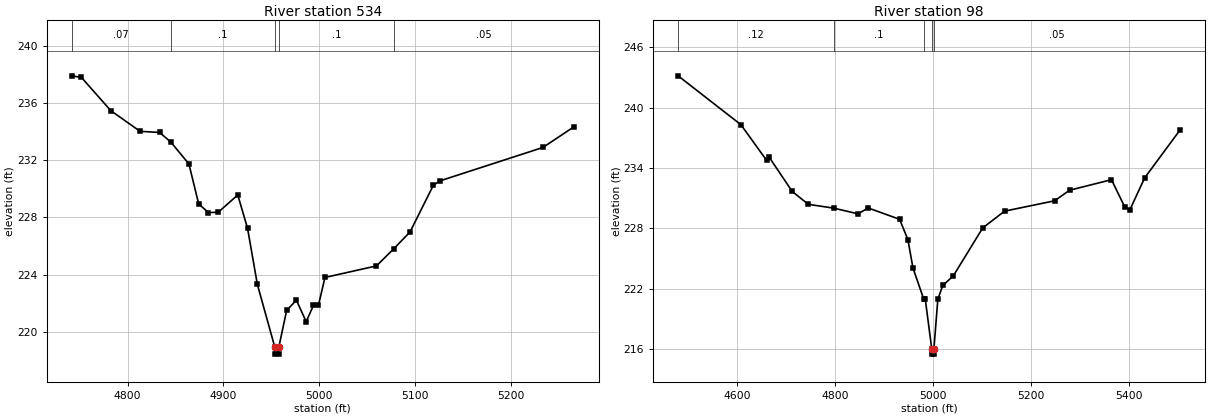
Type RM Length L Ch R = 1,534,436,436,436
BEGIN DESCRIPTION:
LITTLE COOPER CREEK 1.0
END DESCRIPTION:
XS GIS Cut Line= 3
      2460525.01     13602075.00      2460275.00     13602125.00
      2460025.01     13602224.99
#Sta/Elev= 30
  4741.7  237.90  4751.9  237.79  4782.5  235.47  4813.1  234.02  4833.5  233.94
  4845.2  233.27  4864.1  231.74  4874.3  228.94  4884.5  228.34  4894.7  228.36
  4915.1  229.57  4925.3  227.24  4935.5  223.33  4953.7  218.94  4954.0  218.44
  4957.7  218.44  4958.0  218.94  4966.1  221.50  4976.3  222.21  4986.5  220.71
  4994.1  221.85  4999.3  221.85  5006.1  223.80  5059.9  224.61  5078.1  225.82
  5094.9  226.98  5119.2  230.24  5125.9  230.55  5233.6  232.89  5265.9  234.33
#Mann=5,-1,0
  4741.7    0.07       0  4845.2     0.1       0  4953.7    0.05       0
  4958.0     0.1       0  5078.1    0.05       0
Bank Sta=4953.7,4958
Exp/Cntr=0.3,0.1

Type RM Length L Ch R = 1,98,0,0,0
BEGIN DESCRIPTION:
A19649
END DESCRIPTION:
XS GIS Cut Line= 3
      2460636.40     13601676.13      2459999.41     13601796.75
      2459920.25     13602166.15
#Sta/Elev= 30
  4479.5  243.17  4607.8  238.31  4660.3  234.76  4665.4  235.09  4712.6  231.67
  4745.5  230.39  4797.5  230.01  4847.3  229.44  4867.7  230.03  4932.1  228.90
  4949.1  226.86  4959.3  224.07  4981.0  221.01  4984.4  221.00  4997.8  215.99
  4998.1  215.49  5001.8  215.49  5002.1  215.99  5010.2  220.96  5020.3  222.32
  5041.8  223.27  5101.8  228.04  5146.5  229.71  5248.7  230.74  5279.4  231.79
  5365.0  232.84  5391.9  230.14  5402.2  229.81  5432.8  233.02  5505.6  237.82
#Mann=5,-1,0
  4479.5    0.12       0  4797.5     0.1       0  4981.0    0.05       0
  4997.8    0.05       0  5002.1    0.05       0
Bank Sta=4997.8,5002.1
Exp/Cntr=0.3,0.1

Chan Stop Cuts=-1