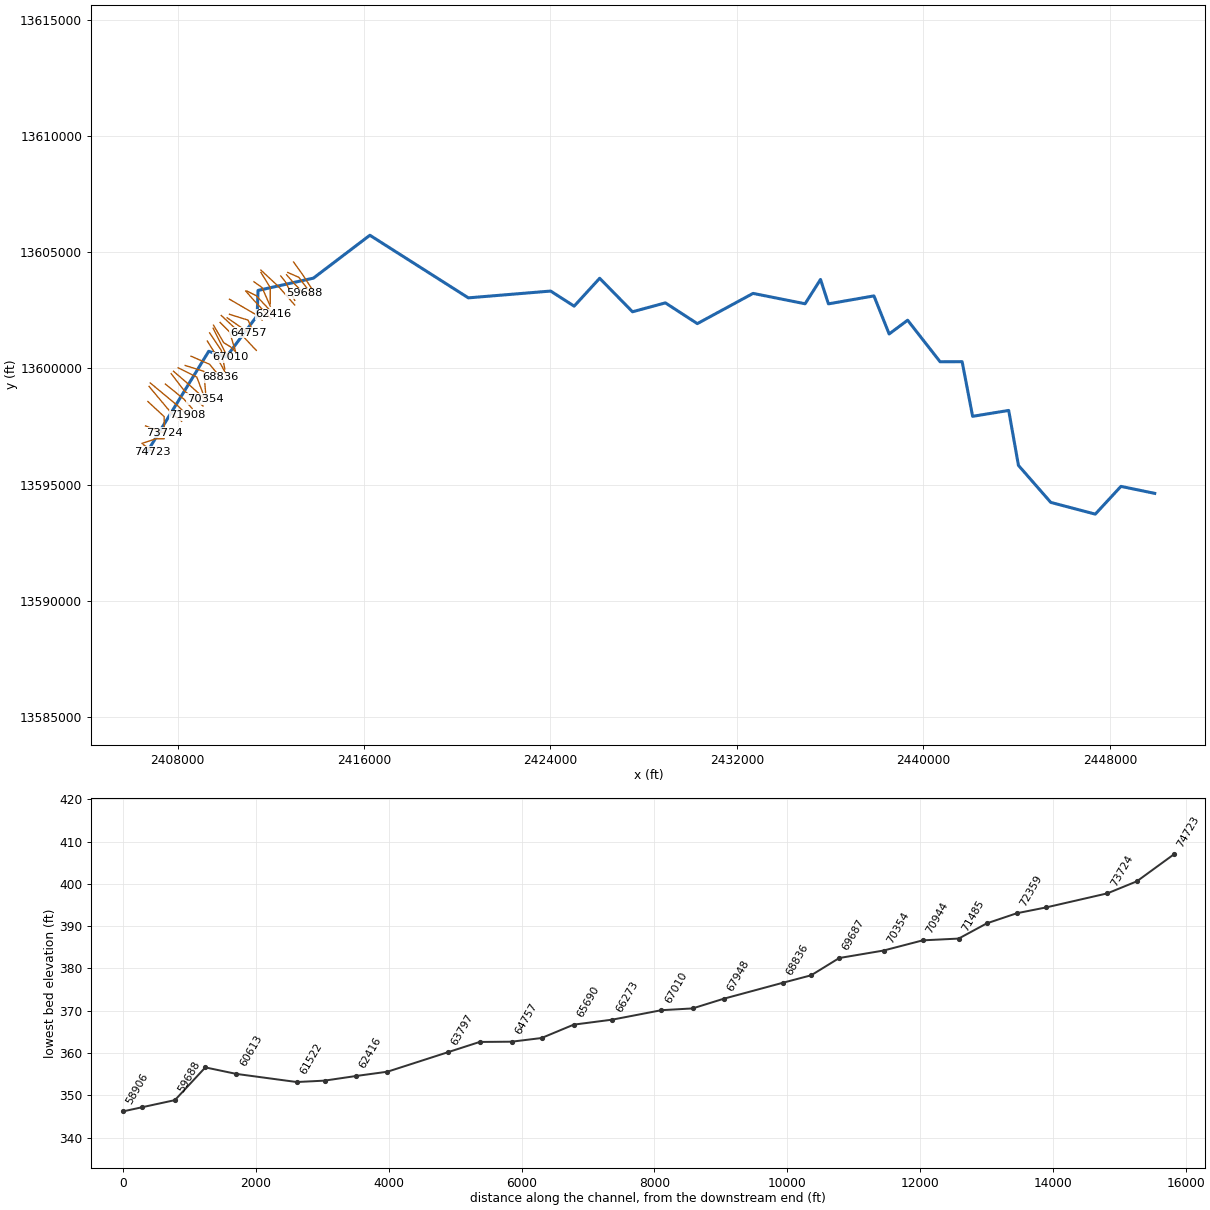
--- SHOATS CREEK.prj (project) ---

Proj Title=SHOATS CREEK Base Level Engineering
Current Plan=p01
Default Exp/Contr=0.3,0.1
English Units
Geom File=g01
Flow File=f01
Plan File=p01
Y Axis Title=Elevation
X Axis Title(PF)=Main Channel Distance
X Axis Title(XS)=Station
BEGIN DESCRIPTION:
SHOATS CREEK
END DESCRIPTION:
DSS Export Rating Curves= 0
DSS Export Rating Curve Sorted= 0
DSS Export Volume Flow Curves= 0
DXF OffsetX= 0
DXF OffsetY= 0
DXF ScaleX= 1
DXF ScaleY= 10

--- SHOATS CREEK.p01 (plan) ---

Plan Title=Multiple Run
Short Identifier=Multiple
Geom File=g01
Flow File=f01
Subcritical Flow
K Sum by GR= 0
Std Step Tol= 0.01
Critical Tol= 0.01
Num of Std Step Trials= 20
Max Error Tol= 0.3
Flow Tol Ratio= 0.001
Split Flow NTrial= 30
Split Flow Tol= 0.02
Split Flow Ratio= 0.02
Log Output Level= 0
Friction Slope Method= 1
Unsteady Friction Slope Method= 2
Unsteady Bridges Friction Slope Method= 1
Parabolic Critical Depth
Global Vel Dist=  1 , 1 , 1
Global Log Level= 0
CheckData=True
Encroach Param= -1, 0, 0, 0
BEGIN DESCRIPTION:
Multiple Run
END DESCRIPTION:

--- SHOATS CREEK.f01 (steady flow) ---

Flow Title=Multiple
Number of Profiles=7
Profile Names=10-year,25-year,50-year,1pct_min,100-year,1pct_plu,500-year
River Rch & RM= SHOATS CREEK,Reach-1,74723
    1110    1902    2663    1806    3604    7190    6545
River Rch & RM= SHOATS CREEK,Reach-1,74166
    1197    2039    2841    1916    3823    7628    6865
River Rch & RM= SHOATS CREEK,Reach-1,69265
    1567    2703    3799    2581    5149   10274    9388
River Rch & RM= SHOATS CREEK,Reach-1,67948
    1553    2626    3639    2434    4856    9689    8578
River Rch & RM= SHOATS CREEK,Reach-1,56399
    1541    2598    3594    2399    4788    9552    8427
River Rch & RM= SHOATS CREEK,Reach-1,55695
    2256    3858    5387    3625    7233   14432   12939
River Rch & RM= SHOATS CREEK,Reach-1,50621
    2610    4483    6276    4232    8445   16849   15170
River Rch & RM= SHOATS CREEK,Reach-1,48225
    2862    4924    6901    4657    9293   18542   16718
River Rch & RM= SHOATS CREEK,Reach-1,46606
    2996    5158    7230    4880    9737   19429   17522
River Rch & RM= SHOATS CREEK,Reach-1,44839
    3144    5419    7603    5135   10246   20444   18463
River Rch & RM= SHOATS CREEK,Reach-1,40427
    3336    5771    8118    5497   10968   21885   19864
River Rch & RM= SHOATS CREEK,Reach-1,38741
    3324    5725    8030    5420   10815   21578   19460
River Rch & RM= SHOATS CREEK,Reach-1,34437
    2102    3445    4666    3038    6062   12095   10149
River Rch & RM= SHOATS CREEK,Reach-1,31644
    2158    3526    4766    3096    6177   12325   10291
River Rch & RM= SHOATS CREEK,Reach-1,25493
    2384    3924    5332    3481    6946   13859   11695
River Rch & RM= SHOATS CREEK,Reach-1,19708
    2497    4125    5618    3677    7337   14640   12415
River Rch & RM= SHOATS CREEK,Reach-1,18394
    3342    5599    7700    5088   10152   20256   17502
River Rch & RM= SHOATS CREEK,Reach-1,10705
    3481    5840    8040    5317   10609   21168   18321
River Rch & RM= SHOATS CREEK,Reach-1,9003
    3471    5818    8006    5292   10559   21068   18214
River Rch & RM= SHOATS CREEK,Reach-1,7272
    3562    5965    8202    5417   10808   21564   18611
River Rch & RM= SHOATS CREEK,Reach-1,1249
    3863    6485    8934    5912   11797   23537   20387
Boundary for River Rch & Prof#=SHOATS CREEK,Reach-1,1
Up Type=0
Dn Type=3
Dn Slope=0.005
Boundary for River Rch & Prof#=SHOATS CREEK,Reach-1,2
Up Type=0
Dn Type=3
Dn Slope=0.005
Boundary for River Rch & Prof#=SHOATS CREEK,Reach-1,3
Up Type=0
Dn Type=3
Dn Slope=0.005
Boundary for River Rch & Prof#=SHOATS CREEK,Reach-1,4
Up Type=0
Dn Type=3
Dn Slope=0.005
Boundary for River Rch & Prof#=SHOATS CREEK,Reach-1,5
Up Type=0
Dn Type=3
Dn Slope=0.005
Boundary for River Rch & Prof#=SHOATS CREEK,Reach-1,6
Up Type=0
Dn Type=3
Dn Slope=0.005
Boundary for River Rch & Prof#=SHOATS CREEK,Reach-1,7
Up Type=0
Dn Type=3
Dn Slope=0.005

--- SHOATS CREEK.g01 (geometry) ---

Geom Title=Existing Conditions
Program Version=4.10

River Reach=SHOATS CREEK    ,Reach-1
Reach XY= 30
        2406675.       13596375.      2409335.75     13600734.71
      2410088.36     13600488.39      2411414.18     13602264.68
      2411451.48     13603352.01      2413827.47     13603880.45
       2416250.1     13605725.24      2420474.99     13603032.53
      2424004.96     13603324.95      2425014.57     13602676.03
      2426109.78     13603874.77      2427518.25      13602434.1
      2428928.21     13602817.13      2430300.04     13601924.51
      2432690.88     13603224.48      2434923.75     13602778.51
      2435585.75     13603824.32        2435925.       13602775.
      2437878.32     13603116.96      2438530.44     13601480.24
      2439323.29      13602071.7      2440715.19     13600285.42
      2441661.37     13600288.21      2442111.73     13597938.12
      2443659.31     13598191.78      2444078.53     13595826.45
      2445464.98     13594236.23        2447375.     13593732.06
        2448475.       13594925.        2449925.       13594625.

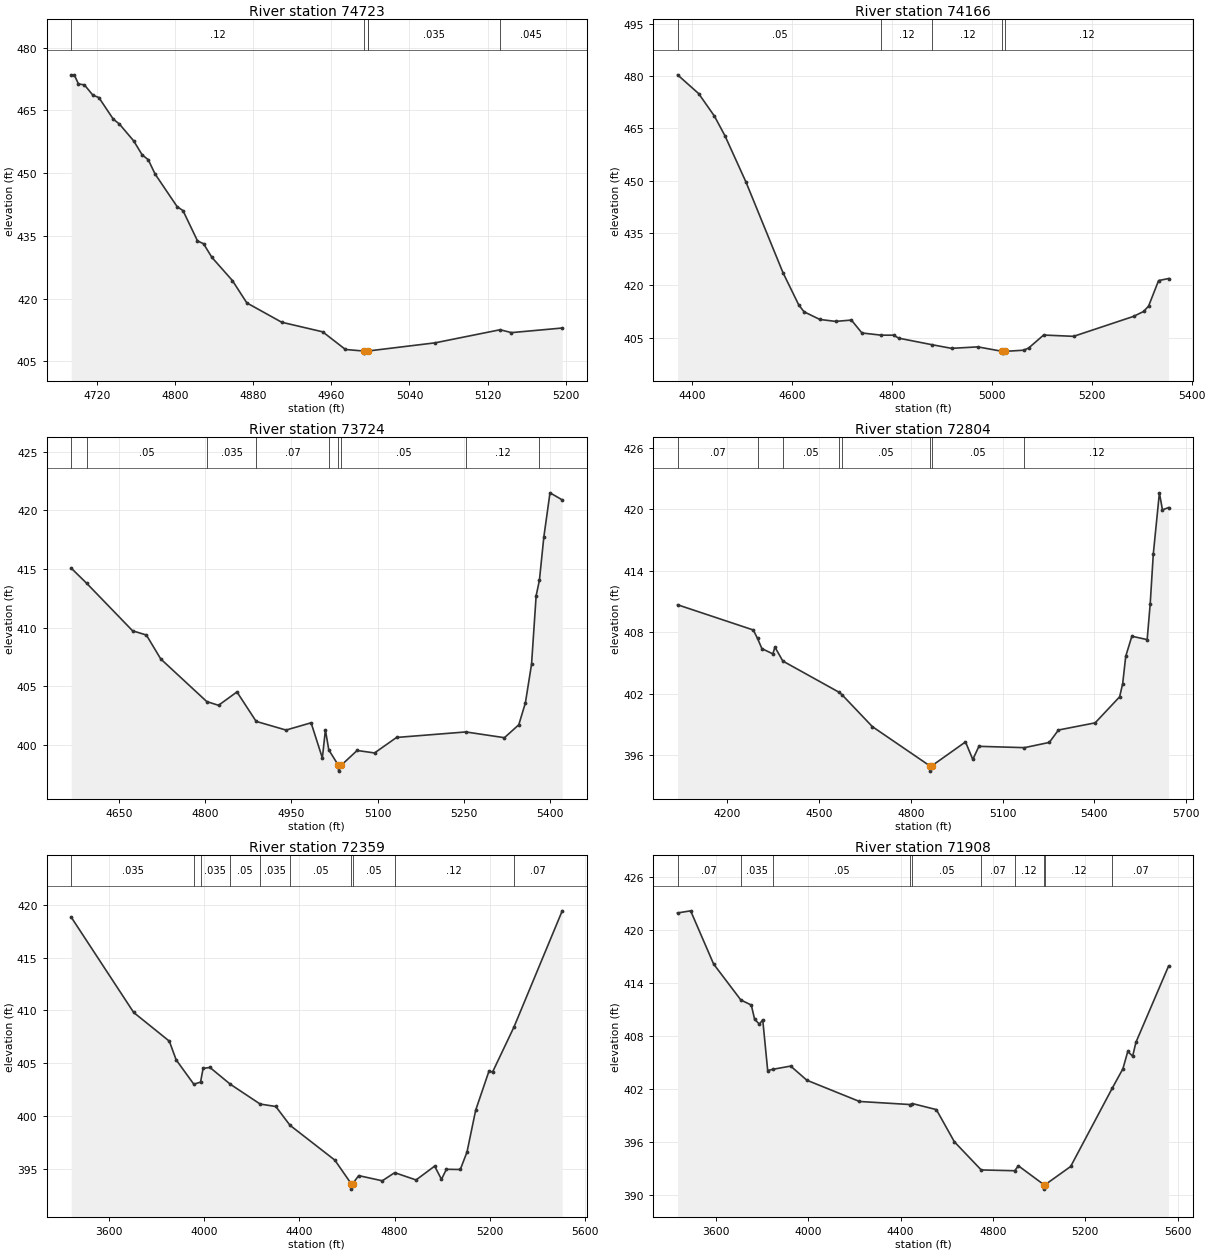
Type RM Length L Ch R = 1 ,74723   ,557,557,557
BEGIN DESCRIPTION:
SHOATS CREEK 104.0
END DESCRIPTION:
XS GIS Cut Line= 3
        2406525.       13596725.      2406797.52     13596532.05
      2406920.43     13596416.81
#Sta/Elev= 30
  4693.9  473.49    4697  473.49  4701.3  471.31  4707.4  471.09  4716.1  468.62
  4722.2  468.06    4737  462.88  4743.1  461.76  4757.9  457.68  4766.5  454.36
  4772.7  453.21  4779.7  449.79  4802.2  442.01  4808.3  441.03  4823.1  433.81
  4829.3  433.12  4837.9  429.85  4858.8  424.33  4873.6  418.98  4909.3  414.36
  4951.2  412.07  4974.5  407.85  4993.2  407.48  4993.5  406.98  4997.7  407.48
    4998   407.5  5066.2  409.44  5132.8  412.57  5144.3  411.88  5196.3  412.98
#Mann= 5 ,-1 , 0
  4693.9     .12       0  4993.2    .035       0  4997.7     .12       0
    4998    .035       0  5132.8    .045       0
Bank Sta=4993.2,4997.7
XS Rating Curve= 0 ,0
Exp/Cntr=0.3,0.1

Type RM Length L Ch R = 1 ,74166   ,442,442,442
BEGIN DESCRIPTION:
SHOATS CREEK 103.0
END DESCRIPTION:
XS GIS Cut Line= 3
      2406475.01       13596775.        2407075.       13596975.
      2407424.95       13596975.
#Sta/Elev= 30
  4371.4  480.33  4413.6  474.96  4445.2   468.5  4466.3  462.86  4508.4  449.58
  4582.2   423.7  4613.8  414.44  4624.4  412.46    4656  410.26  4687.6   409.7
  4719.2  410.08  4740.3  406.38  4778.6  405.76  4803.6  405.75  4814.1  404.89
  4881.3     403  4919.5  401.98  4972.2   402.4  5021.5  401.11  5021.8  400.61
  5026.2  401.11  5063.8  401.45  5073.8  402.07  5103.8  405.79  5163.8  405.42
  5283.8  411.14  5303.8  412.54  5313.8  414.09  5333.8  421.39  5353.8  421.98
#Mann= 5 ,-1 , 0
  4371.4     .05       0  4778.6     .12       0  4881.3     .12       0
  5021.5    .045       0  5026.2     .12       0
Bank Sta=5021.5,5026.2
XS Rating Curve= 0 ,0
Exp/Cntr=0.3,0.1

Type RM Length L Ch R = 1 ,73724   ,920,920,920
BEGIN DESCRIPTION:
SHOATS CREEK 102.0
END DESCRIPTION:
XS GIS Cut Line= 3
      2406624.99       13597525.        2407025.       13597375.
      2407424.99       13597225.
#Sta/Elev= 30
  4566.9  415.07    4594  413.77  4673.7  409.73  4697.7  409.37  4722.7  407.33
  4802.7   403.7  4823.2  403.38  4855.3  404.52  4888.7  402.01  4940.7  401.27
  4984.3  401.89  5003.9  398.89  5009.2  401.28  5015.1  399.58  5031.7  398.27
  5032.1  397.77  5036.7  398.27  5064.4  399.53  5094.7  399.32    5133  400.64
  5253.5  401.11  5320.7  400.62  5345.7  401.72  5357.2  403.59  5367.9  406.88
  5375.9  412.72  5381.6  414.04  5389.3  417.73    5400  421.49  5421.3  420.89
#Mann= 9 ,-1 , 0
  4566.9     .07       0    4594     .05       0  4802.7    .035       0
  4888.7     .07       0  5015.1     .05       0  5031.7     .05       0
  5036.7     .05       0  5253.5     .12       0  5381.6    .045       0
Bank Sta=5031.7,5036.7
XS Rating Curve= 0 ,0
Exp/Cntr=0.3,0.1

Type RM Length L Ch R = 1 ,72804   ,445,445,445
BEGIN DESCRIPTION:
SHOATS CREEK 101.0
END DESCRIPTION:
XS GIS Cut Line= 3
      2406725.02     13598574.98        2407425.       13597925.
        2407425.     13597275.03
#Sta/Elev= 30
  4037.4  410.68  4284.9  408.22  4298.9  407.39  4313.2   406.4  4348.9  405.89
  4355.7  406.55  4381.5  405.19  4564.5  402.16  4574.8  401.91  4674.3  398.79
  4862.8  394.95  4863.2  394.45  4867.8  394.95  4978.7   397.3  5002.6  395.59
  5022.6  396.87  5171.4  396.74  5252.6  397.25  5282.6  398.46  5402.6  399.16
  5482.6   401.7  5492.6  402.99  5502.6  405.66  5522.6  407.61  5572.6  407.28
  5582.6  410.79  5592.6  415.61  5612.6   421.6  5622.6  419.94  5642.6  420.16
#Mann= 8 ,-1 , 0
  4037.4     .07       0  4298.9    .035       0  4381.5     .05       0
  4564.5     .07       0  4574.8     .05       0  4862.8     .05       0
  4867.8     .05       0  5171.4     .12       0
Bank Sta=4862.8,4867.8
XS Rating Curve= 0 ,0
Exp/Cntr=0.3,0.1

Type RM Length L Ch R = 1 ,72359   ,451,451,451
BEGIN DESCRIPTION:
SHOATS CREEK 100.0
END DESCRIPTION:
XS GIS Cut Line= 3
      2406774.97     13599225.04        2407775.       13598025.
        2408175.       13597725.
#Sta/Elev= 30
    3442  418.83  3704.3   409.8    3854  407.08  3882.7  405.31  3956.9     403
  3985.1   403.2  3995.9   404.5  4024.6  404.59  4110.1     403  4235.6  401.12
  4301.2  400.89  4360.8  399.11  4549.1  395.81  4618.2  393.56  4618.6  393.06
  4623.3  393.56  4649.4  394.34  4748.3  393.85  4800.5  394.62  4890.2  393.93
  4968.3  395.24  4996.9  393.99  5017.6  394.94    5076  394.92  5104.1  396.57
  5140.6  400.54  5196.8  404.27  5211.4  404.15  5301.2  408.41  5504.1  419.43
#Mann= 10 ,-1 , 0
    3442    .035       0  3956.9     .05       0  3985.1    .035       0
  4110.1     .05       0  4235.6    .035       0  4360.8     .05       0
  4618.2     .05       0  4623.3     .05       0  4800.5     .12       0
  5301.2     .07       0
Bank Sta=4618.2,4623.3
XS Rating Curve= 0 ,0
Exp/Cntr=0.3,0.1

Type RM Length L Ch R = 1 ,71908   ,423,423,423
BEGIN DESCRIPTION:
SHOATS CREEK 99.0
END DESCRIPTION:
XS GIS Cut Line= 3
      2406824.97     13599375.03        2408025.       13598375.
      2408425.02     13597974.98
#Sta/Elev= 30
  3433.1  421.89  3489.8  422.13  3589.3  416.12  3707.4  412.05  3752.7  411.48
    3767  409.87  3787.9  409.32  3802.2  409.82  3823.7  404.08  3847.1  404.22
  3923.2  404.58  3993.5  402.98  4221.3  400.58    4442  400.23  4451.1  400.34
  4554.6  399.66  4632.7  396.02  4748.9  392.84  4894.3  392.75  4909.9  393.31
  5020.9  391.17  5021.3  390.67    5026  391.17  5136.6  393.23  5317.8  402.13
  5362.9  404.27  5384.1  406.23  5405.3   405.7  5419.5  407.27  5560.9  415.89
#Mann= 10 ,-1 , 0
  3433.1     .07       0  3707.4    .035       0  3847.1     .05       0
    4442    .035       0  4451.1     .05       0  4748.9     .07       0
  4894.3     .12       0  5020.9     .05       0    5026     .12       0
  5317.8     .07       0
Bank Sta=5020.9,5026
XS Rating Curve= 0 ,0
Exp/Cntr=0.3,0.1

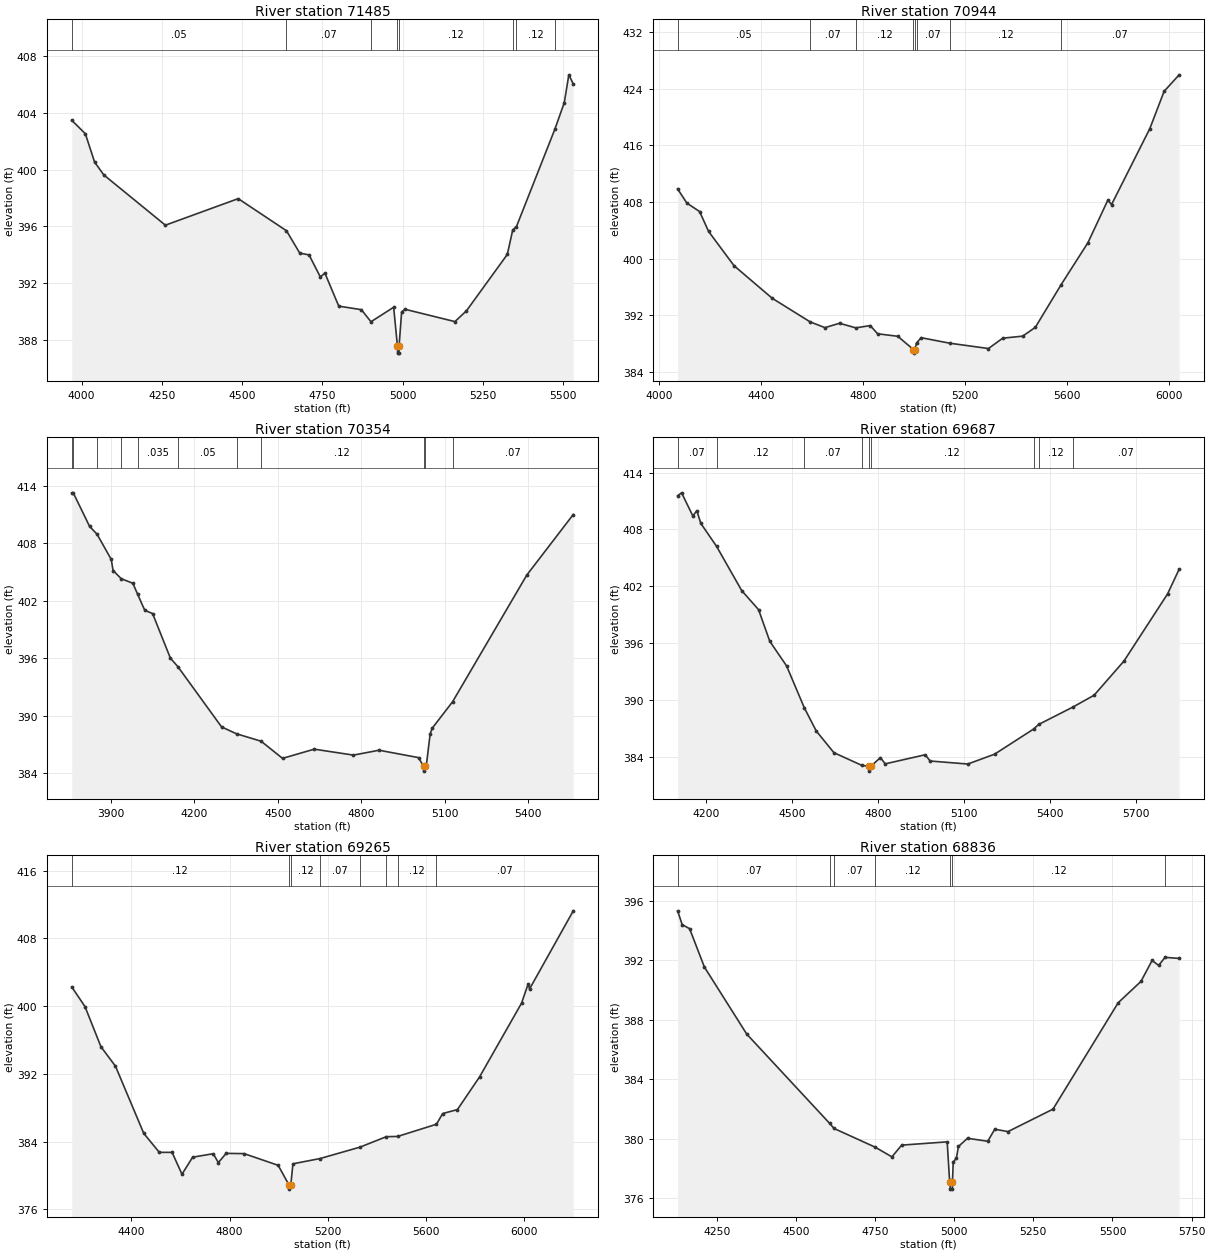
Type RM Length L Ch R = 1 ,71485   ,541,541,541
BEGIN DESCRIPTION:
SHOATS CREEK 98.0
END DESCRIPTION:
XS GIS Cut Line= 3
      2407474.98     13599325.01        2408275.       13598675.
        2408625.       13598275.
#Sta/Elev= 30
  3969.1  403.47  4011.5  402.52  4040.2  400.53    4069  399.62  4260.8  396.08
  4487.7  397.95    4638  395.69  4679.5  394.11  4708.3  393.99  4743.4  392.44
  4757.8   392.7  4800.9  390.38  4871.3  390.13  4901.2  389.28  4971.9   390.3
  4983.7  387.57  4984.1  387.07  4988.5  387.07  4988.8  387.57  4996.7  389.96
    5007  390.16  5162.7  389.29  5198.7  390.05  5325.9  394.02  5342.9  395.75
  5354.4  395.98  5474.4  402.86  5503.4  404.71  5517.6  406.67  5531.4  406.03
#Mann= 8 ,-1 , 0
  3969.1     .05       0    4638     .07       0  4901.2     .12       0
  4983.7     .05       0  4988.8     .12       0  5342.9    .035       0
  5354.4     .12       0  5474.4     .07       0
Bank Sta=4983.7,4988.8
XS Rating Curve= 0 ,0
Exp/Cntr=0.3,0.1

Type RM Length L Ch R = 1 ,70944   ,590,590,590
BEGIN DESCRIPTION:
SHOATS CREEK 97.0
END DESCRIPTION:
XS GIS Cut Line= 3
      2407724.98     13599775.03      2408292.78      13599029.3
      2409094.38     13598381.85
#Sta/Elev= 30
  4072.2  409.85  4108.6  407.84  4158.5  406.65  4193.8  403.84  4293.6     399
  4443.3   394.4  4592.4  391.06  4650.4  390.25  4707.4  390.87  4771.3  390.22
    4828  390.54  4857.1  389.38    4936  389.03  4997.7  387.15  4998.2  386.65
  5003.2  387.15  5009.6  388.08    5028  388.83  5140.2  388.05  5291.8   387.3
  5347.8  388.76  5426.1  389.05  5475.7  390.29  5576.9  396.32    5682  402.24
  5760.3  408.26  5774.7  407.63    5925  418.37    5981  423.63  6039.9  425.96
#Mann= 8 ,-1 , 0
  4072.2     .05       0  4592.4     .07       0  4771.3     .12       0
  4997.7     .05       0  5003.2     .12       0  5009.6     .07       0
  5140.2     .12       0  5576.9     .07       0
Bank Sta=4997.7,5003.2
XS Rating Curve= 0 ,0
Exp/Cntr=0.3,0.1

Type RM Length L Ch R = 1 ,70354   ,667,667,667
BEGIN DESCRIPTION:
SHOATS CREEK 96.0
END DESCRIPTION:
XS GIS Cut Line= 3
      2407824.98     13599875.02      2408508.59     13599283.65
      2409179.15     13598682.46
#Sta/Elev= 30
  3758.8  413.23  3764.3  413.26    3823  409.76  3849.9  408.94  3900.9  406.32
  3907.5  405.16  3936.6  404.31  3978.7  403.83  3995.6   402.7  4021.5  401.01
  4049.7  400.67  4113.6  396.03  4141.3  395.11  4297.9  388.85  4351.9  388.13
  4440.1  387.36  4517.3  385.57  4631.3  386.53  4772.5  385.91  4864.5  386.42
  5006.5  385.65  5024.7  384.74  5025.1  384.24  5030.3  384.74  5034.2  384.74
  5048.4  388.13  5055.9  388.72    5129  391.47    5396  404.68  5563.3     411
#Mann= 11 ,-1 , 0
  3758.8    .035       0  3764.3     .07       0  3849.9     .05       0
  3936.6     .07       0  3995.6    .035       0  4141.3     .05       0
  4351.9     .07       0  4440.1     .12       0  5024.7     .05       0
  5030.3     .12       0    5129     .07       0
Bank Sta=5024.7,5030.3
XS Rating Curve= 0 ,0
Exp/Cntr=0.3,0.1

Type RM Length L Ch R = 1 ,69687   ,422,422,422
BEGIN DESCRIPTION:
SHOATS CREEK 95.0
END DESCRIPTION:
XS GIS Cut Line= 3
      2408025.04     13600024.98        2408825.       13599625.
      2409125.01     13598824.98
#Sta/Elev= 30
  4101.7  411.56  4115.6  411.87  4154.8  409.43  4168.7  409.98  4182.7  408.64
  4237.5  406.22  4325.3  401.54    4384  399.53  4423.1  396.19  4481.8  393.58
  4543.7  389.15  4585.2  386.71  4646.7  384.42    4744  383.08  4769.7  382.97
  4770.1  382.47  4775.3  382.97  4808.8   383.9  4825.6  383.24  4965.3   384.2
  4982.1  383.54  5113.6  383.22    5207  384.26  5342.8  386.91  5360.7   387.4
  5480.8  389.25  5554.1  390.49  5658.2   394.1  5810.4   401.2  5850.5   403.8
#Mann= 9 ,-1 , 0
  4101.7     .07       0  4237.5     .12       0  4543.7     .07       0
    4744     .12       0  4769.7     .05       0  4775.3     .12       0
  5342.8     .07       0  5360.7     .12       0  5480.8     .07       0
Bank Sta=4769.7,4775.3
XS Rating Curve= 0 ,0
Exp/Cntr=0.3,0.1

Type RM Length L Ch R = 1 ,69265   ,429,429,429
BEGIN DESCRIPTION:
SHOATS CREEK 94.0
END DESCRIPTION:
XS GIS Cut Line= 3
      2408325.04     13600124.99        2409125.       13599875.
        2409225.     13598674.97
#Sta/Elev= 30
  4157.3  402.26  4211.2  399.94  4276.2   395.2  4335.4   392.9  4450.6  384.97
    4514  382.73  4565.9  382.73  4606.2  380.15  4649.7  382.16  4733.5  382.57
  4754.4  381.52  4785.9  382.61  4859.2  382.58  4997.9   381.2  5041.8  378.89
  5042.3  378.39  5049.3  378.89  5058.1  381.38  5168.5     382  5331.5  383.35
  5438.2  384.58  5484.4  384.61  5642.6  386.05  5667.7  387.31  5727.9  387.78
  5818.3  391.65  5988.8  400.33  6016.4  402.64  6021.5  402.01  6199.6  411.24
#Mann= 8 ,-1 , 0
  4157.3     .12       0  5041.8     .05       0  5049.3     .12       0
  5168.5     .07       0  5331.5     .12       0  5438.2     .07       0
  5484.4     .12       0  5642.6     .07       0
Bank Sta=5041.8,5049.3
XS Rating Curve= 0 ,0
Exp/Cntr=0.3,0.1

Type RM Length L Ch R = 1 ,68836   ,888,888,888
BEGIN DESCRIPTION:
SHOATS CREEK 93.0
END DESCRIPTION:
XS GIS Cut Line= 3
      2408574.96     13600525.02        2409375.       13600175.
      2409825.01     13599624.99
#Sta/Elev= 30
  4126.6  395.33  4141.1   394.4  4164.5  394.13  4211.2  391.55  4344.9  387.04
  4606.9  381.03  4620.7  380.69  4750.8  379.43  4803.4  378.78  4834.2  379.57
    4978  379.79  4985.4  377.23  4987.1  377.11  4987.6  376.61  4994.2  376.61
  4994.7  377.11  4997.1  378.44    5007  378.68  5013.5  379.48  5042.2  380.03
  5106.1  379.83  5128.3  380.64    5170  380.48  5312.1  381.99  5518.1  389.15
  5589.9  390.58  5625.1  391.99  5645.9  391.66    5666   392.2  5710.5  392.13
#Mann= 7 ,-1 , 0
  4126.6     .07       0  4606.9     .12       0  4620.7     .07       0
  4750.8     .12       0  4987.1     .05       0  4994.7     .12       0
    5666     .07       0
Bank Sta=4987.1,4994.7
XS Rating Curve= 0 ,0
Exp/Cntr=0.3,0.1

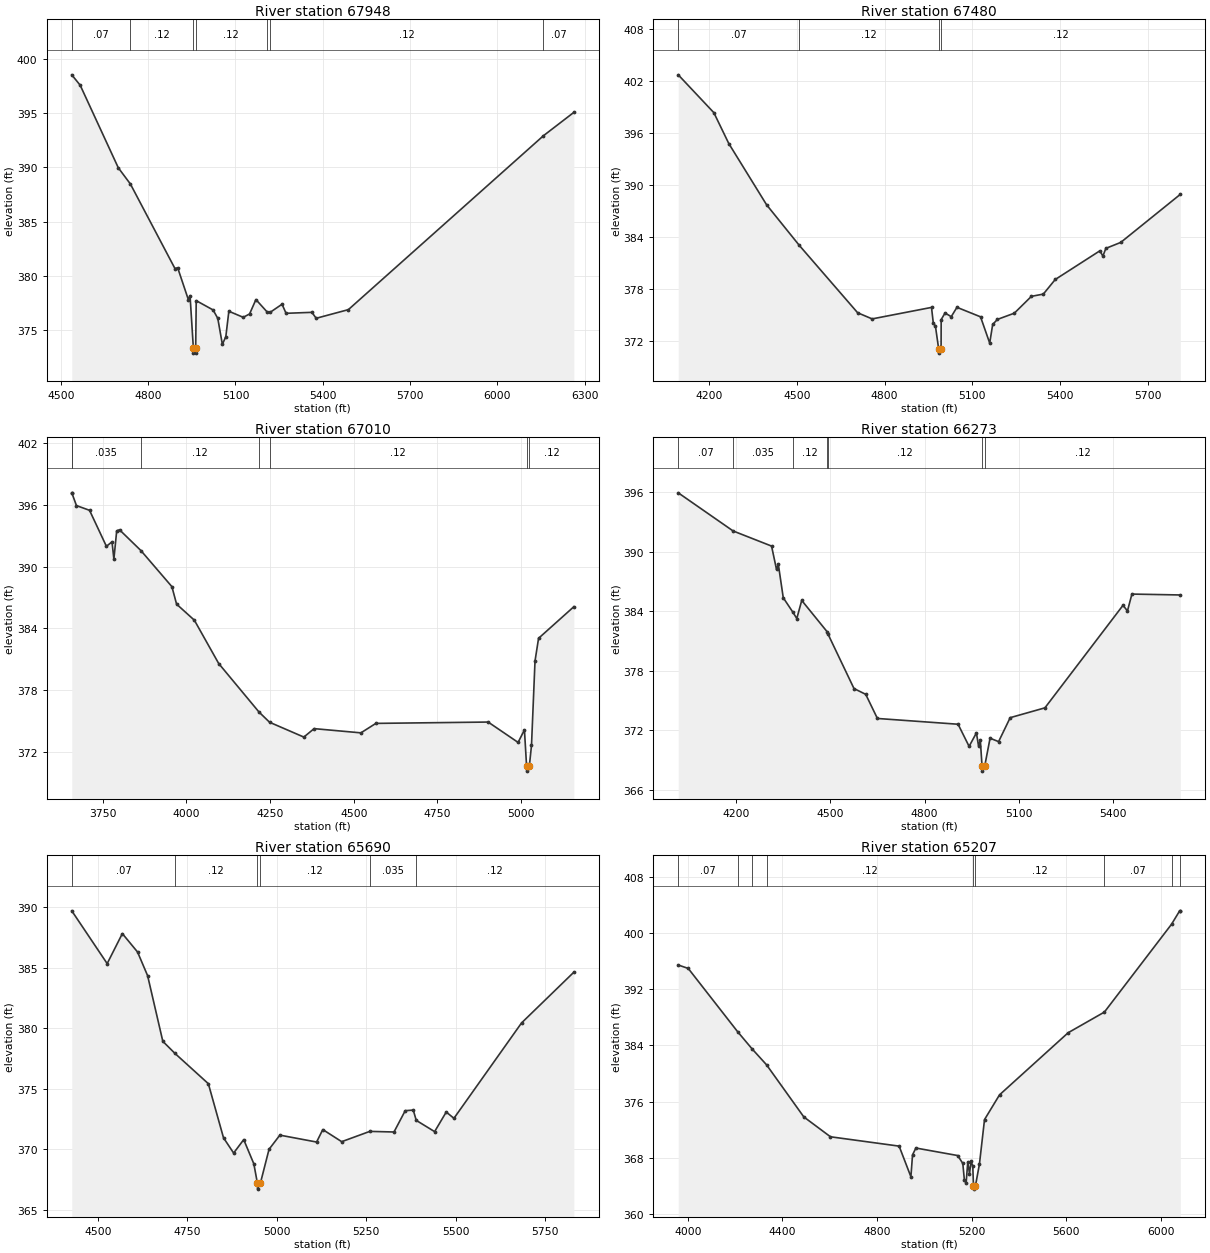
Type RM Length L Ch R = 1 ,67948   ,468,468,468
BEGIN DESCRIPTION:
SHOATS CREEK 92.0
END DESCRIPTION:
XS GIS Cut Line= 3
      2409274.98     13601175.04        2409525.       13600775.
      2410124.98     13599675.04
#Sta/Elev= 30
  4537.6  398.56  4566.5   397.6  4697.4  389.97    4739  388.47    4892  380.66
  4901.4  380.73    4938  377.79  4943.9  378.15  4955.2  373.34  4955.7  372.84
  4962.8  372.84  4963.3  373.34  4965.1  377.69  5023.1  376.83  5039.2  376.05
  5054.9  373.65  5066.8  374.36  5077.2  376.71  5126.6  376.15  5148.4  376.46
  5170.2  377.79  5208.2  376.66  5218.5   376.6  5259.9  377.36  5273.7  376.52
  5362.5  376.61  5377.2  376.06  5487.8  376.86  6157.8  392.93  6262.3  395.09
#Mann= 7 ,-1 , 0
  4537.6     .07       0    4739     .12       0  4955.2     .05       0
  4963.3     .12       0  5208.2     .07       0  5218.5     .12       0
  6157.8     .07       0
Bank Sta=4955.2,4963.3
XS Rating Curve= 0 ,0
Exp/Cntr=0.3,0.1

Type RM Length L Ch R = 1 ,67480   ,470,470,470
BEGIN DESCRIPTION:
SHOATS CREEK 91.0
END DESCRIPTION:
XS GIS Cut Line= 3
      2409375.02     13601524.97        2409875.       13600775.
        2410025.     13599974.99
#Sta/Elev= 30
    4095  402.75  4216.7  398.37  4267.7   394.8  4396.9  387.71  4508.5  383.02
  4707.9  375.22  4757.5  374.51  4960.3  375.84  4966.3  374.06  4973.8  373.65
  4984.7  371.05  4985.2  370.55    4993  371.05  4993.3  374.43  5006.5  375.19
  5027.7  374.77  5047.2  375.85  5127.8  374.75  5159.1  371.71  5169.3  373.87
  5185.4  374.45  5243.1  375.17  5301.6  377.12  5342.3  377.38    5383  379.07
  5535.6  382.39  5545.8  381.77  5555.9  382.67  5606.8  383.36  5810.3  388.92
#Mann= 4 ,-1 , 0
    4095     .07       0  4508.5     .12       0  4984.7     .05       0
    4993     .12       0
Bank Sta=4984.7,4993
XS Rating Curve= 0 ,0
Exp/Cntr=0.3,0.1

Type RM Length L Ch R = 1 ,67010   ,737,737,737
BEGIN DESCRIPTION:
SHOATS CREEK 90.0
END DESCRIPTION:
XS GIS Cut Line= 3
      2409524.99     13601725.03        2410125.       13600525.
      2410275.01       13600475.
#Sta/Elev= 30
  3657.7  397.18  3657.8  397.18  3671.7  395.94  3710.8  395.48  3761.2  391.98
  3777.9  392.42  3783.5  390.74  3791.9  393.48  3800.3  393.59  3864.2  391.57
  3956.8  388.06  3970.8  386.36  4023.9   384.8  4096.6  380.59  4217.1  375.87
  4248.6  374.88  4350.9  373.44  4381.7  374.26  4521.4  373.85  4566.1  374.77
  4901.5   374.9    4991  372.92  5009.9  374.14  5016.3  370.63  5016.8  370.13
  5024.6  370.63    5031  372.63  5041.5  380.83  5052.1  383.04  5157.5  386.11
#Mann= 7 ,-1 , 0
  3657.7     .07       0  3657.8    .035       0  3864.2     .12       0
  4217.1     .07       0  4248.6     .12       0  5016.3     .05       0
  5024.6     .12       0
Bank Sta=5016.3,5024.6
XS Rating Curve= 0 ,0
Exp/Cntr=0.3,0.1

Type RM Length L Ch R = 1 ,66273   ,583,583,583
BEGIN DESCRIPTION:
E20816
END DESCRIPTION:
XS GIS Cut Line= 4
      2409541.41     13601857.97      2409980.74     13601102.63
      2410273.63     13600925.36      2410543.41     13600655.58
#Sta/Elev= 30
  4016.2  395.91  4190.9  392.07  4313.2  390.55  4328.9   388.2  4334.7  388.72
  4350.4  385.35  4380.1  383.94  4393.5  383.26  4409.2  385.08  4490.5  381.91
  4492.2  381.73  4575.5  376.21  4612.8  375.63    4650   373.2  4906.7  372.62
  4941.8  370.39  4965.1  371.75  4971.7  370.45  4977.5     371    4983   368.4
  4983.5   367.9  4991.4   368.4  5008.5  371.21  5035.7  370.87  5072.5  373.28
  5183.1  374.27  5431.6  384.59  5445.7  384.02  5459.9  385.72  5613.9  385.63
#Mann= 7 ,-1 , 0
  4016.2     .07       0  4190.9    .035       0  4380.1     .12       0
  4490.5    .035       0  4492.2     .12       0    4983     .05       0
  4991.4     .12       0
Bank Sta=4983,4991.4
XS Rating Curve= 0 ,0
Exp/Cntr=0.3,0.1

Type RM Length L Ch R = 1 ,65690   ,483,483,483
BEGIN DESCRIPTION:
SHOATS CREEK 89.0
END DESCRIPTION:
XS GIS Cut Line= 3
      2409824.99     13601975.01        2410225.       13601575.
      2410475.01     13600774.96
#Sta/Elev= 30
  4426.5   389.7  4525.5  385.34  4567.9  387.82  4610.4   386.3  4638.6  384.34
  4681.1  378.92  4715.1  377.92  4808.4  375.42  4850.8  370.95  4879.1  369.69
  4907.3   370.8  4935.6   368.8  4945.5  367.21    4946  366.71    4954  367.21
  4978.1     370  5008.4  371.17  5111.1   370.6  5128.4  371.63  5181.3  370.63
  5259.9  371.48  5327.5  371.43  5358.9  373.19  5381.4  373.24  5389.7  372.39
  5441.1  371.46  5473.6  373.08  5495.1  372.56  5684.2  380.44  5830.4  384.63
#Mann= 6 ,-1 , 0
  4426.5     .07       0  4715.1     .12       0  4945.5     .05       0
    4954     .12       0  5259.9    .035       0  5389.7     .12       0
Bank Sta=4945.5,4954
XS Rating Curve= 0 ,0
Exp/Cntr=0.3,0.1

Type RM Length L Ch R = 1 ,65207   ,450,450,450
BEGIN DESCRIPTION:
SHOATS CREEK 88.0
END DESCRIPTION:
XS GIS Cut Line= 3
      2409875.01     13602274.99        2410625.       13601575.
      2411375.01     13600774.99
#Sta/Elev= 30
  3959.8  395.45  4002.1  394.96    4211  385.95  4272.5  383.49    4333  381.25
  4490.6  373.83  4603.4     371  4893.6  369.67  4943.4  365.31  4950.3  368.43
  4964.5   369.4  5141.3  368.33  5162.8  367.21  5169.6  364.79  5176.9  364.44
  5183.8  367.42  5191.1  365.76  5197.9  367.52    5205   366.8  5207.9  364.05
  5208.4  363.55  5216.4  364.05  5233.1  367.11  5254.6  373.45  5318.1  376.97
  5608.2  385.81  5761.4  388.75  6045.2  401.25  6079.6  403.16  6082.3  403.16
#Mann= 9 ,-1 , 0
  3959.8     .07       0    4211     .12       0  4272.5     .07       0
    4333     .12       0  5207.9     .05       0  5216.4     .12       0
  5761.4     .07       0  6045.2    .035       0  6079.6     .07       0
Bank Sta=5207.9,5216.4
XS Rating Curve= 0 ,0
Exp/Cntr=0.3,0.1

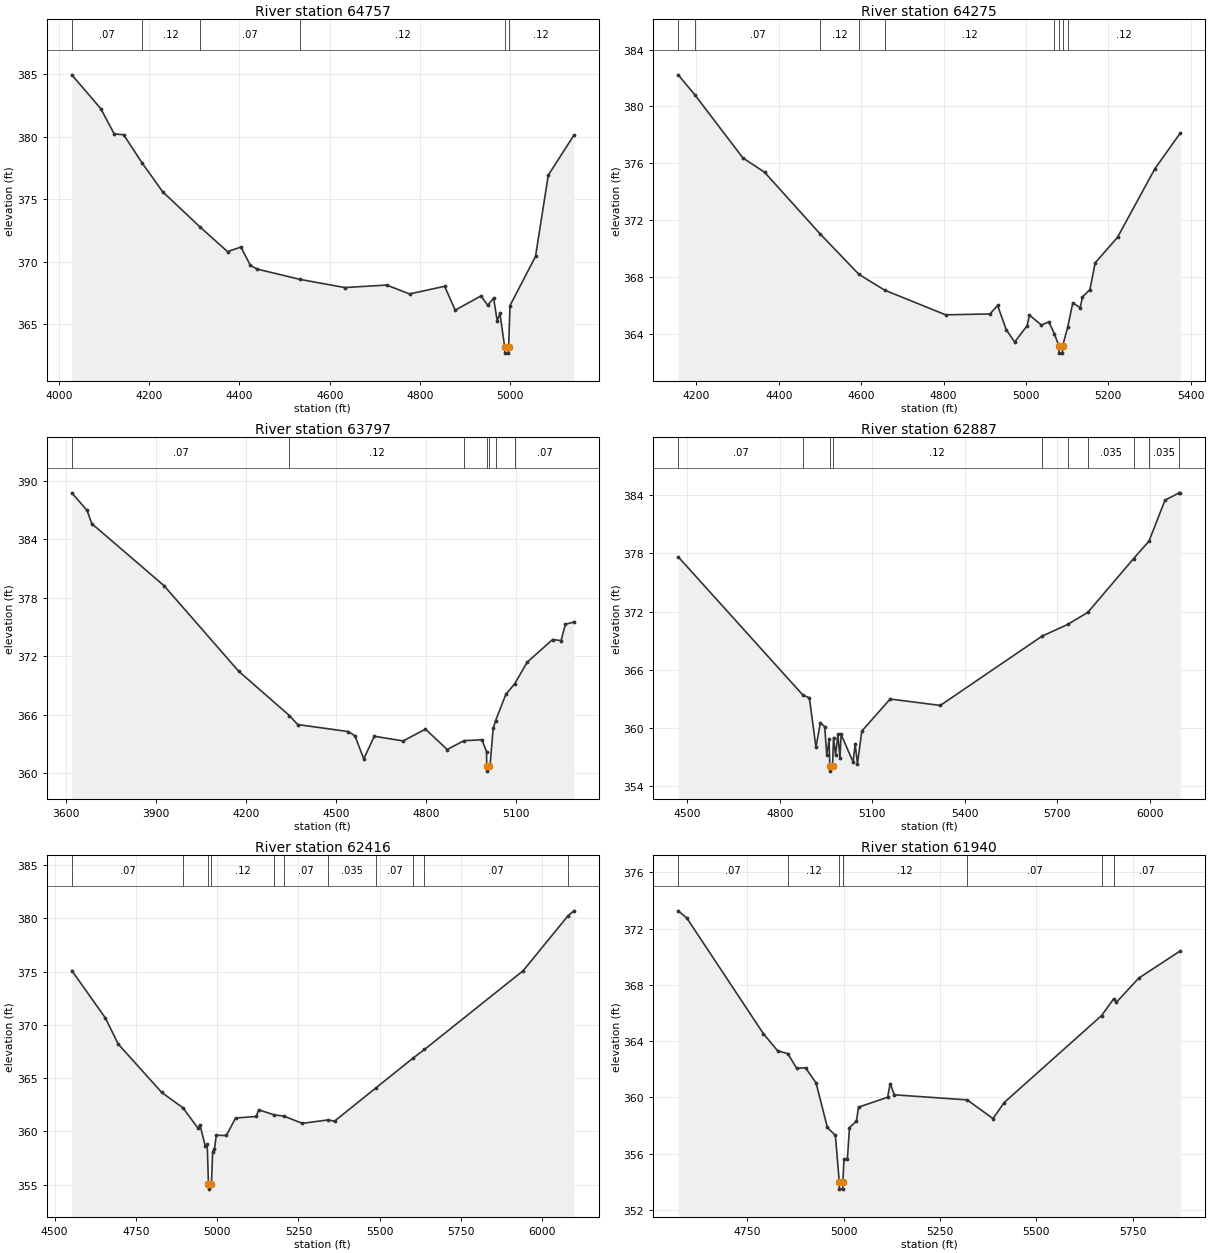
Type RM Length L Ch R = 1 ,64757   ,482,482,482
BEGIN DESCRIPTION:
SHOATS CREEK 87.0
END DESCRIPTION:
XS GIS Cut Line= 3
      2410125.04     13602174.98        2410925.       13601625.
        2411025.       13601525.
#Sta/Elev= 30
  4028.6  384.96  4092.8  382.26  4122.6  380.23  4143.6  380.16  4184.3  377.91
  4230.2  375.59  4312.7  372.78  4373.6  370.81  4403.4  371.17  4424.3   369.7
  4439.2  369.41  4534.6  368.58  4633.4  367.93  4726.1  368.13  4776.8  367.42
  4854.6  368.03    4878  366.12  4935.1  367.26    4950  366.51    4963  367.09
    4971  365.27    4977  365.86  4987.6  363.18  4988.1  362.68  4995.8  362.68
  4996.3  363.18  4999.4  366.49  5055.9  370.42  5084.2  376.93  5140.8  380.12
#Mann= 6 ,-1 , 0
  4028.6     .07       0  4184.3     .12       0  4312.7     .07       0
  4534.6     .12       0  4987.6     .05       0  4996.3     .12       0
Bank Sta=4987.6,4996.3
XS Rating Curve= 0 ,0
Exp/Cntr=0.3,0.1

Type RM Length L Ch R = 1 ,64275   ,478,478,478
BEGIN DESCRIPTION:
SHOATS CREEK 86.0
END DESCRIPTION:
XS GIS Cut Line= 3
      2410225.02     13602324.99        2411025.       13602075.
      2411174.99     13601725.02
#Sta/Elev= 30
    4156  382.23  4197.4  380.78  4313.1  376.37  4365.5  375.37  4500.5  371.02
  4594.7  368.17    4657  367.06    4805  365.32  4912.9  365.38  4931.3  365.98
  4952.2  364.28  4972.7   363.4  5003.2  364.56  5008.6   365.3  5037.7   364.6
  5055.8  364.82  5068.9  363.99  5080.4  363.12  5080.9  362.62  5088.6  362.62
  5089.1  363.12  5101.5  364.44  5113.8  366.16  5131.9  365.82  5137.4  366.59
  5155.5   367.1  5168.2  368.98  5222.6  370.79  5313.3  375.62  5374.9  378.13
#Mann= 9 ,-1 , 0
    4156     .12       0  4197.4     .07       0  4500.5     .12       0
  4594.7     .07       0    4657     .12       0  5068.9     .07       0
  5080.4     .05       0  5089.1     .07       0  5101.5     .12       0
Bank Sta=5080.4,5089.1
XS Rating Curve= 0 ,0
Exp/Cntr=0.3,0.1

Type RM Length L Ch R = 1 ,63797   ,910,910,910
BEGIN DESCRIPTION:
SHOATS CREEK 85.0
END DESCRIPTION:
XS GIS Cut Line= 3
      2410224.98     13602975.01        2411425.       13602275.
        2411625.       13602075.
#Sta/Elev= 30
  3620.2  388.76  3671.1  386.96  3686.8   385.6  3927.4  379.23  4175.9  370.45
  4344.8   365.9  4372.7  364.97  4541.8  364.25  4563.3  363.81  4592.7  361.45
  4627.8  363.77  4723.8  363.29  4798.2   364.5  4870.5  362.41  4926.7  363.32
  4986.3  363.41  5001.6  362.17  5002.2  360.69  5002.7  360.19    5011  360.69
    5013  360.69  5023.6  364.57  5031.5  365.36    5066  368.08  5095.8  369.18
  5136.7  371.37  5221.6   373.7  5249.9  373.59    5264  375.26  5292.3   375.5
#Mann= 7 ,-1 , 0
  3620.2     .07       0  4344.8     .12       0  4926.7     .07       0
  5002.2     .05       0    5011     .07       0  5031.5     .12       0
  5095.8     .07       0
Bank Sta=5002.2,5011
XS Rating Curve= 0 ,0
Exp/Cntr=0.3,0.1

Type RM Length L Ch R = 1 ,62887   ,471,471,471
BEGIN DESCRIPTION:
SHOATS CREEK 84.0
END DESCRIPTION:
XS GIS Cut Line= 3
      2410924.99     13603325.01        2411275.       13602925.
        2412025.       13602125.
#Sta/Elev= 30
  4470.4  377.63  4875.2  363.39  4895.6  363.13    4917  358.04  4931.2  360.56
  4945.4  360.15  4952.1  357.21  4959.7  358.85  4961.9  356.08  4962.4  355.58
  4970.8  356.08  4973.9  359.04  4980.6  357.26  4988.2  359.36  4994.8  356.91
  4998.6  359.36  5037.3  356.53  5044.2  358.35  5051.5  356.34  5065.7   359.7
  5157.5     363  5320.2  362.34  5650.2  369.47  5734.1  370.69  5798.6  371.92
    5947  377.45  5997.1  379.26  6048.9  383.47  6095.4  384.22  6098.5  384.22
#Mann= 10 ,-1 , 0
  4470.4     .07       0  4875.2     .12       0  4961.9     .05       0
  4970.8     .12       0  5650.2    .035       0  5734.1     .07       0
  5798.6    .035       0    5947     .07       0  5997.1    .035       0
  6095.4     .07       0
Bank Sta=4961.9,4970.8
XS Rating Curve= 0 ,0
Exp/Cntr=0.3,0.1

Type RM Length L Ch R = 1 ,62416   ,476,476,476
BEGIN DESCRIPTION:
SHOATS CREEK 83.0
END DESCRIPTION:
XS GIS Cut Line= 3
      2410974.99       13603325.        2411375.       13603125.
      2412124.99     13602325.01
#Sta/Elev= 30
  4552.9  375.11  4656.3  370.65  4695.5  368.21  4829.6  363.65  4894.8  362.21
  4941.4  360.28    4947   360.6  4963.8  358.58  4969.4  358.78  4973.2  355.07
  4973.7  354.57  4982.4  355.07  4986.1  358.08  4991.7  358.35  4997.3  359.63
  5028.2  359.61  5056.6  361.25  5120.5   361.4  5127.4  362.03  5173.9  361.56
  5206.3  361.42  5261.7  360.75  5340.5  361.07  5360.9  360.96  5488.9   364.1
  5600.9  366.85  5637.3  367.69  5941.1   375.1  6079.1  380.27  6096.7  380.72
#Mann= 11 ,-1 , 0
  4552.9     .07       0  4894.8     .12       0  4973.2     .05       0
  4982.4     .12       0  5173.9    .035       0  5206.3     .07       0
  5340.5    .035       0  5488.9     .07       0  5600.9    .035       0
  5637.3     .07       0  6079.1     .12       0
Bank Sta=4973.2,4982.4
XS Rating Curve= 0 ,0
Exp/Cntr=0.3,0.1

Type RM Length L Ch R = 1 ,61940   ,418,418,418
BEGIN DESCRIPTION:
SHOATS CREEK 82.0
END DESCRIPTION:
XS GIS Cut Line= 3
      2411274.96     13603725.03        2411625.       13603475.
      2411975.01     13602674.98
#Sta/Elev= 30
  4570.2  373.27  4592.4  372.76  4791.5  364.52  4828.3  363.31  4854.7  363.11
  4877.5  362.07  4900.8   362.1  4927.9  361.03  4957.4  357.86  4978.2  357.29
  4988.3  353.97  4988.8  353.47  4997.1  353.47  4997.6  353.97  5000.4  355.59
  5009.3  355.62  5014.8  357.85  5032.7   358.3  5038.2   359.3  5113.8  360.01
  5120.4  360.98  5131.3  360.18  5320.1  359.82  5387.5  358.49  5416.3  359.63
  5669.3  365.82  5700.6  367.01  5707.9  366.77  5765.6  368.48  5873.6  370.42
#Mann= 7 ,-1 , 0
  4570.2     .07       0  4854.7     .12       0  4988.3     .05       0
  4997.6     .12       0  5320.1     .07       0  5669.3     .12       0
  5700.6     .07       0
Bank Sta=4988.3,4997.6
XS Rating Curve= 0 ,0
Exp/Cntr=0.3,0.1

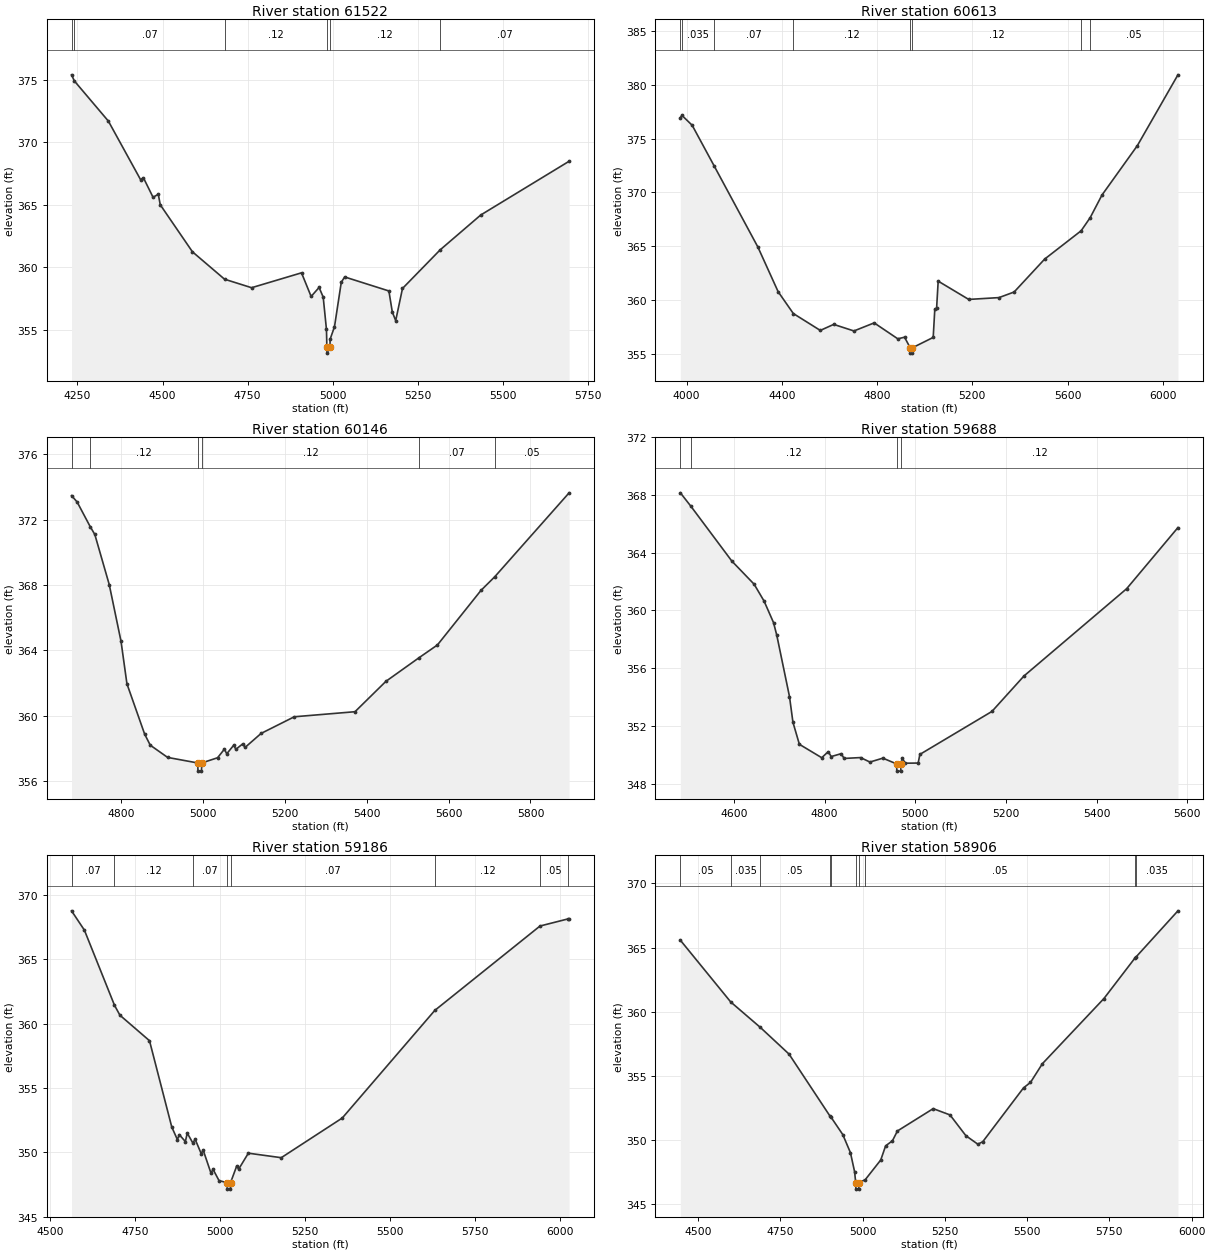
Type RM Length L Ch R = 1 ,61522   ,909,909,909
BEGIN DESCRIPTION:
SHOATS CREEK 81.0
END DESCRIPTION:
XS GIS Cut Line= 3
      2411574.98     13604125.04        2411975.       13603475.
        2411975.     13602774.96
#Sta/Elev= 30
  4232.5  375.39  4240.8   374.9  4340.8  371.69  4435.5  367.01  4443.9  367.16
  4472.2   365.6  4487.6  365.84  4493.4     365  4588.1  361.24  4682.5  359.05
    4762  358.37  4908.8  359.56  4937.1  357.67  4960.5  358.39  4972.6  357.62
  4982.2  355.03  4983.4  353.64  4983.9  353.14  4992.7  353.64  4992.8  354.24
  5005.8  355.25  5025.8  358.81  5035.8  359.23  5165.8  358.11  5175.8  356.43
  5185.8  355.74  5205.8  358.31  5316.7   361.4  5435.8  364.18  5695.8  368.48
#Mann= 6 ,-1 , 0
  4232.5    .035       0  4240.8     .07       0  4682.5     .12       0
  4983.4     .05       0  4992.7     .12       0  5316.7     .07       0
Bank Sta=4983.4,4992.7
XS Rating Curve= 0 ,0
Exp/Cntr=0.3,0.1

Type RM Length L Ch R = 1 ,60613   ,467,467,467
BEGIN DESCRIPTION:
SHOATS CREEK 80.0
END DESCRIPTION:
XS GIS Cut Line= 3
      2411574.97     13604225.03        2412325.       13603525.
      2413025.02     13602724.98
#Sta/Elev= 30
  3974.1  376.95  3980.8  377.15  4023.7  376.23  4115.1  372.49  4299.7  364.91
  4384.5  360.77  4448.3  358.74  4561.6  357.17  4617.8  357.73  4702.8  357.12
  4787.8  357.87    4887  356.39  4915.3  356.54  4938.9  355.56  4939.4  355.06
  4947.9  355.06  4948.4  355.56  5035.6  356.52  5042.3  359.13  5049.9  359.24
  5056.5  361.75  5184.7  360.05  5311.8  360.22  5375.4  360.74  5503.6   363.8
  5656.7  366.43  5694.7  367.65  5744.2  369.75  5892.7  374.34  6063.1  380.92
#Mann= 8 ,-1 , 0
  3974.1     .07       0  3980.8    .035       0  4115.1     .07       0
  4448.3     .12       0  4938.9     .05       0  4948.4     .12       0
  5656.7     .07       0  5694.7     .05       0
Bank Sta=4938.9,4948.4
XS Rating Curve= 0 ,0
Exp/Cntr=0.3,0.1

Type RM Length L Ch R = 1 ,60146   ,458,458,458
BEGIN DESCRIPTION:
SHOATS CREEK 79.0
END DESCRIPTION:
XS GIS Cut Line= 3
      2412425.03     13603974.97        2412625.       13603725.
      2413024.98     13602925.04
#Sta/Elev= 30
  4679.8  373.48  4693.4  373.09  4725.3  371.58  4736.6   371.1  4771.8  368.03
  4800.6  364.55    4815  361.95  4858.2  358.87  4871.9  358.19  4914.3  357.44
  4987.9   357.1  4988.4   356.6    4997   356.6  4997.5   357.1  5036.3  357.42
    5053  357.95  5058.6  357.66  5075.4  358.18    5081  357.94  5097.7  358.27
  5103.3  358.05  5142.5  358.91  5223.5  359.93  5371.7  360.24  5447.1   362.1
  5528.7  363.56  5572.9  364.33  5679.1  367.67  5712.9  368.51  5894.3  373.65
#Mann= 6 ,-1 , 0
  4679.8     .07       0  4725.3     .12       0  4987.9     .05       0
  4997.5     .12       0  5528.7     .07       0  5712.9     .05       0
Bank Sta=4987.9,4997.5
XS Rating Curve= 0 ,0
Exp/Cntr=0.3,0.1

Type RM Length L Ch R = 1 ,59688   ,502,502,502
BEGIN DESCRIPTION:
SHOATS CREEK 78.0
END DESCRIPTION:
XS GIS Cut Line= 3
      2412675.03     13604024.97        2413025.       13603625.
      2413424.96     13603225.04
#Sta/Elev= 30
  4482.1  368.16  4505.5  367.22  4595.5  363.43  4644.8  361.82  4666.7  360.65
  4687.5  359.16  4694.7  358.28  4722.7  354.03  4730.3  352.25  4744.5  350.72
  4793.8  349.79  4808.1  350.21  4814.7  349.87  4836.6  350.07  4843.2  349.74
  4879.3   349.8  4900.1  349.49  4928.6  349.76  4958.9  349.36  4959.4  348.86
    4968  348.86  4968.5  349.36  4971.3  349.76    4978  349.41  5006.4  349.42
  5010.2  350.02  5169.1     353  5239.8  355.46  5466.1  361.51  5579.2  365.75
#Mann= 4 ,-1 , 0
  4482.1     .07       0  4505.5     .12       0  4958.9     .05       0
  4968.5     .12       0
Bank Sta=4958.9,4968.5
XS Rating Curve= 0 ,0
Exp/Cntr=0.3,0.1

Type RM Length L Ch R = 1 ,59186   ,280,280,280
BEGIN DESCRIPTION:
SHOATS CREEK 77.0
END DESCRIPTION:
XS GIS Cut Line= 3
      2412725.02     13604124.99       2413202.5     13603915.89
      2413765.14     13603160.57
#Sta/Elev= 30
  4563.8  368.75  4601.6  367.25  4690.1  361.42    4706  360.65    4793  358.67
  4858.5  351.97  4875.1  350.99  4880.6  351.38  4898.5  350.84    4904   351.5
  4920.3  350.74  4927.4  351.01  4945.3  349.89  4950.7  350.19  4974.1  348.37
  4979.6   348.7  4997.5  347.81  5021.4  347.65  5021.9  347.15  5030.8  347.15
  5031.3  347.65  5049.7  348.96  5055.2   348.7  5083.7  349.94  5180.5  349.59
  5359.9  352.67  5631.9  361.02  5941.3  367.57  6024.7  368.13  6026.9  368.13
#Mann= 8 ,-1 , 0
  4563.8     .07       0  4690.1     .12       0  4920.3     .07       0
  5021.4     .05       0  5031.3     .07       0  5631.9     .12       0
  5941.3     .05       0  6024.7    .035       0
Bank Sta=5021.4,5031.3
XS Rating Curve= 0 ,0
Exp/Cntr=0.3,0.1

Type RM Length L Ch R = 1 ,58906   ,572,572,572
BEGIN DESCRIPTION:
SHOATS CREEK 76.0
END DESCRIPTION:
XS GIS Cut Line= 3
      2412975.01     13604574.99      2413348.94     13604054.63
      2413825.01     13603324.98
#Sta/Elev= 30
  4446.4  365.58  4599.4  360.77  4689.3  358.79  4776.6  356.71    4900  351.92
  4903.8  351.81  4939.9  350.44  4963.2  349.03  4975.9  347.54  4979.2  346.69
  4979.7  346.19  4988.6  346.19  4989.1  346.69  5008.3  346.93  5055.3  348.46
  5070.1  349.56  5090.9  349.96    5106  350.72  5214.7  352.46  5265.8  351.97
  5314.1  350.35  5350.4  349.69  5365.5  349.89  5489.2  354.08  5510.3   354.5
  5546.5  355.96  5733.6  361.04  5828.6  364.22  5832.3  364.31  5958.4  367.87
#Mann= 10 ,-1 , 0
  4446.4     .05       0  4599.4    .035       0  4689.3     .05       0
    4900     .07       0  4903.8     .12       0  4979.2     .05       0
  4989.1     .12       0  5008.3     .05       0  5828.6     .12       0
  5832.3    .035       0
Bank Sta=4979.2,4989.1
XS Rating Curve= 0 ,0
Exp/Cntr=0.3,0.1