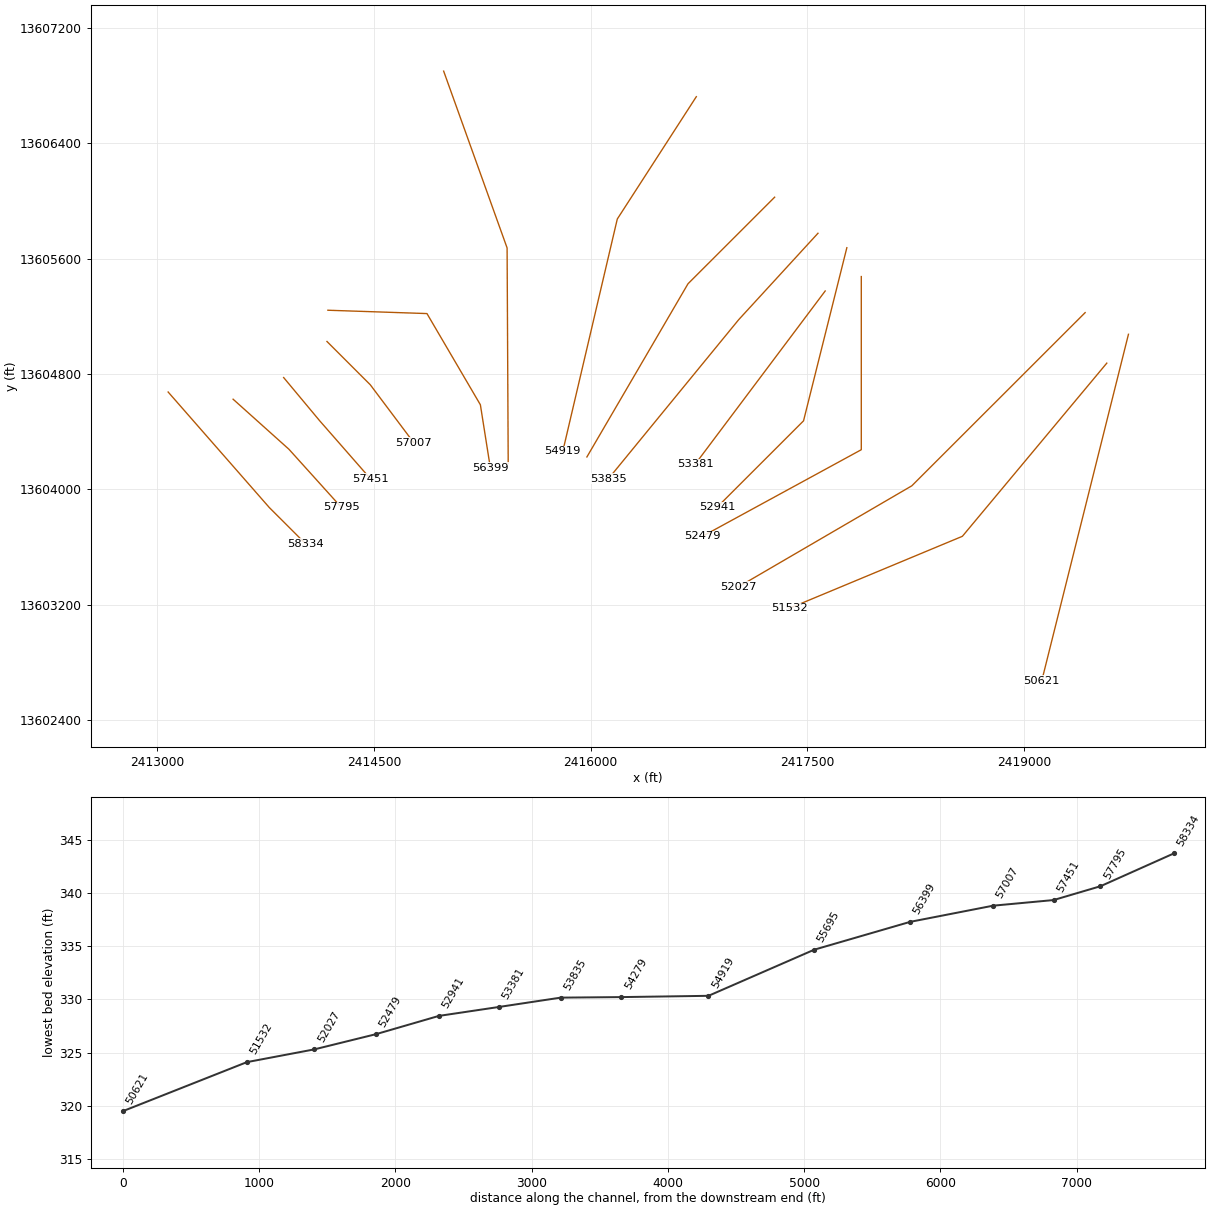
HEC-RAS study SHOATS CREEK.prj: SHOATS CREEK Base Level Engineering

--- SHOATS CREEK.g01 (geometry) --- (continued)

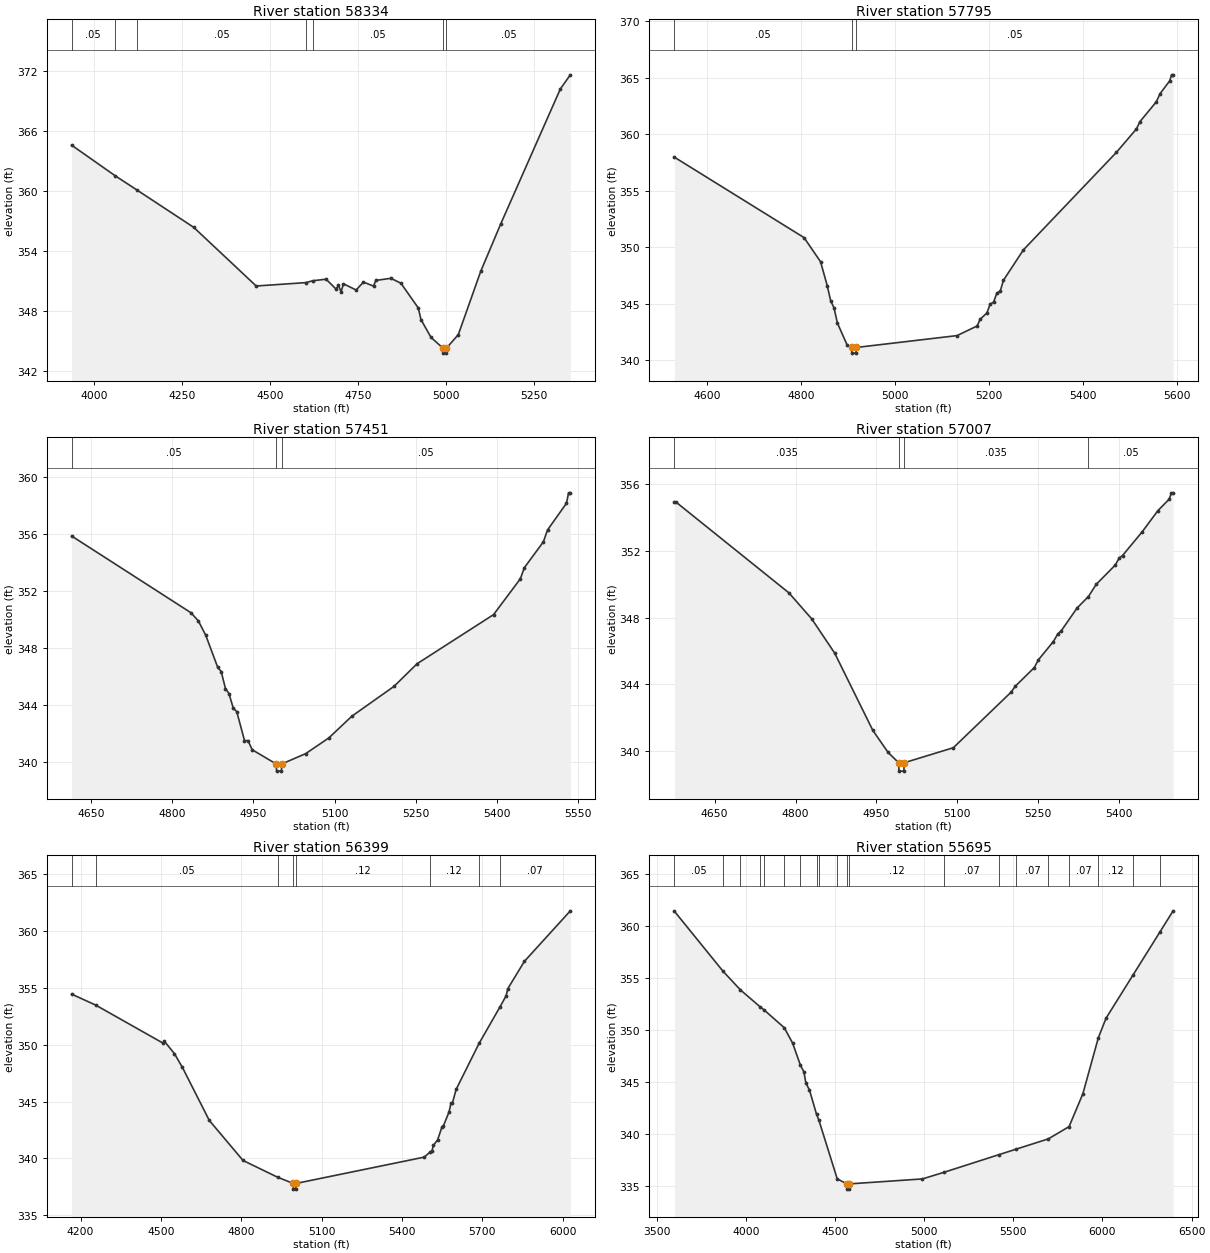
Type RM Length L Ch R = 1 ,58334   ,539,539,539
BEGIN DESCRIPTION:
SHOATS CREEK 75.0
END DESCRIPTION:
XS GIS Cut Line= 3
      2413075.03     13604674.97        2413775.       13603875.
      2414024.98     13603625.02
#Sta/Elev= 30
  3936.3  364.56  4059.5  361.51  4121.9  360.07  4283.2  356.33  4460.6  350.46
  4601.9   350.8  4622.1  350.99    4659  351.14  4687.5  350.15  4694.1  350.53
  4701.7  349.88  4708.4  350.68  4744.4  350.06  4765.3  350.85  4793.8  350.45
  4800.4  351.02  4843.1  351.23  4871.6  350.74    4921  348.26  4928.6   347.1
    4957  345.32    4991  344.24  4991.5  343.74  5000.4  343.74  5000.9  344.24
  5034.6  345.59  5098.3  351.93  5154.8  356.65  5324.5  370.19  5352.8   371.6
#Mann= 7 ,-1 , 0
  3936.3     .05       0  4059.5    .035       0  4121.9     .05       0
  4601.9     .12       0  4622.1     .05       0    4991     .05       0
  5000.9     .05       0
Bank Sta=4991,5000.9
XS Rating Curve= 0 ,0
Exp/Cntr=0.3,0.1

Type RM Length L Ch R = 1 ,57795   ,344,344,344
BEGIN DESCRIPTION:
SHOATS CREEK 74.0
END DESCRIPTION:
XS GIS Cut Line= 3
        2413525.       13604625.      2413911.59     13604278.15
      2414275.03     13603874.96
#Sta/Elev= 30
  4530.4  357.97  4806.6  350.86  4841.7  348.73    4856   346.6  4863.4  345.25
  4870.2  344.68  4877.6  343.31  4898.6  341.34  4907.8  341.15  4908.3  340.65
  4917.3  340.65  4917.8  341.15  5132.5   342.2  5175.1  343.05  5181.9  343.66
  5196.1   344.2  5202.8  344.98  5210.3  345.16    5217  345.94  5224.5  346.14
  5231.2  347.09  5273.8  349.78  5471.9   358.4  5514.5  360.47  5521.9  361.11
  5557.1  362.88  5564.5  363.57  5585.5  364.73  5589.2  365.25  5592.6  365.25
#Mann= 3 ,-1 , 0
  4530.4     .05       0  4907.8     .05       0  4917.8     .05       0
Bank Sta=4907.8,4917.8
XS Rating Curve= 0 ,0
Exp/Cntr=0.3,0.1

Type RM Length L Ch R = 1 ,57451   ,444,444,444
BEGIN DESCRIPTION:
SHOATS CREEK 73.0
END DESCRIPTION:
XS GIS Cut Line= 3
      2413874.99     13604775.01        2414125.       13604475.
      2414474.98     13604075.02
#Sta/Elev= 30
  4613.9  355.86  4834.6  350.47  4848.2   349.9  4861.9  348.89    4884  346.64
  4890.5  346.34  4898.3  345.15  4904.8   344.8  4912.7  343.78  4919.2  343.53
  4933.5   341.5    4940  341.49  4947.8  340.85  4992.3  339.85  4992.8  339.35
  5001.8  339.35  5002.3  339.85  5046.7  340.58  5089.4  341.68  5132.1  343.21
  5209.9   345.3  5252.6  346.89    5394  350.34  5443.4  352.85    5451  353.64
  5486.1  355.45  5493.7  356.28  5528.8  358.16  5532.6  358.89  5535.9  358.89
#Mann= 3 ,-1 , 0
  4613.9     .05       0  4992.3     .05       0  5002.3     .05       0
Bank Sta=4992.3,5002.3
XS Rating Curve= 0 ,0
Exp/Cntr=0.3,0.1

Type RM Length L Ch R = 1 ,57007   ,608,608,608
BEGIN DESCRIPTION:
SHOATS CREEK 72.0
END DESCRIPTION:
XS GIS Cut Line= 3
      2414174.98     13605025.02        2414475.       13604725.
      2414775.01     13604324.99
#Sta/Elev= 30
  4575.5  354.89  4579.1  354.89  4787.7  349.48  4830.1  347.92  4872.5  345.88
  4943.2  341.26  4971.5  339.94  4991.2  339.32  4991.7  338.82  5000.8  338.82
  5001.3  339.32  5092.5  340.22  5199.8  343.55  5207.1  343.89  5242.5  345.01
  5249.8  345.46  5277.9  346.57  5286.2  347.03  5292.5  347.21  5321.7  348.57
  5342.9  349.26  5357.1  349.98  5392.5  351.14  5399.8  351.56    5406  351.71
  5442.5  353.13  5471.7   354.4  5492.5  355.08  5496.7  355.46  5499.8  355.46
#Mann= 4 ,-1 , 0
  4575.5    .035       0  4991.2    .035       0  5001.3    .035       0
  5342.9     .05       0
Bank Sta=4991.2,5001.3
XS Rating Curve= 0 ,0
Exp/Cntr=0.3,0.1

Type RM Length L Ch R = 1 ,56399   ,704,704,704
BEGIN DESCRIPTION:
E20815
END DESCRIPTION:
XS GIS Cut Line= 4
      2414181.34     13605241.59      2414867.33     13605218.47
      2415237.29     13604586.45      2415306.43      13604148.6
#Sta/Elev= 30
  4166.6  354.44  4256.2  353.48  4508.1  350.13  4513.1  350.29  4550.5  349.21
  4580.5  347.99  4680.6  343.34  4806.6  339.82  4935.4  338.35  4994.2   337.8
  4994.7   337.3  5003.9   337.3  5004.4   337.8  5482.7  340.11  5503.3  340.52
  5511.6  340.64  5517.5  341.15  5533.1  341.63  5548.8  342.73  5554.6  342.85
    5576   344.1  5583.3  344.89  5588.6  344.89  5602.3  346.07  5687.7   350.1
  5766.5  353.34  5789.3  354.31  5794.7   354.9  5857.1  357.32  6028.6  361.76
#Mann= 8 ,-1 , 0
  4166.6    .035       0  4256.2     .05       0  4935.4     .12       0
  4994.2     .05       0  5004.4     .12       0  5503.3     .12       0
  5687.7     .05       0  5766.5     .07       0
Bank Sta=4994.2,5004.4
XS Rating Curve= 0 ,0
Exp/Cntr=0.3,0.1

Type RM Length L Ch R = 1 ,55695   ,776,776,776
BEGIN DESCRIPTION:
SHOATS CREEK 71.0
END DESCRIPTION:
XS GIS Cut Line= 3
      2414982.95     13606898.71      2415422.28     13605673.22
      2415429.98       13604179.
#Sta/Elev= 30
    3600   361.4  3873.7  355.61  3970.1  353.84  4079.8  352.22  4102.2  351.92
  4216.1   350.2  4262.6  348.73  4305.7  346.64  4326.3  345.94  4337.2  344.88
  4357.3  344.21  4396.8  341.88  4409.3  341.35  4512.9  335.67  4567.4  335.18
  4567.9  334.68  4577.2  334.68  4577.7  335.18  4990.1  335.66  5111.9   336.3
  5418.6  337.99  5517.1  338.53  5696.3  339.51  5812.7  340.69  5890.1  343.85
  5976.6  349.22  6020.1  351.12  6172.4   355.3  6323.3  359.44  6396.1  361.44
#Mann= 20 ,-1 , 0
    3600     .05       0  3873.7    .035       0  3970.1     .05       0
  4079.8     .12       0  4102.2     .07       0  4216.1     .12       0
  4305.7     .07       0  4396.8     .12       0  4409.3     .07       0
  4512.9     .12       0  4567.4     .05       0  4577.7     .12       0
  5111.9     .07       0  5418.6    .035       0  5517.1     .07       0
  5696.3    .035       0  5812.7     .07       0  5976.6     .12       0
  6172.4     .07       0  6323.3     .12       0
Bank Sta=4567.4,4577.7
XS Rating Curve= 0 ,0
Exp/Cntr=0.3,0.1

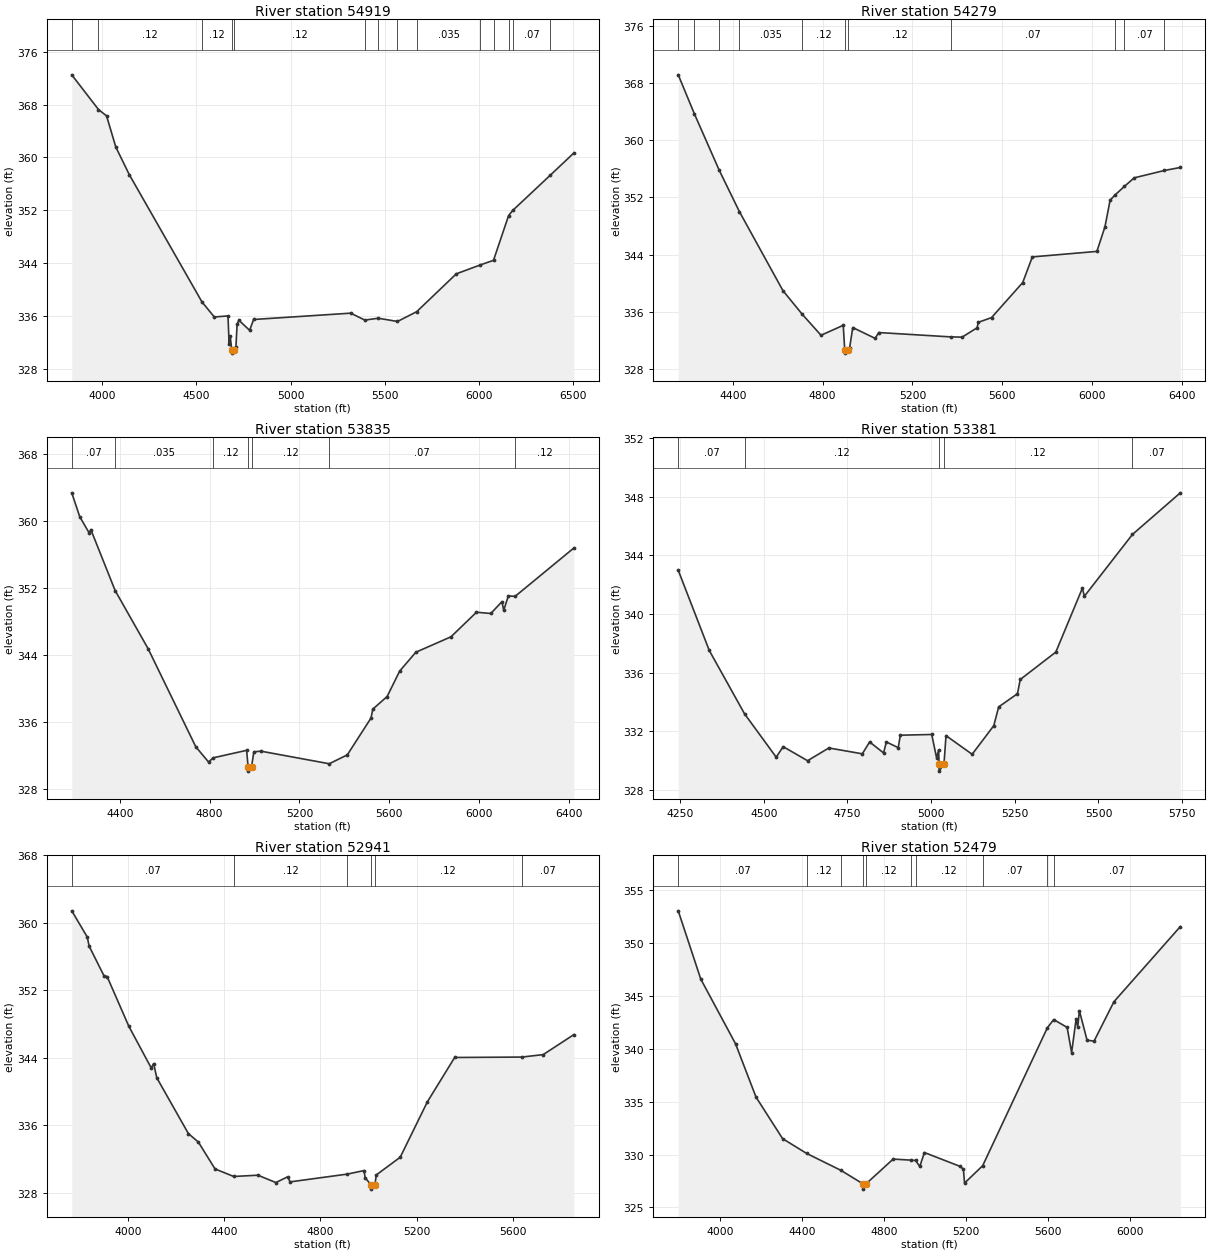
Type RM Length L Ch R = 1 ,54919   ,640,640,640
BEGIN DESCRIPTION:
SHOATS CREEK 70.0
END DESCRIPTION:
XS GIS Cut Line= 3
      2416732.57     13606721.46      2416185.32     13605873.61
      2415807.65     13604262.71
#Sta/Elev= 30
  3838.3  372.53    3980  367.27    4023   366.3  4072.1  361.57  4143.8  357.38
  4529.3  338.09  4594.5  335.82  4667.1  335.98    4673  331.79  4679.1  332.94
  4686.6  330.84  4687.1  330.34  4701.6  330.84  4709.3  331.28  4715.3  334.68
  4724.5  335.33  4781.9   333.8    4803  335.44  5318.5   336.4  5392.9  335.35
  5464.4  335.63  5566.3  335.14  5668.2  336.62  5878.3  342.36  6006.6  343.72
  6075.8  344.41  6155.8  351.19  6177.7  351.97  6376.8  357.31    6502  360.68
#Mann= 14 ,-1 , 0
  3838.3     .07       0    3980     .12       0  4529.3     .12       0
  4686.6     .05       0  4701.6     .12       0  5392.9     .07       0
  5464.4     .12       0  5566.3     .07       0  5668.2    .035       0
  6006.6     .07       0  6075.8     .12       0  6155.8    .035       0
  6177.7     .07       0  6376.8     .12       0
Bank Sta=4686.6,4701.6
XS Rating Curve= 0 ,0
Exp/Cntr=0.3,0.1

Type RM Length L Ch R = 1 ,54279   ,444,444,444
BEGIN DESCRIPTION:
SHOATS CREEK 69.0
END DESCRIPTION:
XS GIS Cut Line= 3
      2417274.99     13606024.99        2416675.       13605425.
      2415974.98     13604224.96
#Sta/Elev= 30
  4156.3  369.15  4227.9  363.72    4339   355.8  4428.7  350.03    4623  338.96
  4708.6  335.67  4792.7  332.72  4891.7  334.11  4898.3  330.72  4898.8  330.22
  4913.4  330.72    4920  330.92  4934.1   333.8  5034.2  332.28  5049.9   333.1
  5371.3  332.49  5421.6  332.46  5488.2  333.76  5493.9  334.53  5552.7  335.19
  5691.6  340.09  5734.6  343.68  6022.3  344.45  6058.3   347.9  6081.1   351.6
  6102.3  352.32  6144.4  353.53  6188.6  354.74  6323.4  355.77  6394.1  356.19
#Mann= 11 ,-1 , 0
  4156.3     .07       0  4227.9     .12       0    4339     .07       0
  4428.7    .035       0  4708.6     .12       0  4898.3     .05       0
  4913.4     .12       0  5371.3     .07       0  6102.3     .12       0
  6144.4     .07       0  6323.4     .12       0
Bank Sta=4898.3,4913.4
XS Rating Curve= 0 ,0
Exp/Cntr=0.3,0.1

Type RM Length L Ch R = 1 ,53835   ,454,454,454
BEGIN DESCRIPTION:
SHOATS CREEK 68.0
END DESCRIPTION:
XS GIS Cut Line= 3
      2417575.01     13605775.01        2417025.       13605175.
      2416125.01     13604075.02
#Sta/Elev= 30
  4186.3  363.36  4221.8  360.51  4264.3  358.55  4271.1  358.98  4379.5   351.7
  4525.8  344.79  4738.5  333.07  4795.2  331.26  4816.4  331.76  4964.8  332.65
  4971.4  330.67  4971.9  330.17  4986.5  330.67  4996.9  332.47  5028.2  332.55
  5332.6  331.05    5413  332.11  5518.5   336.5  5526.4  337.56  5590.3  339.07
  5646.3  342.11  5718.1  344.35  5874.5  346.19    5988  349.12  6051.8  348.97
  6101.4  350.38  6109.3  349.36  6130.1  351.07  6159.9  351.01  6421.5  356.78
#Mann= 7 ,-1 , 0
  4186.3     .07       0  4379.5    .035       0  4816.4     .12       0
  4971.4     .05       0  4986.5     .12       0  5332.6     .07       0
  6159.9     .12       0
Bank Sta=4971.4,4986.5
XS Rating Curve= 0 ,0
Exp/Cntr=0.3,0.1

Type RM Length L Ch R = 1 ,53381   ,440,440,440
BEGIN DESCRIPTION:
SHOATS CREEK 67.0
END DESCRIPTION:
XS GIS Cut Line= 3
      2417624.98     13605374.98        2417175.       13604775.
      2416724.98     13604174.98
#Sta/Elev= 30
  4244.5  342.99  4337.2  337.52  4442.6   333.2  4537.2  330.24    4558  330.96
  4630.9     330  4694.5  330.87  4794.5  330.47  4816.3  331.28    4858  330.53
  4866.3  331.28  4901.8  330.89    4908  331.74  5001.8  331.79  5016.3   330.2
  5022.6  330.74  5023.4  329.79  5023.9  329.29  5038.5  329.79  5044.5  331.71
  5122.6  330.44  5187.2  332.39  5201.8  333.67    5258  334.57  5266.3  335.54
  5372.6  337.41  5451.8  341.76    5458  341.22  5601.4  345.43  5744.5  348.27
#Mann= 5 ,-1 , 0
  4244.5     .07       0  4442.6     .12       0  5023.4     .05       0
  5038.5     .12       0  5601.4     .07       0
Bank Sta=5023.4,5038.5
XS Rating Curve= 0 ,0
Exp/Cntr=0.3,0.1

Type RM Length L Ch R = 1 ,52941   ,462,462,462
BEGIN DESCRIPTION:
SHOATS CREEK 66.0
END DESCRIPTION:
XS GIS Cut Line= 3
      2417774.99     13605674.96        2417475.       13604475.
      2416875.02     13603875.02
#Sta/Elev= 30
  3767.7  361.43  3832.1  358.32  3839.8  357.25  3901.7  353.72  3914.5  353.64
  4004.7  347.75  4097.5  342.82  4107.8  343.32  4120.7  341.65  4252.1  335.03
  4293.4  334.03  4362.9  330.84  4440.3  329.95  4540.7   330.1  4615.5  329.23
  4664.4  329.91  4674.7  329.31  4912.1  330.23  4981.4  330.65  4986.6  329.79
  5011.2  328.95  5011.7  328.45  5026.3  328.95  5032.9  330.14  5131.9  332.23
    5245  338.81  5358.1  344.05    5637   344.1  5725.8  344.39  5853.1  346.76
#Mann= 6 ,-1 , 0
  3767.7     .07       0  4440.3     .12       0  4912.1     .12       0
  5011.2     .05       0  5026.3     .12       0    5637     .07       0
Bank Sta=5011.2,5026.3
XS Rating Curve= 0 ,0
Exp/Cntr=0.3,0.1

Type RM Length L Ch R = 1 ,52479   ,452,452,452
BEGIN DESCRIPTION:
SHOATS CREEK 65.0
END DESCRIPTION:
XS GIS Cut Line= 3
        2417875.       13605475.        2417875.       13604275.
        2416775.       13603675.
#Sta/Elev= 30
  3793.8  353.04  3903.8  346.59  4073.8  340.47  4173.8  335.43  4303.8   331.5
  4421.6   330.1  4588.2  328.51  4696.2  327.23  4696.7  326.73  4711.3  327.23
  4843.8  329.57  4931.1  329.47  4953.5  329.44  4973.8  328.87  4996.6  330.19
  5170.8  328.88    5187  328.62  5192.7   327.3  5281.4  328.95  5597.1  341.98
    5628  342.76  5693.9  342.02  5715.7  339.64  5737.5  342.77  5745.6  342.08
  5753.7   343.6  5791.2  340.81  5825.3  340.72  5922.6  344.45  6246.8  351.55
#Mann= 10 ,-1 , 0
  3793.8     .07       0  4421.6     .12       0  4588.2     .12       0
  4696.2     .05       0  4711.3     .12       0  4931.1     .12       0
  4953.5     .12       0  5281.4     .07       0  5597.1     .12       0
    5628     .07       0
Bank Sta=4696.2,4711.3
XS Rating Curve= 0 ,0
Exp/Cntr=0.3,0.1

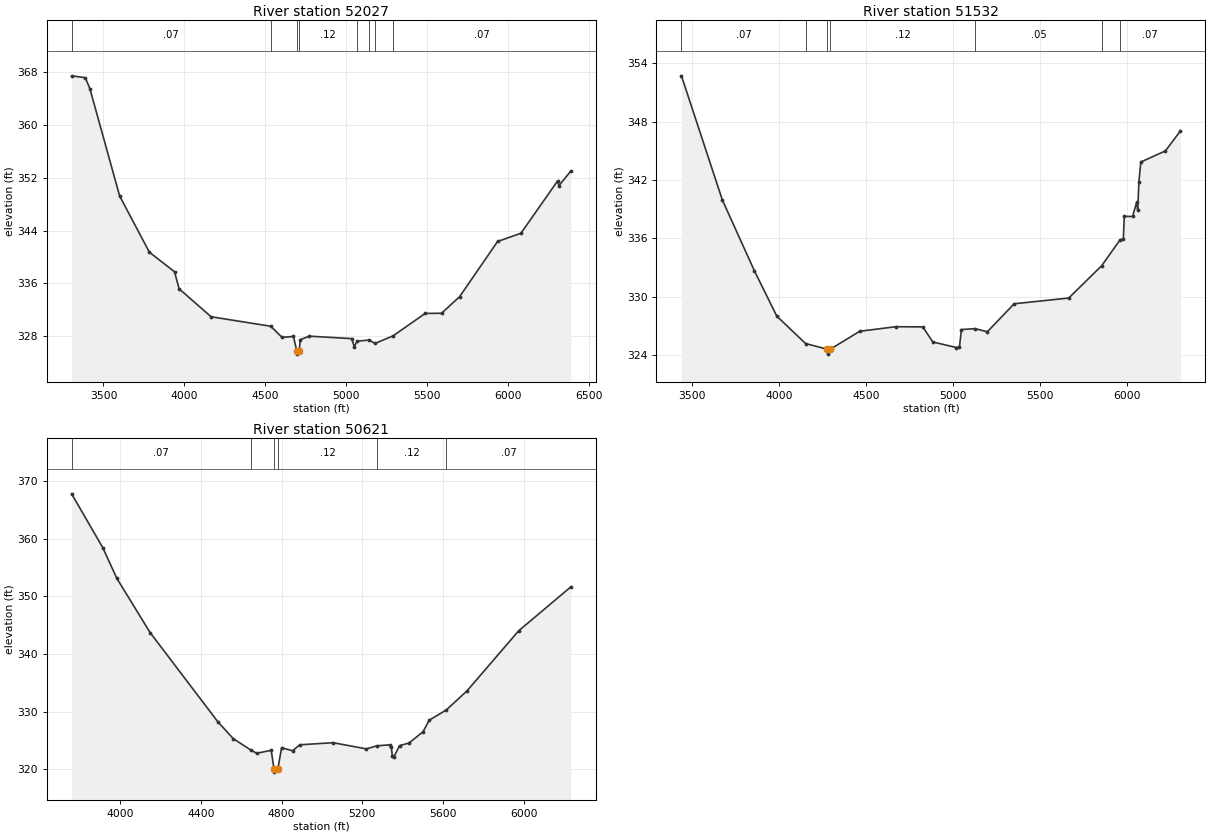
Type RM Length L Ch R = 1 ,52027   ,495,495,495
BEGIN DESCRIPTION:
SHOATS CREEK 64.0
END DESCRIPTION:
XS GIS Cut Line= 3
      2419425.03     13605225.03        2418225.       13604025.
      2417025.04     13603325.02
#Sta/Elev= 30
  3302.9  367.45  3387.8  367.16  3416.1  365.49  3599.9  349.25  3783.8  340.74
  3939.3  337.78  3967.6   335.2  4165.6  330.96  4534.8  329.52    4604  327.84
  4674.7  327.98  4695.4   325.8  4695.9   325.3  4710.7   325.8  4717.2   327.5
  4773.7  328.02  5035.1  327.65  5050.9  326.42  5067.4  327.26  5143.4  327.43
  5179.4  326.92  5291.4  328.07  5489.1  331.46  5590.8  331.49  5702.5     334
  5937.3  342.36    6082  343.61  6308.2  351.52  6316.9  350.82  6389.2     353
#Mann= 8 ,-1 , 0
  3302.9     .07       0  4534.8     .12       0  4695.4     .05       0
  4710.7     .12       0  5067.4    .035       0  5143.4     .07       0
  5179.4    .035       0  5291.4     .07       0
Bank Sta=4695.4,4710.7
XS Rating Curve= 0 ,0
Exp/Cntr=0.3,0.1

Type RM Length L Ch R = 1 ,51532   ,911,911,911
BEGIN DESCRIPTION:
SHOATS CREEK 63.0
END DESCRIPTION:
XS GIS Cut Line= 3
      2419575.02     13604875.03        2418575.       13603675.
      2417374.99       13603175.
#Sta/Elev= 30
    3442  352.73  3676.3  339.97  3860.5  332.67  3988.8  328.01  4153.9  325.19
  4279.5   324.6    4280   324.1  4295.4   324.6  4464.5  326.45  4670.2  326.92
  4826.4   326.9  4883.7  325.35  5018.7  324.78  5036.6  324.85    5048  326.63
  5126.3  326.72  5196.4   326.4  5350.2  329.28  5663.3  329.87  5852.5   333.2
  5957.9  335.86  5976.4  335.93  5981.8  338.27  6029.5  338.26  6053.3  339.75
  6058.7  338.91  6065.8  341.81  6076.6  343.86    6218  345.01  6304.1  347.07
#Mann= 7 ,-1 , 0
    3442     .07       0  4153.9     .12       0  4279.5     .05       0
  4295.4     .12       0  5126.3     .05       0  5852.5    .035       0
  5957.9     .07       0
Bank Sta=4279.5,4295.4
XS Rating Curve= 0 ,0
Exp/Cntr=0.3,0.1

Type RM Length L Ch R = 1 ,50621   ,442,442,442
BEGIN DESCRIPTION:
SHOATS CREEK 62.0
END DESCRIPTION:
XS GIS Cut Line= 3
        2419725.     13605075.02        2419425.       13603875.
        2419125.     13602674.98
#Sta/Elev= 30
  3758.9  367.81  3913.5  358.45  3983.1  353.13    4148  343.72    4483  328.26
  4560.3  325.29  4646.8  323.33  4676.3  322.75  4748.5  323.27  4762.4  319.98
  4762.9  319.48    4781  319.98    4800  323.72  4854.1  323.19  4890.2  324.23
  5055.1  324.59    5220  323.52  5273.1  324.05    5336  324.22  5343.7  323.86
  5348.9  322.32  5356.6  322.14    5385  324.09  5431.4  324.53  5500.9  326.49
  5531.9  328.51  5616.5  330.27    5720  333.63  5975.1  344.02  6232.8  351.62
#Mann= 6 ,-1 , 0
  3758.9     .07       0  4646.8     .12       0  4762.4     .05       0
    4781     .12       0  5273.1     .12       0  5616.5     .07       0
Bank Sta=4762.4,4781
XS Rating Curve= 0 ,0
Exp/Cntr=0.3,0.1