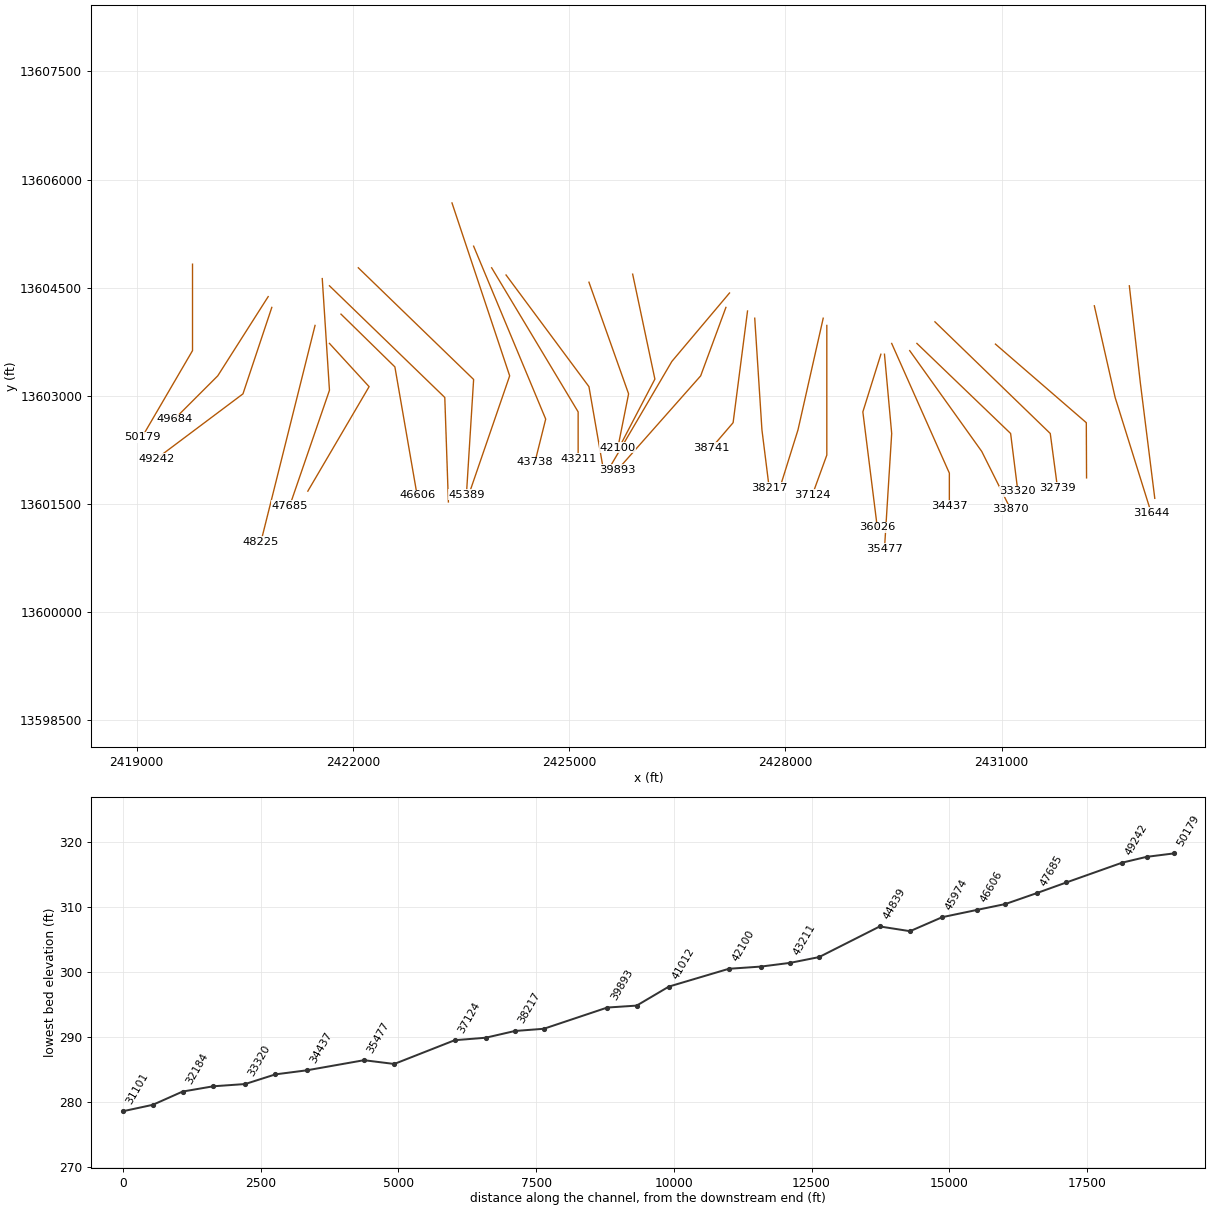
HEC-RAS study SHOATS CREEK.prj: SHOATS CREEK Base Level Engineering

--- SHOATS CREEK.g01 (geometry) --- (continued)

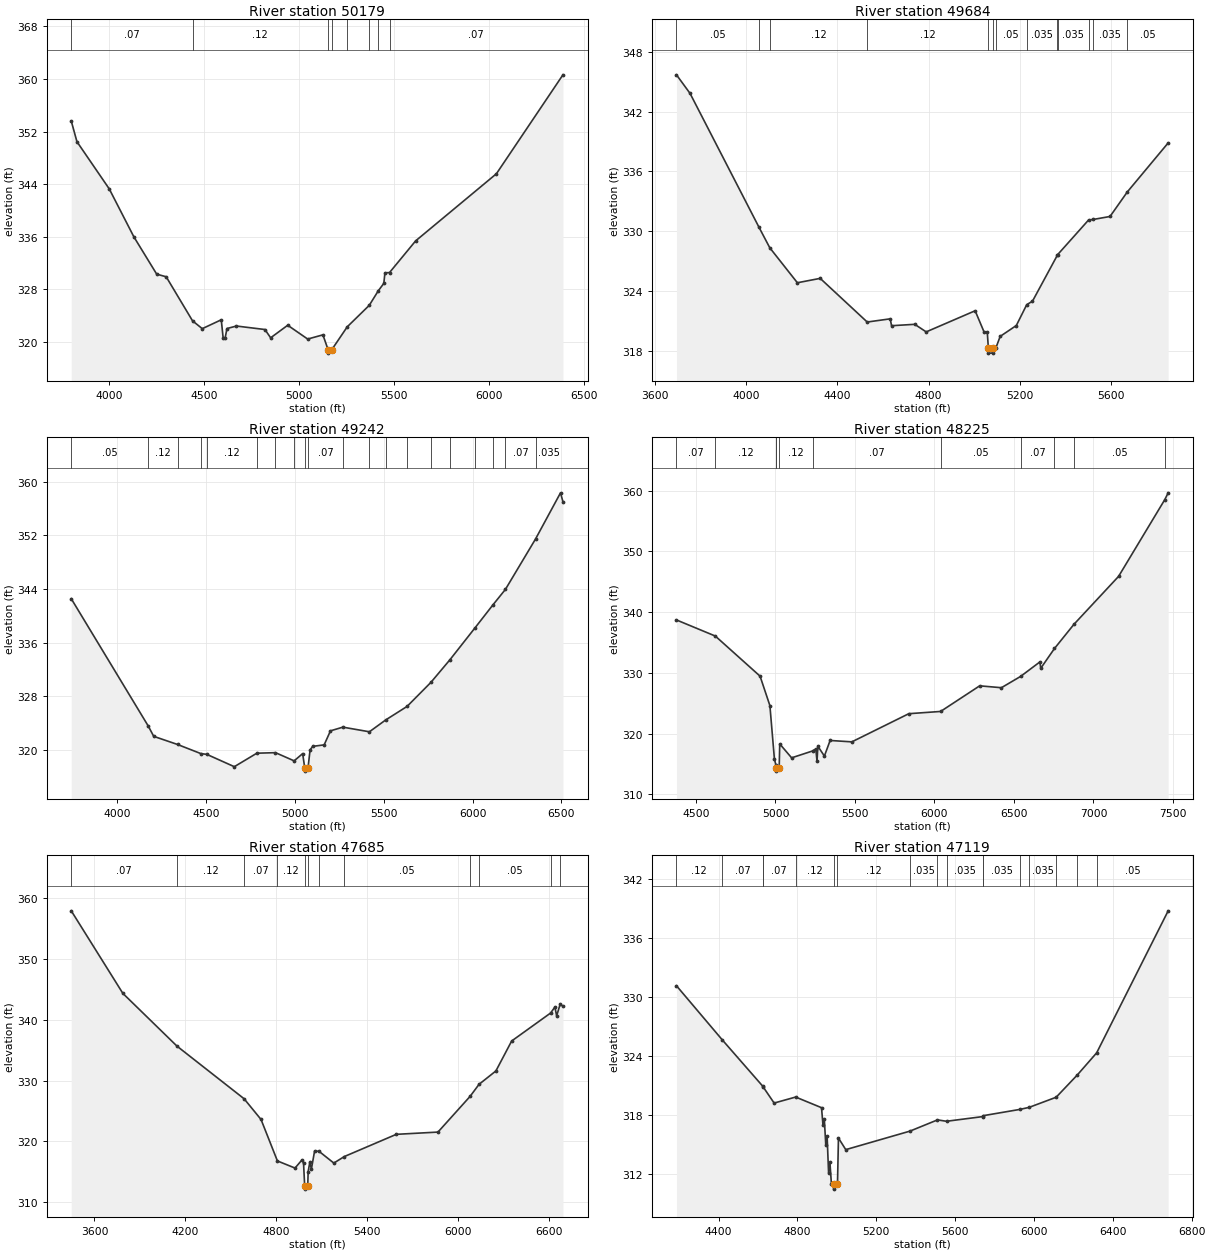
Type RM Length L Ch R = 1 ,50179   ,495,495,495
BEGIN DESCRIPTION:
SHOATS CREEK 61.0
END DESCRIPTION:
XS GIS Cut Line= 3
        2419775.     13604825.01        2419775.       13603625.
      2419074.98     13602424.96
#Sta/Elev= 30
    3800   353.6    3830  350.45    4000  343.28    4130  335.97    4250  330.31
    4300  329.91  4438.7  323.21    4490  322.02    4590  323.37    4600  320.58
    4610  320.54    4620  322.04    4670  322.42    4820  321.89    4850  320.63
    4940  322.54  5045.1  320.44  5125.3  321.08  5152.8   318.8  5153.3   318.3
  5171.4   318.8  5253.4   322.3  5369.4  325.57  5416.9  327.78  5446.1  328.91
  5451.9  330.51    5476  330.55  5613.6  335.37    6039  345.58  6389.3  360.62
#Mann= 8 ,-1 , 0
    3800     .07       0  4438.7     .12       0  5152.8     .05       0
  5171.4     .12       0  5253.4    .035       0  5369.4     .05       0
  5416.9     .12       0    5476     .07       0
Bank Sta=5152.8,5171.4
XS Rating Curve= 0 ,0
Exp/Cntr=0.3,0.1

Type RM Length L Ch R = 1 ,49684   ,442,442,442
BEGIN DESCRIPTION:
SHOATS CREEK 60.0
END DESCRIPTION:
XS GIS Cut Line= 3
      2420825.02     13604375.04        2420125.       13603275.
      2419525.01     13602675.01
#Sta/Elev= 30
  3696.1  345.69  3755.4  343.83  4057.7  330.38  4104.5  328.34  4225.3  324.83
  4325.2  325.27    4531  320.89  4631.7  321.21  4637.6  320.52  4739.2  320.66
  4789.2   319.9  5003.5  322.02  5042.4   319.9  5056.6  319.89  5061.4  318.27
  5061.9  317.77  5079.5  317.77    5080  318.27  5094.1  318.28  5113.1  319.45
  5183.8  320.54  5229.3  322.63  5254.5  322.98  5362.9  327.57  5364.6  327.65
  5499.8  331.12  5520.4  331.18    5594  331.48  5669.6  333.94  5848.5  338.86
#Mann= 13 ,-1 , 0
  3696.1     .05       0  4057.7     .07       0  4104.5     .12       0
    4531     .12       0  5061.4     .05       0    5080     .12       0
  5094.1     .05       0  5229.3    .035       0  5362.9     .05       0
  5364.6    .035       0  5499.8     .05       0  5520.4    .035       0
  5669.6     .05       0
Bank Sta=5061.4,5080
XS Rating Curve= 0 ,0
Exp/Cntr=0.3,0.1

Type RM Length L Ch R = 1 ,49242   ,1017,1017,1017
BEGIN DESCRIPTION:
SHOATS CREEK 59.0
END DESCRIPTION:
XS GIS Cut Line= 3
      2420874.99     13604224.97        2420475.       13603025.
      2419274.98     13602124.99
#Sta/Elev= 30
  3743.5  342.56  4176.2  323.61  4207.3  322.06  4341.1  320.85  4472.5  319.49
  4505.6  319.38  4660.5  317.54  4787.1  319.55    4892  319.63  4996.8  318.41
  5044.8  319.49  5056.3  317.38  5056.8  316.88    5075  317.38  5086.5  320.04
  5101.1  320.57  5165.7  320.79  5201.1  322.88  5270.9  323.43  5420.1  322.74
  5511.6   324.5    5632  326.52    5766   330.1  5872.7  333.46  6014.3  338.23
  6113.5   341.6    6185  343.95  6354.2  351.45  6494.8  358.33  6508.4     357
#Mann= 20 ,-1 , 0
  3743.5     .05       0  4176.2     .12       0  4341.1     .12       0
  4472.5     .12       0  4505.6     .12       0  4787.1     .12       0
    4892     .12       0  4996.8     .12       0  5056.3     .05       0
    5075     .07       0  5270.9    .035       0  5420.1     .07       0
  5511.6     .07       0    5632     .05       0    5766    .035       0
  5872.7    .035       0  6014.3    .035       0  6113.5     .05       0
    6185     .07       0  6354.2    .035       0
Bank Sta=5056.3,5075
XS Rating Curve= 0 ,0
Exp/Cntr=0.3,0.1

Type RM Length L Ch R = 1 ,48225   ,540,540,540
BEGIN DESCRIPTION:
SHOATS CREEK 58.0
END DESCRIPTION:
XS GIS Cut Line= 3
      2421474.99     13603974.96        2421325.       13603375.
        2420725.     13600974.99
#Sta/Elev= 30
  4377.4  338.72  4621.6  336.07  4903.1  329.46  4964.9  324.61  4993.3  315.82
  5002.2  314.87  5004.4  314.32  5004.9  313.82  5023.3  314.32  5026.8   318.3
  5101.5  316.01  5233.1  317.14  5253.5  317.48  5261.3  315.44  5266.4  317.93
  5307.6   316.3  5343.7  318.87  5480.3  318.64  5838.5  323.28  6038.6  323.65
  6284.3  327.87  6420.9  327.56  6541.6  329.42  6663.1  331.81  6668.3  330.76
  6754.7  334.02  6877.7  338.02  7157.9   345.9  7448.4  358.54  7469.7  359.66
#Mann= 11 ,-1 , 0
  4377.4     .07       0  4621.6     .12       0  5002.2     .12       0
  5004.4     .05       0  5023.3     .12       0  5233.1     .07       0
  6038.6     .05       0  6541.6     .07       0  6754.7    .035       0
  6877.7     .05       0  7448.4    .035       0
Bank Sta=5004.4,5023.3
XS Rating Curve= 0 ,0
Exp/Cntr=0.3,0.1

Type RM Length L Ch R = 1 ,47685   ,566,566,566
BEGIN DESCRIPTION:
SHOATS CREEK 57.0
END DESCRIPTION:
XS GIS Cut Line= 3
        2421575.     13604625.04        2421675.       13603075.
      2421124.99     13601474.96
#Sta/Elev= 30
  3446.7  357.88  3787.4  344.32  4144.9  335.65  4587.6  327.01  4699.3  323.61
  4807.4   316.8  4923.6  315.63  4969.9  316.98  4979.9  316.42  4987.4  312.67
  4987.9  312.17  5007.6  312.67  5010.3  315.06  5021.1  316.57  5031.7  315.47
  5052.8  318.43  5082.1  318.38  5179.7  316.45  5249.1  317.52  5592.1  321.17
  5867.1  321.54  6079.3  327.41    6138  329.38  6249.4  331.58  6353.5   336.5
  6610.2  341.09    6639  342.08  6650.3  340.63  6673.1   342.5  6691.9  342.24
#Mann= 12 ,-1 , 0
  3446.7     .07       0  4144.9     .12       0  4587.6     .07       0
  4807.4     .12       0  4987.4     .05       0  5007.6     .12       0
  5082.1     .07       0  5249.1     .05       0  6079.3    .035       0
    6138     .05       0  6610.2    .035       0  6673.1     .05       0
Bank Sta=4987.4,5007.6
XS Rating Curve= 0 ,0
Exp/Cntr=0.3,0.1

Type RM Length L Ch R = 1 ,47119   ,513,513,513
BEGIN DESCRIPTION:
SHOATS CREEK 56.0
END DESCRIPTION:
XS GIS Cut Line= 3
      2421675.01     13603724.99        2422225.       13603125.
        2421375.       13601675.
#Sta/Elev= 30
  4186.1  331.15    4417  325.69  4624.3  320.94  4624.8  320.91  4681.5  319.24
  4790.8  319.85    4922  318.77  4929.4  317.01  4936.2   317.6  4943.6  314.99
  4950.4  315.89  4957.8  312.16  4964.6  313.23    4972  311.06  4982.8     311
  4983.3   310.5    5003     311  5007.9  315.69    5045  314.51  5370.7  316.39
  5510.4  317.53  5556.1  317.39  5741.6  317.87  5742.8  317.96    5927  318.59
  5975.1   318.8  6112.4  319.83  6219.7  322.09    6318  324.34  6680.8  338.76
#Mann= 17 ,-1 , 0
  4186.1     .12       0    4417     .07       0  4624.3    .035       0
  4624.8     .07       0  4790.8     .12       0  4982.8     .05       0
    5003     .12       0  5370.7    .035       0  5510.4     .12       0
  5556.1    .035       0  5741.6     .07       0  5742.8    .035       0
    5927     .07       0  5975.1    .035       0  6112.4     .05       0
  6219.7     .12       0    6318     .05       0
Bank Sta=4982.8,5003
XS Rating Curve= 0 ,0
Exp/Cntr=0.3,0.1

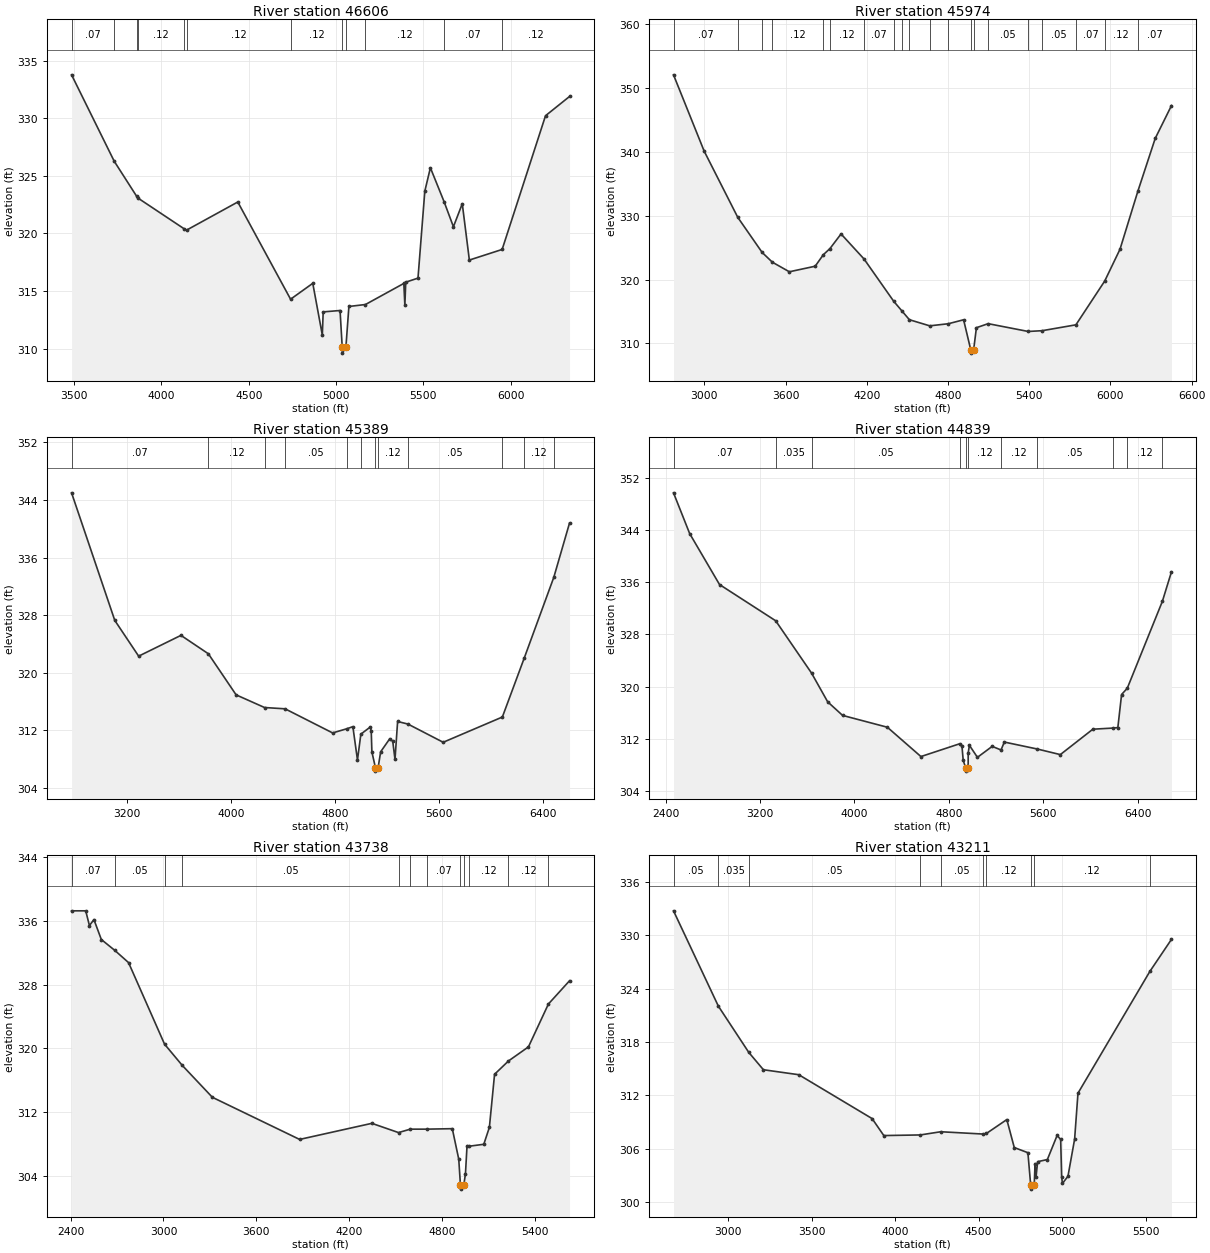
Type RM Length L Ch R = 1 ,46606   ,632,632,632
BEGIN DESCRIPTION:
E20814
END DESCRIPTION:
XS GIS Cut Line= 3
      2421834.96     13604131.71       2422582.6     13603399.49
      2422890.81     13601619.55
#Sta/Elev= 30
  3484.8  333.76  3729.1  326.26  3857.5  323.22  3863.3  323.08  4131.1  320.38
    4144  320.28  4437.1  322.72  4739.6  314.28  4866.7  315.66  4921.4  311.17
  4926.4  313.18    5023   313.3  5035.5   310.1    5036   309.6  5056.4   310.1
  5073.7  313.65  5168.5  313.82  5388.3  315.65  5394.3  313.75  5399.4  315.76
  5469.5  316.11  5508.7  323.67  5540.6  325.69  5618.9  322.75  5672.5  320.57
  5723.2  322.57  5763.8  317.68  5951.6   318.6  6200.2  330.21  6337.7  331.88
#Mann= 12 ,-1 , 0
  3484.8     .07       0  3729.1     .12       0  3857.5     .07       0
  3863.3     .12       0  4131.1     .07       0    4144     .12       0
  4739.6     .12       0  5035.5     .05       0  5056.4     .12       0
  5168.5     .12       0  5618.9     .07       0  5951.6     .12       0
Bank Sta=5035.5,5056.4
XS Rating Curve= 0 ,0
Exp/Cntr=0.3,0.1

Type RM Length L Ch R = 1 ,45974   ,585,585,585
BEGIN DESCRIPTION:
SHOATS CREEK 55.0
END DESCRIPTION:
XS GIS Cut Line= 3
      2421675.02     13604524.98        2423275.       13602975.
        2423325.       13601525.
#Sta/Elev= 30
  2772.4  352.03  2998.6   340.1    3247  329.73  3427.3  324.23  3502.6  322.71
  3628.1  321.21  3818.9  322.08  3879.1  323.88  3928.4  324.85    4010  327.13
  4179.4  323.22  4399.2  316.59    4463     315  4514.7  313.71    4665  312.75
  4802.6  313.08  4915.3   313.7  4968.4  308.98  4968.9  308.48  4989.3  308.98
    5010  312.46  5096.8  313.09  5392.5  311.87  5495.3  311.99    5745  312.91
  5957.7  319.76  6070.7  324.74  6203.1  333.85  6330.8  342.08  6450.9  347.22
#Mann= 20 ,-1 , 0
  2772.4     .07       0    3247     .12       0  3427.3     .07       0
  3502.6     .12       0  3879.1     .07       0  3928.4     .12       0
  4179.4     .07       0  4399.2     .12       0    4463     .07       0
  4514.7     .12       0    4665     .12       0  4802.6     .07       0
  4968.4     .05       0  4989.3     .12       0  5096.8     .05       0
  5392.5    .035       0  5495.3     .05       0    5745     .07       0
  5957.7     .12       0  6203.1     .07       0
Bank Sta=4968.4,4989.3
XS Rating Curve= 0 ,0
Exp/Cntr=0.3,0.1

Type RM Length L Ch R = 1 ,45389   ,550,550,550
BEGIN DESCRIPTION:
SHOATS CREEK 54.0
END DESCRIPTION:
XS GIS Cut Line= 3
      2422075.03     13604774.97        2423675.       13603225.
        2423575.     13601625.04
#Sta/Elev= 30
  2772.9     345  3105.3  327.27    3289   322.3  3614.4  325.19  3825.2  322.63
  4038.8  316.92  4257.6  315.16  4415.5  314.98  4781.2  311.63  4892.3  312.22
  4936.9   312.5  4972.3  307.87  4998.4  311.46  5070.7  312.45  5078.2   311.9
  5083.2  308.99  5110.3  306.82  5110.8  306.32  5131.2  306.82  5150.8  309.01
  5220.9  310.83  5243.5  310.48    5261  307.95  5281.1  313.22  5360.7  312.86
  5631.7  310.33  6086.9  313.84  6254.9  322.02  6482.5  333.25  6603.6   340.8
#Mann= 12 ,-1 , 0
  2772.9     .07       0  3825.2     .12       0  4257.6     .07       0
  4415.5     .05       0  4892.3     .07       0  4998.4     .12       0
  5110.3     .05       0  5131.2     .12       0  5360.7     .05       0
  6086.9     .07       0  6254.9     .12       0  6482.5     .07       0
Bank Sta=5110.3,5131.2
XS Rating Curve= 0 ,0
Exp/Cntr=0.3,0.1

Type RM Length L Ch R = 1 ,44839   ,1101,1101,1101
BEGIN DESCRIPTION:
SHOATS CREEK 53.0
END DESCRIPTION:
XS GIS Cut Line= 3
      2423375.01     13605674.96        2424175.       13603275.
      2423624.99     13601674.97
#Sta/Elev= 30
  2466.3  349.66  2603.3  343.42  2856.3  335.62  3332.5  330.07  3636.2  322.07
  3773.3  317.66  3899.8  315.58  4279.3  313.77  4563.9  309.28  4894.2  311.25
  4911.8  310.88  4922.3  308.69  4943.5  307.55    4944  307.05  4964.4  307.55
  4964.5  309.84    4975     311  5042.9  309.16  5167.9  310.84  5242.9  310.29
    5271   311.5  5551.7  310.43  5745.7  309.58  6021.5  313.47    6190  313.64
  6233.3  313.72    6265  318.78  6313.3  319.74  6610.9  333.05    6688  337.57
#Mann= 11 ,-1 , 0
  2466.3     .07       0  3332.5    .035       0  3636.2     .05       0
  4894.2     .12       0  4943.5     .05       0  4964.4     .12       0
  5242.9     .12       0  5551.7     .05       0    6190     .07       0
  6313.3     .12       0  6610.9     .07       0
Bank Sta=4943.5,4964.4
XS Rating Curve= 0 ,0
Exp/Cntr=0.3,0.1

Type RM Length L Ch R = 1 ,43738   ,527,527,527
BEGIN DESCRIPTION:
SHOATS CREEK 52.0
END DESCRIPTION:
XS GIS Cut Line= 3
        2423675.     13605074.99        2424675.       13602675.
      2424524.99     13602074.96
#Sta/Elev= 30
  2405.9  337.27  2497.4  337.27  2521.3  335.42  2550.5  336.17  2598.2  333.67
    2685  332.31  2774.2  330.77  3006.9  320.53  3121.1  317.87  3315.9  313.86
  3879.8  308.57  4346.7  310.59    4519  309.43  4595.6  309.86  4701.1  309.86
  4866.7  309.92  4908.4  306.09  4919.4  302.83  4919.9  302.33  4940.8  302.83
  4951.7  304.24    4962  307.79  4976.6  307.72  5070.3  307.96  5106.4  310.09
  5139.9  316.75  5229.8  318.42  5358.9  320.19  5487.9  325.57  5624.4  328.49
#Mann= 12 ,-1 , 0
  2405.9     .07       0    2685     .05       0  3006.9    .035       0
  3121.1     .05       0    4519    .035       0  4595.6     .05       0
  4701.1     .07       0  4919.4     .05       0  4940.8     .07       0
  4976.6     .12       0  5229.8     .12       0  5487.9     .07       0
Bank Sta=4919.4,4940.8
XS Rating Curve= 0 ,0
Exp/Cntr=0.3,0.1

Type RM Length L Ch R = 1 ,43211   ,529,529,529
BEGIN DESCRIPTION:
SHOATS CREEK 51.0
END DESCRIPTION:
XS GIS Cut Line= 3
      2423924.98     13604775.03        2425125.       13602775.
        2425125.     13602125.01
#Sta/Elev= 30
  2672.5  332.77  2941.1  322.04  3123.4  316.83  3210.9  314.88  3422.8  314.32
    3862  309.38    3932  307.47  4150.7  307.54  4273.2   307.9  4527.8  307.64
  4546.9  307.71  4668.7  309.27  4713.4  306.12    4795  305.54  4811.5  301.94
    4812  301.44    4833  301.94  4837.8  304.32  4843.6  302.78  4853.3  304.53
  4911.6  304.77  4969.9  307.48  4991.3  307.03  4997.1   302.8    5002  302.08
  5034.9  302.89  5074.9  307.08  5094.9  312.24  5525.5  325.95  5654.9  329.56
#Mann= 10 ,-1 , 0
  2672.5     .05       0  2941.1    .035       0  3123.4     .05       0
  4150.7    .035       0  4273.2     .05       0  4527.8     .07       0
  4546.9     .12       0  4811.5     .05       0    4833     .12       0
  5525.5     .07       0
Bank Sta=4811.5,4833
XS Rating Curve= 0 ,0
Exp/Cntr=0.3,0.1

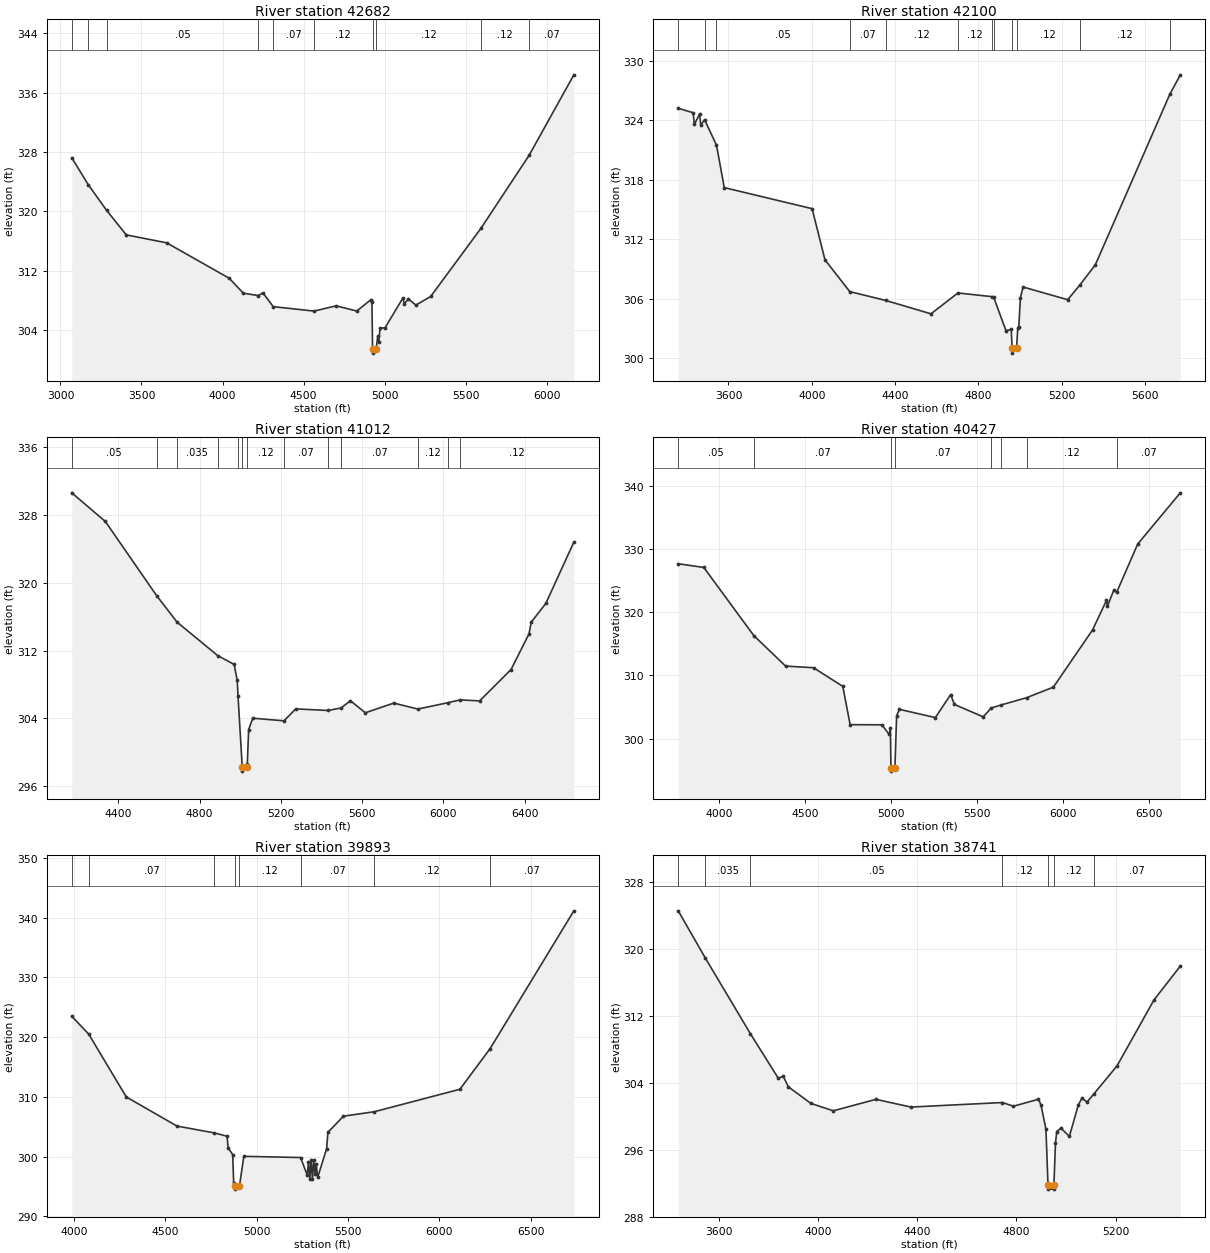
Type RM Length L Ch R = 1 ,42682   ,582,582,582
BEGIN DESCRIPTION:
SHOATS CREEK 50.0
END DESCRIPTION:
XS GIS Cut Line= 3
      2424124.99     13604675.01        2425275.       13603125.
        2425475.       13601975.
#Sta/Elev= 30
    3070  327.22  3171.3  323.61  3284.9  320.13  3406.2  316.82  3655.2  315.75
  4041.3  310.97  4128.4  308.95  4219.5  308.64    4250  308.99  4312.5  307.14
  4564.8  306.54  4700.7  307.25  4827.9  306.55  4913.4  308.04  4921.8  307.78
  4925.7  301.37  4926.2  300.87  4947.2  301.37  4957.3  303.13  4963.5  302.38
  4971.9  304.24  5002.6  304.28  5111.7  308.27  5121.8  307.55  5146.6  308.17
  5192.9  307.35  5284.2  308.51  5594.4  317.71  5891.3  327.55  6167.3  338.41
#Mann= 10 ,-1 , 0
    3070     .05       0  3171.3    .035       0  3284.9     .05       0
  4219.5    .035       0  4312.5     .07       0  4564.8     .12       0
  4925.7     .05       0  4947.2     .12       0  5594.4     .12       0
  5891.3     .07       0
Bank Sta=4925.7,4947.2
XS Rating Curve= 0 ,0
Exp/Cntr=0.3,0.1

Type RM Length L Ch R = 1 ,42100   ,1088,1088,1088
BEGIN DESCRIPTION:
SHOATS CREEK 49.0
END DESCRIPTION:
XS GIS Cut Line= 3
        2425275.       13604575.        2425825.       13603025.
      2425675.01     13602275.04
#Sta/Elev= 30
  3359.1  325.19    3431  324.74  3436.3  323.56  3461.8  324.61  3467.1  323.47
  3485.2  324.05  3542.7  321.48    3580   317.2  4001.5  315.08  4063.3  309.93
    4182  306.73  4353.9  305.84  4572.1  304.49  4701.5  306.59  4863.3  306.22
  4872.7  306.17  4931.9  302.79  4957.5  302.92  4961.2  301.03  4961.7  300.53
  4982.7  301.03  4988.4  303.03  4993.7  303.21  5001.1  306.11    5014  307.19
  5228.1  305.91  5287.6  307.42  5360.7  309.42  5717.8  326.58  5768.6  328.56
#Mann= 12 ,-1 , 0
  3359.1    .035       0  3485.2     .07       0  3542.7     .05       0
    4182     .07       0  4353.9     .12       0  4701.5     .12       0
  4863.3     .12       0  4872.7     .12       0  4961.2     .05       0
  4982.7     .12       0  5287.6     .12       0  5717.8     .07       0
Bank Sta=4961.2,4982.7
XS Rating Curve= 0 ,0
Exp/Cntr=0.3,0.1

Type RM Length L Ch R = 1 ,41012   ,585,585,585
BEGIN DESCRIPTION:
E20813
END DESCRIPTION:
XS GIS Cut Line= 3
      2425881.43     13604686.69      2426189.74     13603229.92
      2425735.25     13602359.46
#Sta/Elev= 30
    4171   330.6  4336.3  327.22  4588.9  318.47    4689  315.36  4889.2  311.41
    4970  310.37  4985.2  308.52  4989.3  306.62  5009.9  298.29  5010.4  297.79
  5032.3  298.29  5034.9  298.61  5041.6  302.69    5062  304.03  5215.6  303.72
  5273.2  305.13  5432.6  304.94  5496.6  305.24  5542.4  306.09    5616  304.67
  5755.8  305.81  5874.2  305.11  6020.9  305.85  6082.7  306.19  6178.4  306.07
    6333  309.77  6421.4  313.98  6432.2  315.35  6504.1  317.56    6642  324.79
#Mann= 13 ,-1 , 0
    4171     .05       0  4588.9     .07       0    4689    .035       0
  4889.2     .05       0  4989.3     .12       0  5009.9     .05       0
  5032.3     .12       0  5215.6     .07       0  5432.6     .12       0
  5496.6     .07       0  5874.2     .12       0  6020.9     .07       0
  6082.7     .12       0
Bank Sta=5009.9,5032.3
XS Rating Curve= 0 ,0
Exp/Cntr=0.3,0.1

Type RM Length L Ch R = 1 ,40427   ,534,534,534
BEGIN DESCRIPTION:
SHOATS CREEK 48.0
END DESCRIPTION:
XS GIS Cut Line= 3
      2427225.01     13604425.02        2426425.       13603475.
      2425574.98     13602024.97
#Sta/Elev= 30
  3762.1  327.67    3911  327.08  4201.8  316.31    4387  311.48  4549.6  311.22
    4720  308.27  4762.8  302.21  4947.5  302.19  4990.4  300.66  4996.9   301.7
  5000.3  295.36  5000.8  294.86  5023.5  295.36  5033.4  303.58  5049.1  304.64
  5259.1  303.33  5348.1  306.98  5369.6  305.41  5537.3  303.45  5585.1  304.86
  5638.2   305.3  5790.6  306.48  5946.1  308.15  6174.8  317.23    6255  321.87
  6260.8  320.97  6297.9   323.5  6314.4  323.15  6436.7  330.78  6684.9  338.89
#Mann= 8 ,-1 , 0
  3762.1     .05       0  4201.8     .07       0  5000.3     .05       0
  5023.5     .07       0  5585.1     .12       0  5638.2     .07       0
  5790.6     .12       0  6314.4     .07       0
Bank Sta=5000.3,5023.5
XS Rating Curve= 0 ,0
Exp/Cntr=0.3,0.1

Type RM Length L Ch R = 1 ,39893   ,1152,1152,1152
BEGIN DESCRIPTION:
SHOATS CREEK 47.0
END DESCRIPTION:
XS GIS Cut Line= 3
      2427175.01     13604225.03        2426825.       13603275.
      2425675.01     13601975.01
#Sta/Elev= 30
    3988  323.49  4080.7  320.51  4286.4  309.99  4563.5  305.12  4766.4  303.98
  4838.3  303.41  4843.6  301.48  4868.8  300.35  4874.1   295.6    4882  295.06
  4882.5  294.56  4905.8  295.06  4929.7  300.05  5240.3  299.85  5276.9   296.9
  5283.6  299.12  5291.1  296.27  5297.8  299.37  5305.4  296.27    5312  299.45
  5319.6  297.08  5326.3  298.71  5333.8  296.52  5383.1  301.33  5389.8  304.06
  5475.2  306.77  5644.2  307.52  6112.5  311.28  6278.2   318.1  6736.1  341.15
#Mann= 8 ,-1 , 0
    3988     .05       0  4080.7     .07       0  4766.4     .12       0
    4882     .05       0  4905.8     .12       0  5240.3     .07       0
  5644.2     .12       0  6278.2     .07       0
Bank Sta=4882,4905.8
XS Rating Curve= 0 ,0
Exp/Cntr=0.3,0.1

Type RM Length L Ch R = 1 ,38741   ,524,524,524
BEGIN DESCRIPTION:
SHOATS CREEK 46.0
END DESCRIPTION:
XS GIS Cut Line= 3
        2427475.       13604175.        2427275.       13602625.
      2426975.02     13602275.02
#Sta/Elev= 30
  3436.9  324.52  3546.6  318.86  3727.5  309.86  3840.2  304.53  3860.4  304.76
  3880.6  303.51  3971.3  301.53    4062  300.64  4233.5  302.01  4374.6  301.09
  4743.9  301.63    4788  301.19  4888.8  302.02  4898.9  301.37  4919.1  298.44
  4927.4  291.79  4927.9  291.29  4950.7  291.29  4951.2  291.79  4957.5  296.79
  4962.6  298.17  4979.6  298.58  5013.5  297.58  5049.7  301.35    5064  302.14
  5084.8  301.69    5112  302.65  5205.5     306  5354.8  313.89  5460.7  317.92
#Mann= 7 ,-1 , 0
  3436.9     .05       0  3546.6    .035       0  3727.5     .05       0
  4743.9     .12       0  4927.4     .05       0  4951.2     .12       0
    5112     .07       0
Bank Sta=4927.4,4951.2
XS Rating Curve= 0 ,0
Exp/Cntr=0.3,0.1

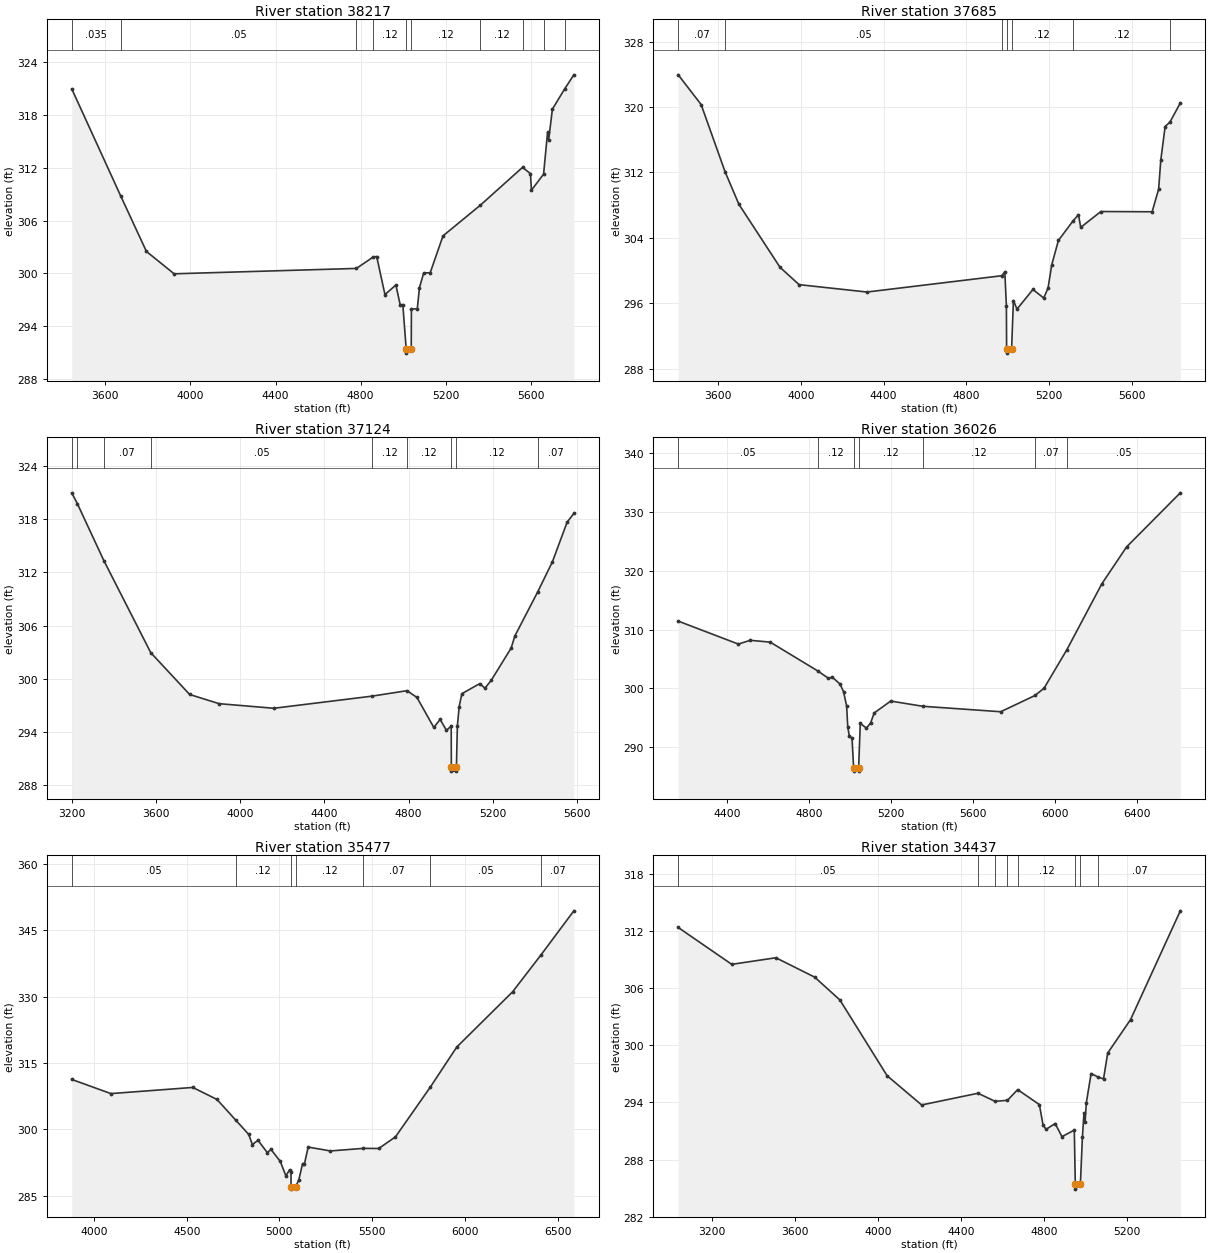
Type RM Length L Ch R = 1 ,38217   ,532,532,532
BEGIN DESCRIPTION:
SHOATS CREEK 45.0
END DESCRIPTION:
XS GIS Cut Line= 3
        2427575.     13604075.04        2427675.       13602525.
        2427775.     13601724.98
#Sta/Elev= 30
  3442.5  320.96  3672.7  308.79  3793.3   302.5  3923.5  299.96  4780.2  300.57
  4858.6  301.86  4875.5  301.92  4914.3   297.6  4965.7  298.69  4985.7  296.45
  4998.3  296.46    5014  291.45  5014.5  290.95  5037.9  291.45  5038.6  295.95
  5066.3  295.99  5076.4  298.38  5096.5  300.07  5126.8  300.07  5187.2  304.27
    5363  307.76  5560.9  312.05  5597.9  311.34  5602.9  309.46  5659.8  311.28
  5678.5  316.03  5683.6  315.16  5701.2  318.66  5758.8  320.96    5802  322.56
#Mann= 10 ,-1 , 0
  3442.5    .035       0  3672.7     .05       0  4780.2     .12       0
  4858.6     .12       0    5014     .05       0  5037.9     .12       0
    5363     .12       0  5560.9     .07       0  5659.8     .12       0
  5758.8     .07       0
Bank Sta=5014,5037.9
XS Rating Curve= 0 ,0
Exp/Cntr=0.3,0.1

Type RM Length L Ch R = 1 ,37685   ,561,561,561
BEGIN DESCRIPTION:
SHOATS CREEK 44.0
END DESCRIPTION:
XS GIS Cut Line= 3
        2428525.     13604074.99        2428175.       13602525.
      2427924.99     13601724.97
#Sta/Elev= 30
  3407.3  323.93  3517.9   320.3  3633.7  312.08  3700.9  308.09  3899.4   300.4
  3991.6  298.28  4319.7  297.38    4971  299.37  4986.1  299.84  4993.7   295.7
  4994.8  290.41  4995.3  289.91  5018.8  290.41  5027.7  296.34    5045  295.29
    5122  297.69  5174.4  296.64  5195.4   297.9  5212.7  300.68  5245.1  303.68
  5315.8  306.07  5342.1  306.82  5353.1  305.28  5450.5  307.22  5698.3  307.19
  5729.7  309.95  5740.2  313.52  5761.1  317.61  5784.4  318.15  5834.5  320.49
#Mann= 7 ,-1 , 0
  3407.3     .07       0  3633.7     .05       0    4971     .12       0
  4994.8     .05       0  5018.8     .12       0  5315.8     .12       0
  5784.4     .07       0
Bank Sta=4994.8,5018.8
XS Rating Curve= 0 ,0
Exp/Cntr=0.3,0.1

Type RM Length L Ch R = 1 ,37124   ,1098,1098,1098
BEGIN DESCRIPTION:
SHOATS CREEK 43.0
END DESCRIPTION:
XS GIS Cut Line= 3
        2428575.     13603974.96        2428575.       13602175.
        2428375.       13601625.
#Sta/Elev= 30
  3199.6  321.01  3226.6  319.76  3351.9  313.35  3574.9  302.93  3759.6   298.2
  3899.6  297.16  4159.6  296.64  4625.6  298.01  4792.3  298.63  4839.6  297.86
  4919.6  294.47  4949.6  295.38  4979.6  294.14  5002.2  294.63  5002.9  290.03
  5003.4  289.53  5026.4  289.53  5026.9  290.03  5031.5  294.66  5040.1  296.82
  5052.8  298.29  5137.9  299.43  5162.5  298.91  5193.1  299.83  5286.9  303.45
  5304.8  304.83  5412.4  309.77    5483  313.21  5552.9  317.69  5584.8  318.68
#Mann= 9 ,-1 , 0
  3199.6     .07       0  3226.6     .05       0  3351.9     .07       0
  3574.9     .05       0  4625.6     .12       0  4792.3     .12       0
  5002.9     .05       0  5026.9     .12       0  5412.4     .07       0
Bank Sta=5002.9,5026.9
XS Rating Curve= 0 ,0
Exp/Cntr=0.3,0.1

Type RM Length L Ch R = 1 ,36026   ,549,549,549
BEGIN DESCRIPTION:
SHOATS CREEK 42.0
END DESCRIPTION:
XS GIS Cut Line= 3
      2429324.99     13603574.95        2429075.       13602775.
      2429275.01     13601174.96
#Sta/Elev= 30
  4162.2  311.43  4455.5  307.52  4513.7  308.16  4611.1  307.85  4843.3  302.94
  4895.5  301.68  4913.9  301.88  4951.6  300.72  4968.9  299.43  4984.1  296.97
  4989.8  293.33  4997.7  291.79  5010.4  291.53  5018.4  286.37  5018.9  285.87
  5042.2  285.87  5042.7  286.37  5050.7  294.01  5080.9  293.19  5101.1  294.08
  5118.7  295.78  5199.3  297.81  5355.5  296.92    5736  295.99  5903.6  298.76
  5947.6  299.99  6059.6  306.59  6229.8  317.79  6350.7  324.08  6612.8  333.29
#Mann= 7 ,-1 , 0
  4162.2     .05       0  4843.3     .12       0  5018.4     .05       0
  5042.7     .12       0  5355.5     .12       0  5903.6     .07       0
  6059.6     .05       0
Bank Sta=5018.4,5042.7
XS Rating Curve= 0 ,0
Exp/Cntr=0.3,0.1

Type RM Length L Ch R = 1 ,35477   ,1040,1040,1040
BEGIN DESCRIPTION:
SHOATS CREEK 41.0
END DESCRIPTION:
XS GIS Cut Line= 3
        2429375.     13603575.04        2429475.       13602475.
        2429375.     13600874.99
#Sta/Elev= 30
  3880.1  311.26    4091  308.06  4532.8  309.45  4663.4  306.73  4764.1  302.07
  4834.1  298.84  4854.1  296.53  4884.3   297.5  4934.5  294.72  4954.5  295.43
  5004.7  292.72  5034.8  289.45  5054.8  290.83  5062.3  290.36  5062.7  286.95
  5063.2  286.45    5087  286.95  5104.9  288.59  5124.9  292.24    5135  292.17
    5155  295.96  5275.2  295.09  5452.7  295.67  5535.7  295.64  5625.9  298.28
  5814.1  309.55  5956.6   318.6  6257.2  331.07  6410.5  339.42  6587.8   349.4
#Mann= 7 ,-1 , 0
  3880.1     .05       0  4764.1     .12       0  5062.7     .05       0
    5087     .12       0  5452.7     .07       0  5814.1     .05       0
  6410.5     .07       0
Bank Sta=5062.7,5087
XS Rating Curve= 0 ,0
Exp/Cntr=0.3,0.1

Type RM Length L Ch R = 1 ,34437   ,567,567,567
BEGIN DESCRIPTION:
SHOATS CREEK 40.0
END DESCRIPTION:
XS GIS Cut Line= 3
        2429475.     13603724.99        2430275.       13601925.
        2430275.     13601474.97
#Sta/Elev= 30
  3036.3  312.37  3294.1   308.5  3506.9  309.19  3693.6  307.16  3815.3  304.76
  4043.1   296.8  4209.3  293.73  4481.2  294.96  4563.4  294.11    4623  294.22
  4672.1  295.34  4776.9  293.77  4794.7  291.61  4809.1  291.17  4852.9  291.78
  4885.7   290.4  4945.2  291.09    4950  285.39  4950.5  284.89  4974.5  285.39
  4984.2  290.34  4991.7  292.85  4997.2  291.98  5003.3  293.98  5026.1  297.03
  5061.3  296.65  5086.1  296.47  5106.1  299.18  5216.1  302.69  5456.1  314.12
#Mann= 8 ,-1 , 0
  3036.3     .05       0  4481.2     .12       0  4563.4     .12       0
    4623     .05       0  4672.1     .12       0    4950     .05       0
  4974.5     .12       0  5061.3     .07       0
Bank Sta=4950,4974.5
XS Rating Curve= 0 ,0
Exp/Cntr=0.3,0.1

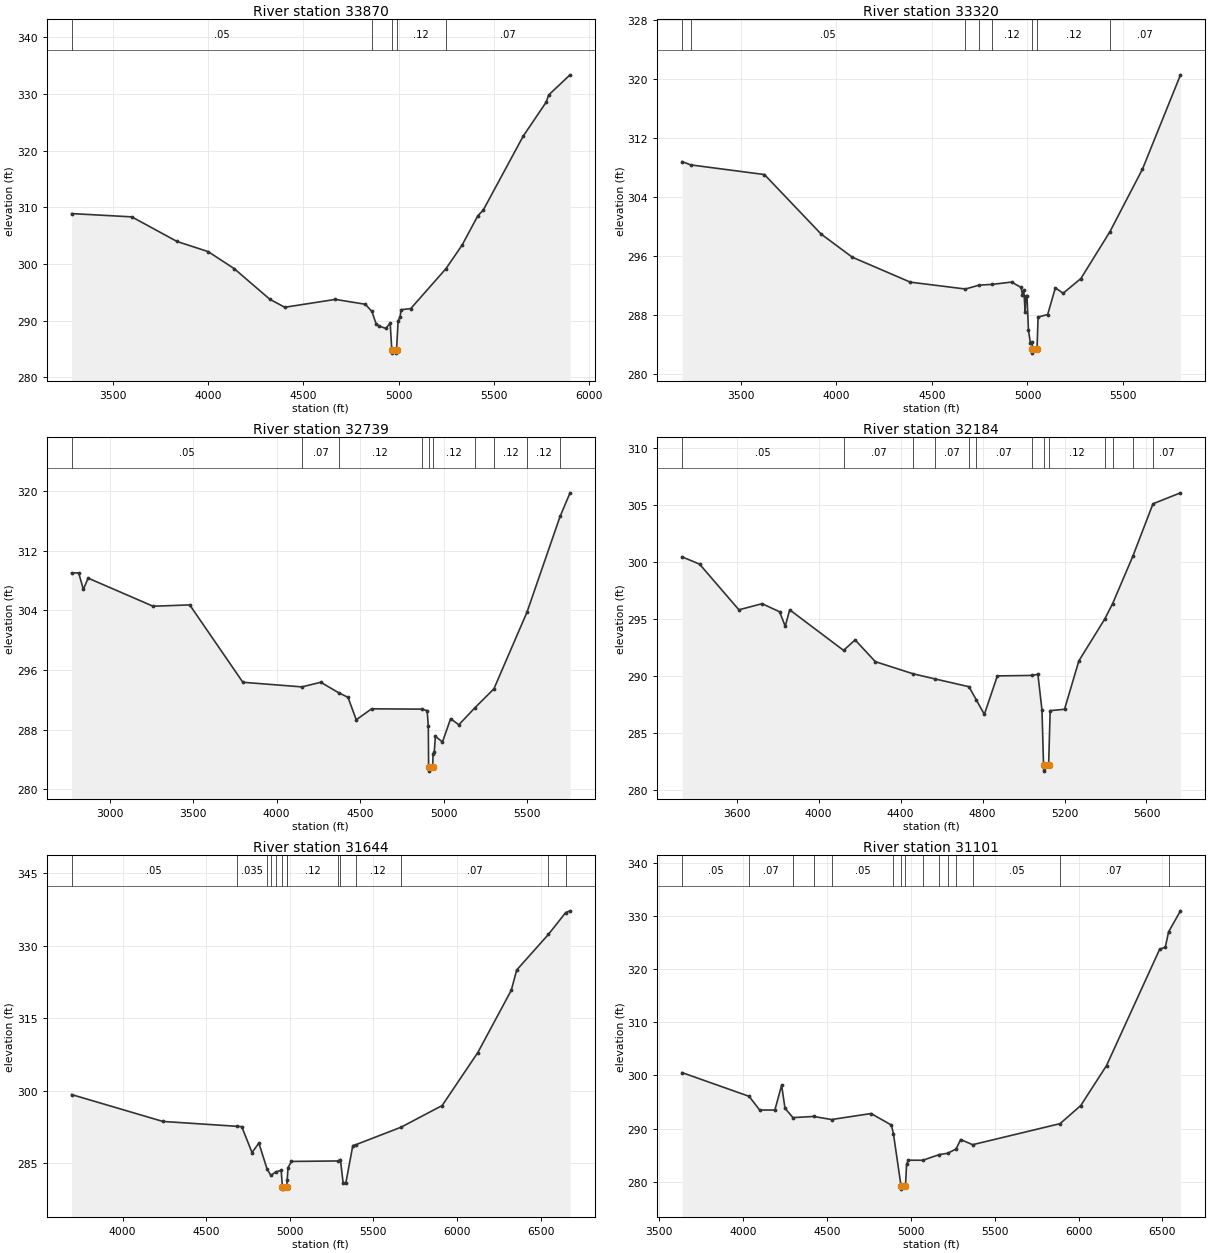
Type RM Length L Ch R = 1 ,33870   ,550,550,550
BEGIN DESCRIPTION:
SHOATS CREEK 39.0
END DESCRIPTION:
XS GIS Cut Line= 3
      2429724.99     13603625.01        2430725.       13602225.
        2431125.     13601425.01
#Sta/Elev= 30
  3284.8  308.89  3600.6  308.31  3837.8  303.97  4001.3  302.18  4137.7  299.18
  4324.5  293.78  4403.1  292.36  4668.6  293.75  4825.9  292.89  4860.2  291.62
  4882.4  289.43  4897.1  289.08  4932.8  288.62  4956.1  289.56  4964.8  284.77
  4965.3  284.27  4988.8  284.27  4989.3  284.77  4997.9  289.98  5008.1  290.68
  5013.7  291.93    5064  292.13  5248.6  299.17  5332.3  303.27  5416.2  308.52
  5444.1  309.49  5653.7  322.54  5773.9  328.52  5787.9  329.83  5899.7  333.37
#Mann= 5 ,-1 , 0
  3284.8     .05       0  4860.2     .12       0  4964.8     .05       0
  4989.3     .12       0  5248.6     .07       0
Bank Sta=4964.8,4989.3
XS Rating Curve= 0 ,0
Exp/Cntr=0.3,0.1

Type RM Length L Ch R = 1 ,33320   ,581,581,581
BEGIN DESCRIPTION:
SHOATS CREEK 38.0
END DESCRIPTION:
XS GIS Cut Line= 3
      2429824.99     13603725.01        2431125.       13602475.
        2431225.     13601675.01
#Sta/Elev= 30
  3191.6  308.77  3236.9  308.32  3622.9  307.01  3920.1  298.93  4082.7   295.8
  4386.8  292.41  4675.1  291.48  4746.3     292  4815.4  292.11  4917.3  292.42
  4966.9  291.69  4973.9  290.69  4981.1  291.34    4988  288.34  4991.6  290.52
  4997.6  290.52  5005.2  285.92  5015.2  284.19  5025.3   284.3  5025.7  283.28
  5026.2  282.78  5050.2  283.28  5055.6  287.67  5105.9  288.02  5146.3  291.65
  5186.6   290.9  5279.8   292.9  5431.4  299.24  5602.3  307.75  5801.3  320.54
#Mann= 8 ,-1 , 0
  3191.6    .035       0  3236.9     .05       0  4675.1     .07       0
  4746.3     .12       0  4815.4     .12       0  5025.7     .05       0
  5050.2     .12       0  5431.4     .07       0
Bank Sta=5025.7,5050.2
XS Rating Curve= 0 ,0
Exp/Cntr=0.3,0.1

Type RM Length L Ch R = 1 ,32739   ,555,555,555
BEGIN DESCRIPTION:
SHOATS CREEK 37.0
END DESCRIPTION:
XS GIS Cut Line= 3
      2430075.02     13604024.98        2431675.       13602475.
        2431775.     13601724.97
#Sta/Elev= 30
  2772.4     309  2814.7     309    2843  306.79  2871.3   308.3  3260.2  304.53
  3479.6  304.71  3797.8  294.34  4151.3  293.72  4264.5  294.34  4371.8  292.93
  4427.3  292.32  4476.7  289.31  4568.5  290.78  4867.6  290.74  4901.1  290.54
  4908.1  288.47  4909.9  282.93  4910.4  282.43  4934.5  282.93  4936.4  284.71
  4943.6  284.95  4950.5  287.09    4993  286.34  5041.6  289.46  5090.8  288.64
  5185.7  290.89  5300.8  293.46  5498.8  303.73  5696.9  316.56  5756.7  319.73
#Mann= 10 ,-1 , 0
  2772.4     .05       0  4151.3     .07       0  4371.8     .12       0
  4867.6     .12       0  4909.9     .05       0  4934.5     .12       0
  5185.7     .12       0  5300.8     .12       0  5498.8     .12       0
  5696.9    .035       0
Bank Sta=4909.9,4934.5
XS Rating Curve= 0 ,0
Exp/Cntr=0.3,0.1

Type RM Length L Ch R = 1 ,32184   ,540,540,540
BEGIN DESCRIPTION:
SHOATS CREEK 36.0
END DESCRIPTION:
XS GIS Cut Line= 3
      2430914.48     13603715.48        2432175.       13602625.
      2432178.51     13601858.96
#Sta/Elev= 30
  3333.2  300.43  3418.9  299.79  3610.8  295.78  3723.8  296.32  3809.3  295.61
  3836.8  294.34  3858.7  295.78  4121.7  292.22  4177.9  293.14  4276.6  291.23
  4461.7  290.16  4568.8  289.71  4733.5  289.03  4768.7   287.9  4808.6   286.6
  4872.2  289.98  5040.7  290.02    5070  290.12    5090  286.98  5097.7  282.12
  5098.2  281.62  5122.3  282.12    5130  286.93    5200  287.05    5270   291.3
  5395.6  294.95  5434.8  296.33  5533.3  300.48  5631.8  305.09    5766  306.05
#Mann= 13 ,-1 , 0
  3333.2     .05       0  4121.7     .07       0  4461.7     .05       0
  4568.8     .07       0  4733.5     .05       0  4768.7     .07       0
  5040.7     .12       0  5097.7     .05       0  5122.3     .12       0
  5395.6     .12       0  5434.8     .07       0  5533.3    .035       0
  5631.8     .07       0
Bank Sta=5097.7,5122.3
XS Rating Curve= 0 ,0
Exp/Cntr=0.3,0.1

Type RM Length L Ch R = 1 ,31644   ,543,543,543
BEGIN DESCRIPTION:
SHOATS CREEK 35.0
END DESCRIPTION:
XS GIS Cut Line= 3
      2432286.43     13604247.28        2432575.       13602975.
        2433075.       13601375.
#Sta/Elev= 30
    3695  299.18  4240.8  293.61  4683.3   292.6  4712.5  292.52    4774  287.17
    4815  289.12  4863.8  283.76  4886.9  282.41  4915.2  283.14  4948.3  283.47
  4955.9  280.08  4956.4  279.58  4981.8  280.08  4984.5   281.5  4989.3  284.03
  5010.1  285.32  5291.1  285.42  5302.6  285.72  5318.6  280.95  5334.9  280.83
  5376.8  288.62  5393.4  288.77  5665.7  292.42  5911.1  296.91  6124.3  307.89
  6324.4  320.79  6356.9     325  6546.4  332.37  6649.5  336.89  6675.9  337.26
#Mann= 14 ,-1 , 0
    3695     .05       0  4683.3    .035       0  4863.8     .07       0
  4886.9     .12       0  4915.2     .07       0  4955.9     .05       0
  4981.8     .07       0  4984.5     .12       0  5291.1     .12       0
  5302.6     .12       0  5393.4     .12       0  5665.7     .07       0
  6546.4     .05       0  6649.5     .07       0
Bank Sta=4955.9,4981.8
XS Rating Curve= 0 ,0
Exp/Cntr=0.3,0.1

Type RM Length L Ch R = 1 ,31101   ,585,585,585
BEGIN DESCRIPTION:
SHOATS CREEK 34.0
END DESCRIPTION:
XS GIS Cut Line= 3
      2432771.99      13604524.8        2432925.       13603175.
        2433125.     13601574.99
#Sta/Elev= 30
  3636.9  300.54  4036.6  296.07  4099.6  293.49  4190.2  293.49  4230.5  298.16
  4250.6  293.82    4298  292.06  4420.9  292.28  4527.8   291.7  4763.9  292.83
  4884.6  290.66  4896.7  289.06  4942.6  279.09  4943.1  278.59  4968.5  279.09
  4975.2  283.28  4985.3  284.04  5072.2  284.03  5171.2  285.11  5219.9  285.34
  5270.1  286.15  5297.7  287.93    5369  286.96  5889.9  290.92  6013.2  294.33
  6166.9  301.86  6484.3  323.82  6517.1  324.12  6536.8  327.05  6607.8  331.01
#Mann= 15 ,-1 , 0
  3636.9     .05       0  4036.6     .07       0    4298     .05       0
  4420.9     .12       0  4527.8     .05       0  4896.7     .12       0
  4942.6     .05       0  4968.5     .12       0  5072.2     .12       0
  5171.2    .035       0  5219.9     .12       0  5270.1    .035       0
    5369     .05       0  5889.9     .07       0  6536.8     .05       0
Bank Sta=4942.6,4968.5
XS Rating Curve= 0 ,0
Exp/Cntr=0.3,0.1