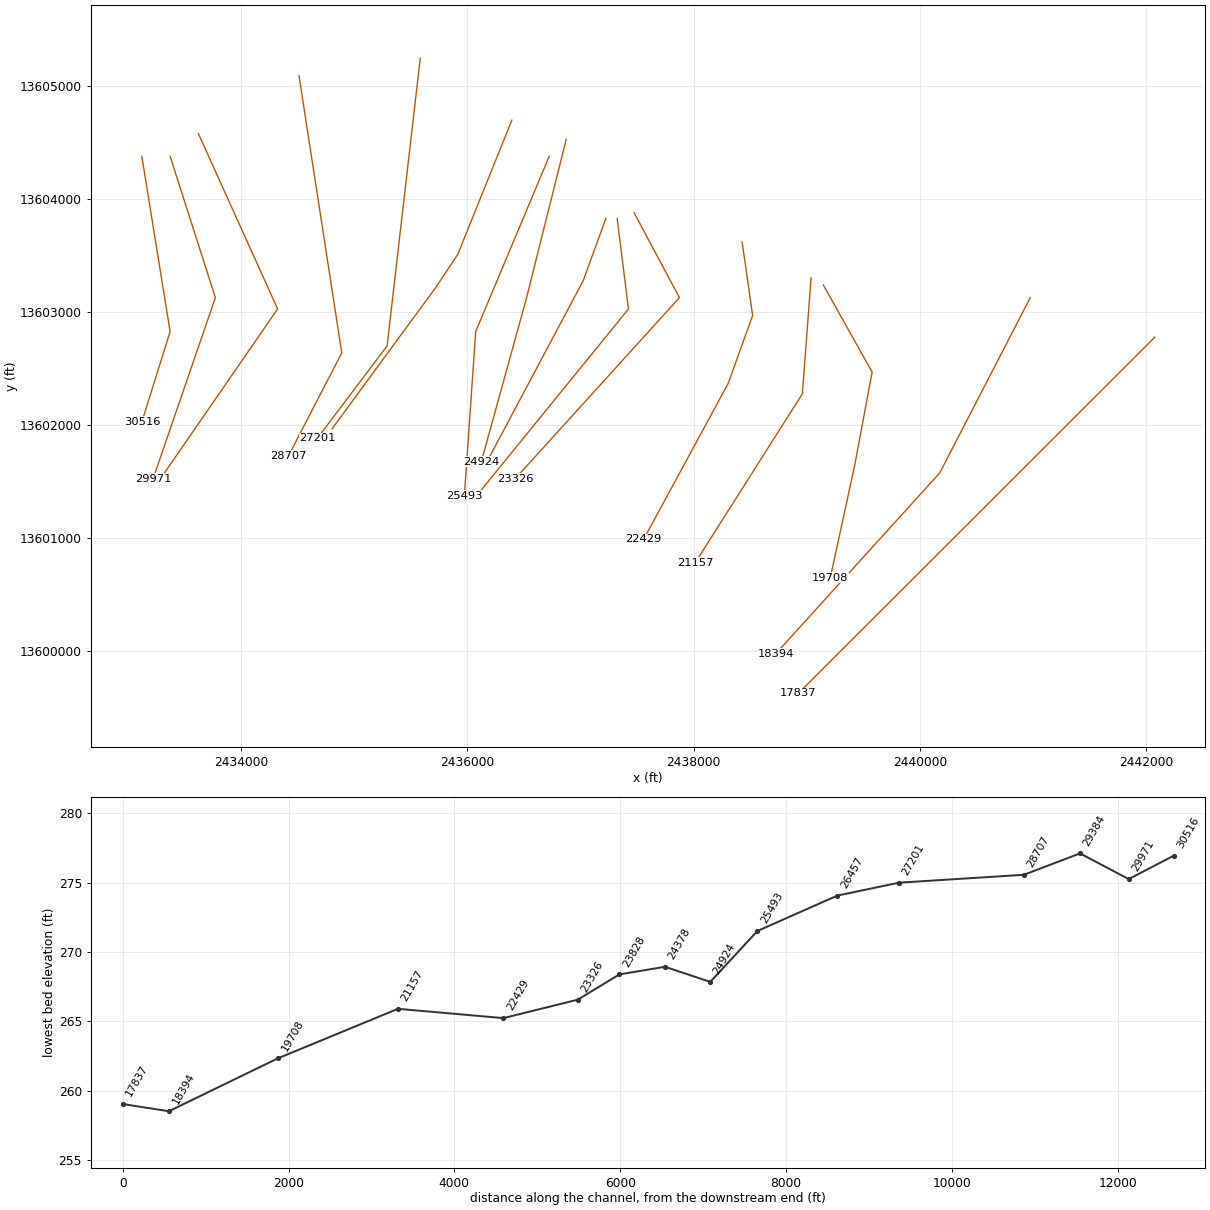
HEC-RAS study SHOATS CREEK.prj: SHOATS CREEK Base Level Engineering

--- SHOATS CREEK.g01 (geometry) --- (continued)

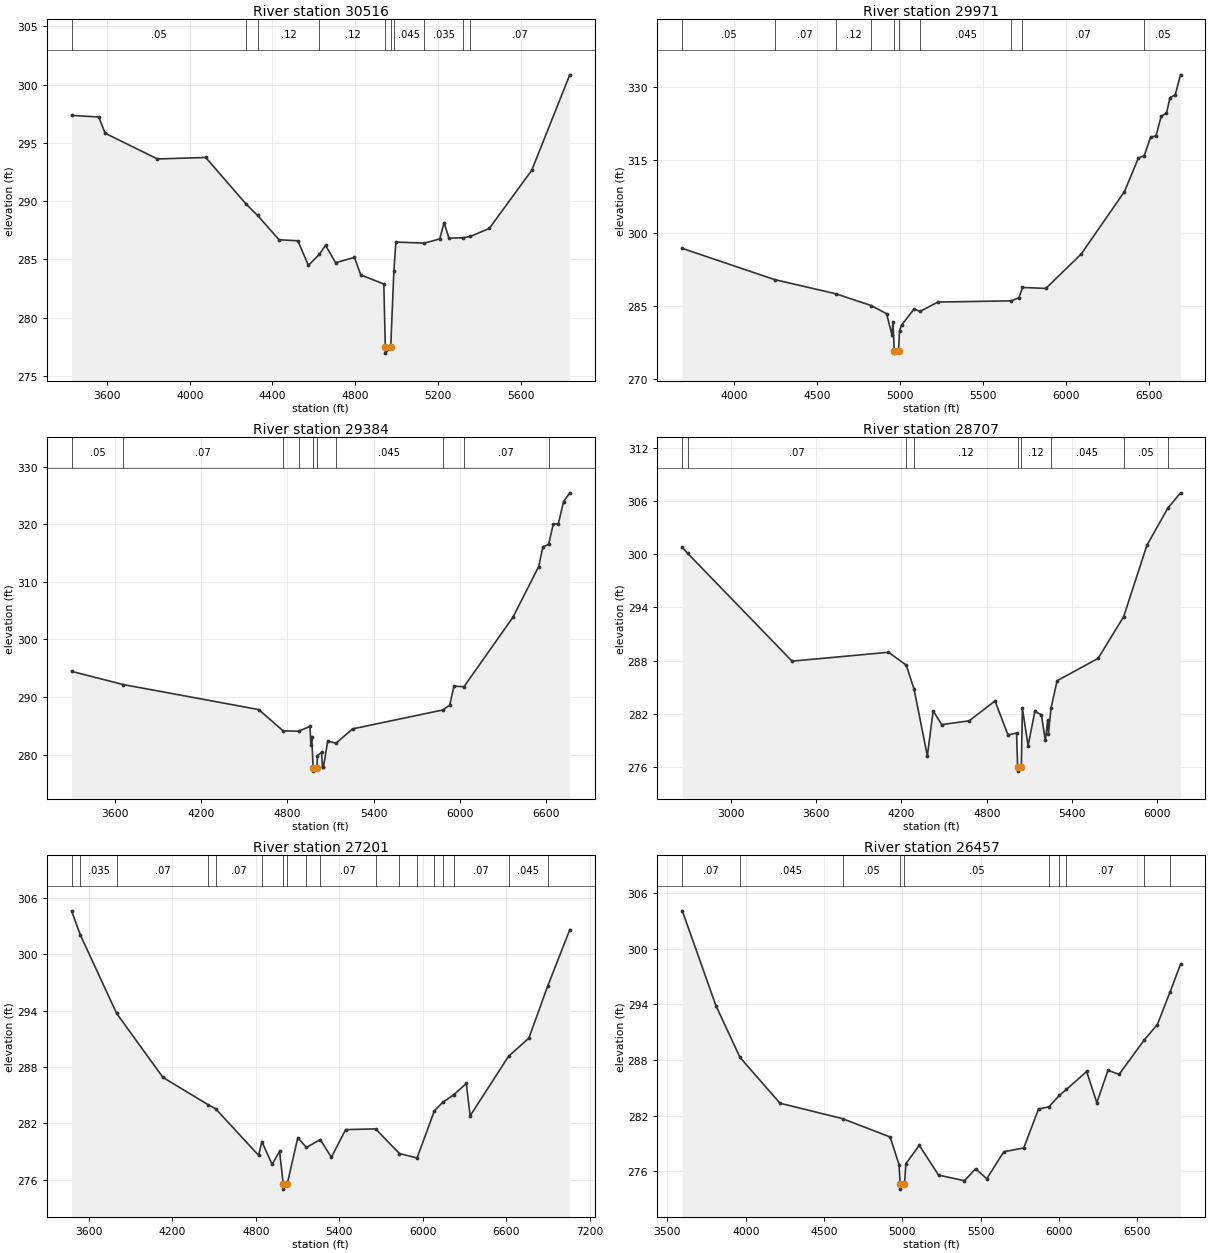
Type RM Length L Ch R = 1 ,30516   ,545,545,545
BEGIN DESCRIPTION:
SHOATS CREEK 33.0
END DESCRIPTION:
XS GIS Cut Line= 3
      2433124.99     13604375.05        2433375.       13602825.
      2433125.01     13602025.03
#Sta/Elev= 30
    3429  297.35  3560.7  297.21  3591.1  295.82  3844.3  293.61  4077.3  293.74
  4271.8  289.76    4328  288.77  4431.8  286.68    4523  286.59  4573.7  284.48
  4627.1  285.43  4656.7   286.2  4705.3  284.71  4796.5  285.16  4826.9  283.66
  4938.3  282.88  4945.6  277.45  4946.1  276.95  4971.6  277.45    4987     284
  4996.5  286.48  5134.7  286.39  5208.6  286.75  5229.6  288.15  5253.1  286.81
  5321.3  286.85  5356.2  286.96    5448  287.65  5653.4  292.64  5837.2  300.83
#Mann= 10 ,-1 , 0
    3429     .05       0  4271.8     .07       0    4328     .12       0
  4627.1     .12       0  4945.6    .045       0  4971.6     .12       0
    4987    .045       0  5134.7    .035       0  5321.3     .05       0
  5356.2     .07       0
Bank Sta=4945.6,4971.6
XS Rating Curve= 0 ,0
Exp/Cntr=0.3,0.1

Type RM Length L Ch R = 1 ,29971   ,587,587,587
BEGIN DESCRIPTION:
SHOATS CREEK 32.0
END DESCRIPTION:
XS GIS Cut Line= 3
      2433375.01     13604374.96        2433775.       13603125.
        2433225.     13601524.99
#Sta/Elev= 30
  3687.7  296.79  4243.9  290.38  4613.3  287.46  4825.8  285.05  4919.7  283.36
  4951.9  279.01  4958.1  281.69  4965.7  275.76  4966.2  275.26  4991.9  275.76
  4997.5  279.89  5010.4  281.04  5084.7  284.31  5121.8  283.84  5229.1  285.76
  5672.6  286.01  5718.4  286.68    5739  288.76  5879.9  288.56  6093.3  295.64
  6353.6  308.44  6438.2  315.39  6472.7  315.81  6512.2  319.69  6543.9  319.89
  6575.7  323.98  6607.4  324.58  6628.5  327.75  6660.3  328.37    6692  332.47
#Mann= 10 ,-1 , 0
  3687.7     .05       0  4243.9     .07       0  4613.3     .12       0
  4825.8     .12       0  4965.7     .05       0  4991.9     .12       0
  5121.8    .045       0  5672.6    .035       0    5739     .07       0
  6472.7     .05       0
Bank Sta=4965.7,4991.9
XS Rating Curve= 0 ,0
Exp/Cntr=0.3,0.1

Type RM Length L Ch R = 1 ,29384   ,677,677,677
BEGIN DESCRIPTION:
SHOATS CREEK 31.0
END DESCRIPTION:
XS GIS Cut Line= 3
      2433624.98     13604575.03        2434325.       13603025.
      2433324.98     13601574.97
#Sta/Elev= 30
  3299.7  294.45  3658.5  292.16  4599.8  287.81  4770.6   284.1  4876.8  284.05
  4956.6  284.88    4963  281.63  4968.5  283.11  4978.5  277.61    4979  277.11
  5004.8  277.61  5007.9  279.77  5036.9   280.4  5043.7   277.8  5049.8  277.77
  5079.6  282.33  5137.6  281.97  5252.7  284.45    5879  287.74  5927.5  288.58
  5957.2  291.88  6026.5  291.78  6366.3  303.83  6545.5  312.65  6575.2  316.07
  6615.2  316.54  6646.9  320.04  6682.8  320.14  6718.6  323.95  6761.9  325.48
#Mann= 10 ,-1 , 0
  3299.7     .05       0  3658.5     .07       0  4770.6     .12       0
  4876.8     .12       0  4978.5     .05       0  5004.8     .12       0
  5137.6    .045       0    5879    .035       0  6026.5     .07       0
  6615.2     .05       0
Bank Sta=4978.5,5004.8
XS Rating Curve= 0 ,0
Exp/Cntr=0.3,0.1

Type RM Length L Ch R = 1 ,28707   ,1506,1506,1506
BEGIN DESCRIPTION:
E20812
END DESCRIPTION:
XS GIS Cut Line= 3
      2434513.91     13605087.41      2434891.57     13602636.44
      2434422.21     13601728.48
#Sta/Elev= 30
  2660.3  300.75    2699  300.07  3431.7  287.95  4109.6  288.95  4233.7  287.52
  4288.9  284.84  4382.8  277.29  4423.3  282.35    4484  280.81  4676.2  281.23
  4858.3  283.47  4949.4  279.65  5010.1  279.86  5017.2  276.07  5017.7  275.57
  5043.5  276.07  5050.6  282.65  5091.1  278.43  5138.4   282.3  5184.2  281.91
    5212  279.04  5228.5  281.28  5234.1  279.79  5251.7  282.63  5294.9  285.75
  5582.8  288.26  5762.7  292.96  5925.9  300.99  6071.9  305.15  6162.3   306.9
#Mann= 9 ,-1 , 0
  2660.3     .05       0    2699     .07       0  4233.7     .12       0
  4288.9     .12       0  5017.2     .05       0  5043.5     .12       0
  5251.7    .045       0  5762.7     .05       0  6071.9    .035       0
Bank Sta=5017.2,5043.5
XS Rating Curve= 0 ,0
Exp/Cntr=0.3,0.1

Type RM Length L Ch R = 1 ,27201   ,744,744,744
BEGIN DESCRIPTION:
E20811
END DESCRIPTION:
XS GIS Cut Line= 4
      2435585.25      13605241.6      2435392.56     13603569.05
      2435292.37      13602698.1      2434675.75     13601881.08
#Sta/Elev= 30
    3474  304.65  3537.4  302.07  3797.5  293.74  4130.7  286.91  4456.6  283.99
  4509.7  283.57  4819.4   278.6    4843  280.06  4916.5  277.64  4970.4  279.02
  4997.1   275.5  4997.6     275  5024.3   275.5  5101.3  280.47  5163.8  279.44
  5262.8  280.28  5342.9   278.4  5445.6  281.34  5660.8  281.42    5833  278.79
  5959.3  278.32  6084.6  283.36  6145.7  284.27  6222.1  285.04  6313.8  286.26
  6341.1  282.81  6617.6  289.16  6763.6  291.09  6898.7  296.62  7057.9  302.64
#Mann= 18 ,-1 , 0
    3474     .05       0  3537.4    .035       0  3797.5     .07       0
  4456.6    .045       0  4509.7     .07       0    4843     .12       0
  4997.1     .05       0  5024.3     .12       0  5163.8     .12       0
  5262.8     .07       0  5660.8     .05       0    5833     .12       0
  5959.3     .05       0  6084.6     .07       0  6145.7     .12       0
  6222.1     .07       0  6617.6    .045       0  6898.7     .05       0
Bank Sta=4997.1,5024.3
XS Rating Curve= 0 ,0
Exp/Cntr=0.3,0.1

Type RM Length L Ch R = 1 ,26457   ,964,964,964
BEGIN DESCRIPTION:
E20810
END DESCRIPTION:
XS GIS Cut Line= 4
      2436394.53     13604694.32      2435916.68     13603507.39
      2435716.28      13603206.8      2434806.79     13601965.88
#Sta/Elev= 30
  3595.4  304.07  3810.3  293.83  3963.8  288.26    4219  283.33  4617.7  281.67
  4921.4  279.69  4978.5  276.72  4985.8  274.57  4986.3  274.07  5013.3  274.57
    5022  276.81  5107.7  278.79  5230.9  275.58  5396.2  274.98  5467.2  276.26
  5538.3  275.19  5647.1   278.1  5774.5  278.51  5868.6  282.71  5934.9  282.94
  6001.9  284.18  6046.7  284.82  6175.8  286.75  6240.7  283.38  6311.7  286.88
  6382.7  286.44  6543.8  290.16    6627  291.81  6708.2  295.33  6774.7  298.32
#Mann= 10 ,-1 , 0
  3595.4     .07       0  3963.8    .045       0  4617.7     .05       0
  4985.8     .05       0  5013.3     .05       0  5934.9     .07       0
  6001.9     .05       0  6046.7     .07       0  6543.8    .045       0
  6708.2     .05       0
Bank Sta=4985.8,5013.3
XS Rating Curve= 0 ,0
Exp/Cntr=0.3,0.1

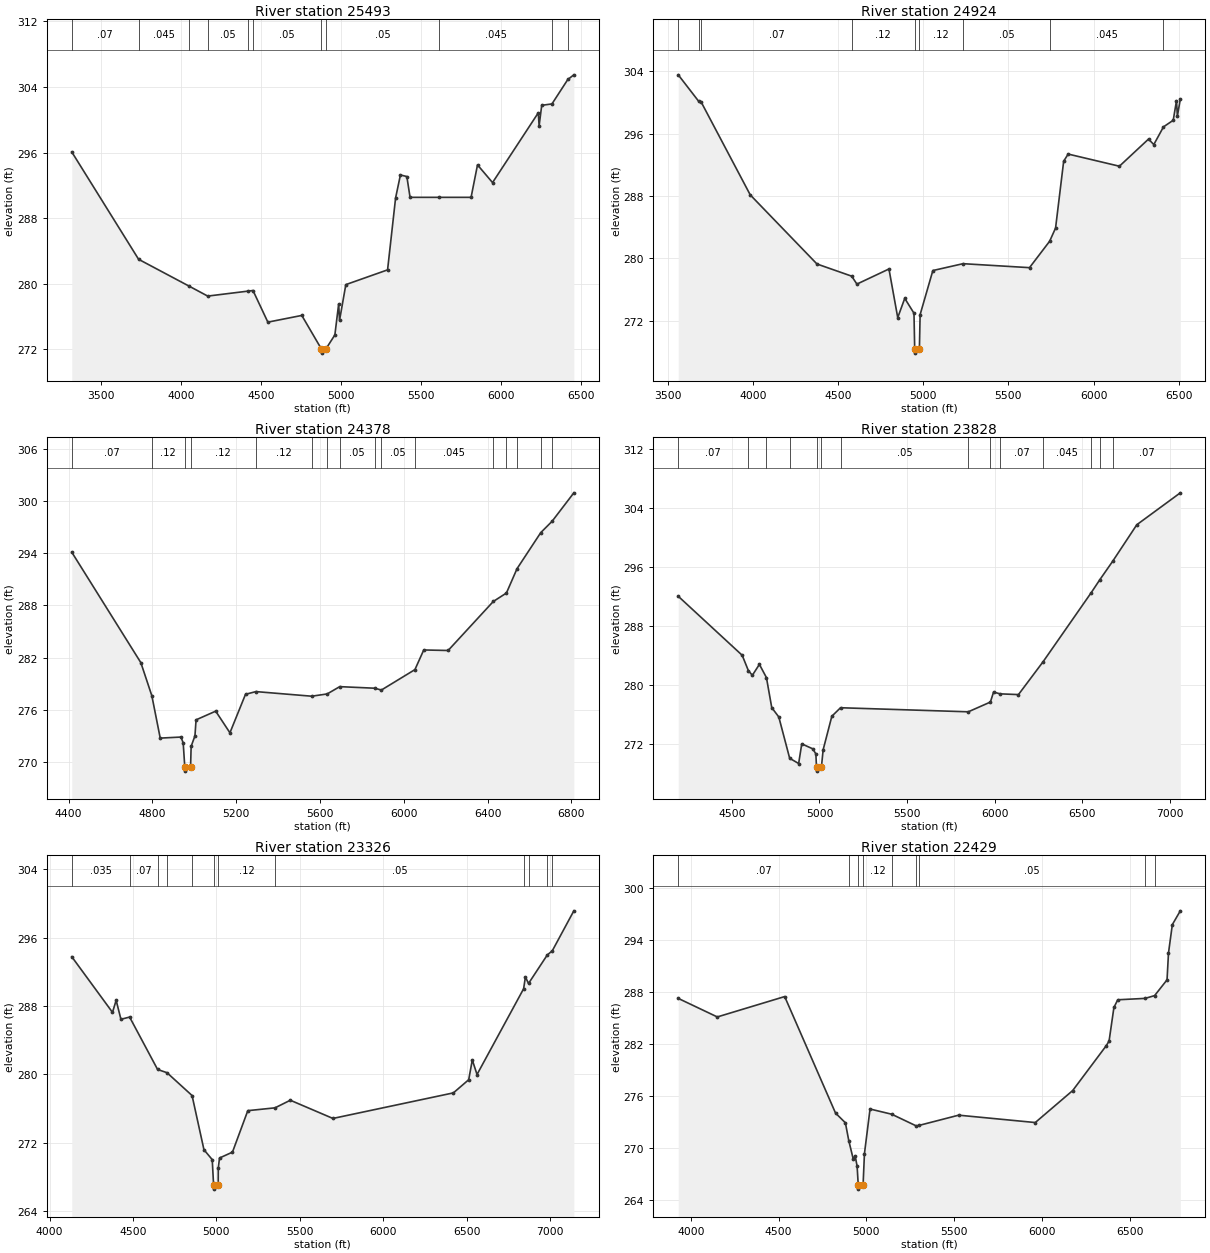
Type RM Length L Ch R = 1 ,25493   ,569,569,569
BEGIN DESCRIPTION:
SHOATS CREEK 28.0
END DESCRIPTION:
XS GIS Cut Line= 3
      2436724.99     13604374.97        2436075.       13602825.
        2435975.     13601374.98
#Sta/Elev= 30
  3318.9  296.07  3736.1  282.97  4051.8  279.69  4167.6  278.48  4420.5  279.09
  4450.2  279.16    4543   275.3  4754.8  276.12  4877.4  272.02  4877.9  271.52
    4905  272.02  4961.3  273.74    4985  277.52  4990.5  275.52  5029.7  279.88
  5290.3  281.68  5340.4  290.46  5370.5  293.26  5410.6  293.07  5430.7  290.53
  5612.9  290.53  5811.6  290.53  5851.7  294.49  5945.6  292.33  6231.3  300.85
  6236.3  299.25  6252.6  301.76  6316.5  301.93  6415.4  304.91  6453.1  305.48
#Mann= 11 ,-1 , 0
  3318.9     .07       0  3736.1    .045       0  4051.8     .07       0
  4167.6     .05       0  4420.5     .07       0  4450.2     .05       0
  4877.4     .05       0    4905     .05       0  5612.9    .045       0
  6316.5    .035       0  6415.4     .07       0
Bank Sta=4877.4,4905
XS Rating Curve= 0 ,0
Exp/Cntr=0.3,0.1

Type RM Length L Ch R = 1 ,24924   ,546,546,546
BEGIN DESCRIPTION:
SHOATS CREEK 27.0
END DESCRIPTION:
XS GIS Cut Line= 3
      2436875.01     13604525.04        2436525.       13603125.
        2436125.     13601674.99
#Sta/Elev= 30
  3562.3  303.57  3681.7  300.19  3698.1  300.03    3985  288.16  4376.7  279.29
  4580.3  277.73  4611.2  276.71  4799.3  278.65  4850.8  272.41    4892  274.88
  4946.2  272.97  4950.4  268.35  4950.9  267.85    4978  268.35  4982.2  272.79
    5057  278.45  5234.2  279.33  5624.3  278.82  5742.5  282.21  5777.3   283.9
  5824.9  292.48  5851.2   293.4    6152  291.84  6322.9  295.32    6354  294.62
  6410.8  296.89  6468.1  297.74  6487.2  300.25  6492.4  298.28  6509.6  300.45
#Mann= 9 ,-1 , 0
  3562.3     .07       0  3681.7    .035       0  3698.1     .07       0
  4580.3     .12       0  4950.4     .05       0    4978     .12       0
  5234.2     .05       0  5742.5    .045       0  6410.8    .035       0
Bank Sta=4950.4,4978
XS Rating Curve= 0 ,0
Exp/Cntr=0.3,0.1

Type RM Length L Ch R = 1 ,24378   ,550,550,550
BEGIN DESCRIPTION:
SHOATS CREEK 26.0
END DESCRIPTION:
XS GIS Cut Line= 3
        2437225.     13603824.99        2437025.       13603275.
        2436175.     13601674.99
#Sta/Elev= 30
  4414.8  294.13  4744.6  281.42  4797.1  277.61  4837.1  272.74  4936.2  272.86
  4946.8  272.18  4954.3  269.44  4954.8  268.94    4982  269.44  4984.7  271.79
  5002.9     273  5008.2  274.84  5101.9  275.84  5169.9  273.35  5244.3  277.78
  5294.2  278.09  5560.1  277.56  5634.1  277.82  5694.1  278.66  5860.7  278.48
    5893  278.27  6053.1  280.62  6095.2  282.88  6211.6  282.82  6427.2  288.46
  6489.9  289.43  6540.5  292.23  6653.8  296.38  6708.1  297.69  6811.8  300.96
#Mann= 16 ,-1 , 0
  4414.8     .07       0  4797.1     .12       0  4954.3     .05       0
    4982     .12       0  5294.2     .12       0  5560.1     .05       0
  5634.1     .07       0  5694.1     .05       0  5860.7     .07       0
    5893     .05       0  6053.1    .045       0  6427.2    .035       0
  6489.9    .045       0  6540.5    .035       0  6653.8     .07       0
  6708.1    .035       0
Bank Sta=4954.3,4982
XS Rating Curve= 0 ,0
Exp/Cntr=0.3,0.1

Type RM Length L Ch R = 1 ,23828   ,502,502,502
BEGIN DESCRIPTION:
SHOATS CREEK 25.0
END DESCRIPTION:
XS GIS Cut Line= 3
        2437325.     13603825.01        2437425.       13603025.
      2436124.99     13601424.99
#Sta/Elev= 30
  4193.3  292.06  4558.6  284.07  4593.8     282  4616.6  281.36  4656.9  282.84
  4697.1  281.05  4727.4  276.99  4767.7  275.72  4829.8  270.13  4881.1  269.42
  4898.8  272.08  4961.7  271.41  4979.4  270.72  4983.2  268.89  4983.7  268.39
  5010.9  268.89  5021.1  271.29  5070.7  275.82  5120.3  276.97  5850.1  276.42
  5976.3  277.74  5994.4  279.09    6032  278.85  6136.6  278.75  6277.7  283.21
    6552  292.54  6601.4   294.3  6674.3  296.78  6812.6  301.74  7061.1  306.06
#Mann= 14 ,-1 , 0
  4193.3     .07       0  4593.8    .035       0  4697.1    .063       0
  4829.8     .12       0  4983.2     .05       0  5010.9     .12       0
  5120.3     .05       0  5850.1     .07       0  5976.3     .05       0
    6032     .07       0  6277.7    .045       0    6552     .07       0
  6601.4    .045       0  6674.3     .07       0
Bank Sta=4983.2,5010.9
XS Rating Curve= 0 ,0
Exp/Cntr=0.3,0.1

Type RM Length L Ch R = 1 ,23326   ,897,897,897
BEGIN DESCRIPTION:
SHOATS CREEK 24.0
END DESCRIPTION:
XS GIS Cut Line= 3
      2437474.99     13603875.03        2437875.       13603125.
      2436425.01     13601525.01
#Sta/Elev= 30
    4133  293.76  4377.1  287.25    4399  288.66  4427.7  286.44  4479.7   286.7
  4647.4  280.57  4703.9  280.19    4854  277.52  4925.3  271.18  4974.9  270.02
    4983  267.07  4983.5  266.57  5010.7  267.07  5011.1  269.02  5018.5  270.21
  5096.2   270.9  5188.1  275.75  5351.2  276.08  5442.9  276.97  5698.3  274.84
  6420.2  277.83  6512.1  279.37  6533.7  281.68    6562  279.98  6841.2  290.01
    6852  291.39  6870.7  290.63  6983.2  293.97    7013  294.45  7142.3  299.13
#Mann= 12 ,-1 , 0
    4133    .035       0  4479.7     .07       0  4647.4     .05       0
  4703.9     .07       0    4854     .12       0    4983     .05       0
  5010.7     .12       0  5351.2     .05       0  6841.2     .07       0
  6870.7     .05       0  6983.2     .07       0    7013    .035       0
Bank Sta=4983,5010.7
XS Rating Curve= 0 ,0
Exp/Cntr=0.3,0.1

Type RM Length L Ch R = 1 ,22429   ,1272,1272,1272
BEGIN DESCRIPTION:
E20809
END DESCRIPTION:
XS GIS Cut Line= 4
      2438429.34     13603615.31      2438521.83     13602967.86
      2438306.02     13602366.67      2437559.19     13600988.49
#Sta/Elev= 30
  3928.3  287.24  4150.8   285.1  4534.7  287.45  4824.5  274.01  4880.6  272.89
  4899.9  270.83  4925.4   268.7    4936  269.09  4947.4  267.89  4953.7  265.74
  4954.2  265.24  4981.4  265.74  4989.1  269.33    5021  274.48  5144.3  273.88
  5283.4  272.54  5298.3  272.58    5526  273.77  5962.3  272.92  6175.5  276.61
  6366.6  281.78  6382.8  282.32  6410.3  286.19  6432.2  287.08  6587.7  287.24
  6642.1  287.56    6713  289.38  6721.3  292.48  6743.2  295.75  6788.6  297.34
#Mann= 9 ,-1 , 0
  3928.3     .07       0  4899.9     .12       0  4953.7     .05       0
  4981.4     .12       0  5144.3     .05       0  5283.4     .07       0
  5298.3     .05       0  6587.7    .035       0  6642.1     .05       0
Bank Sta=4953.7,4981.4
XS Rating Curve= 0 ,0
Exp/Cntr=0.3,0.1

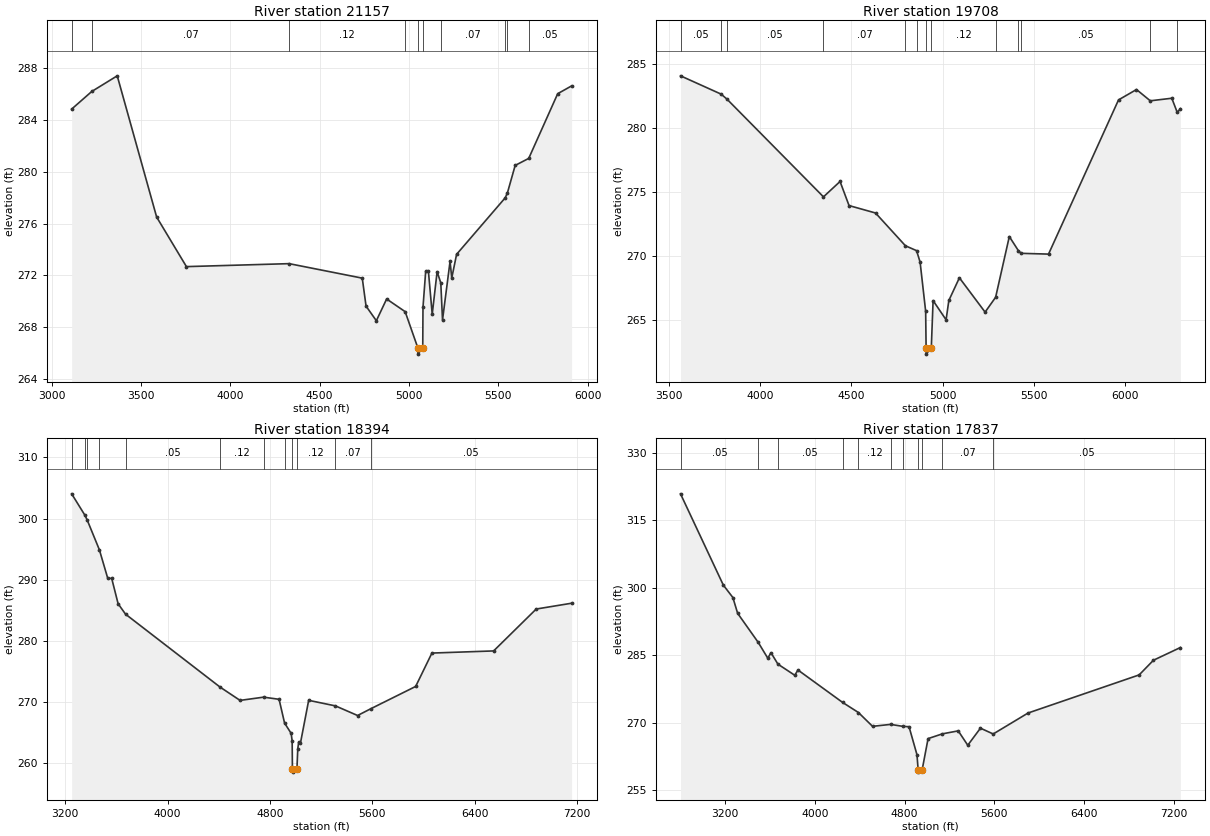
Type RM Length L Ch R = 1 ,21157   ,1449,1449,1449
BEGIN DESCRIPTION:
E20808
END DESCRIPTION:
XS GIS Cut Line= 3
      2439038.24      13603299.3      2438961.17     13602274.18
       2438013.5      13600779.5
#Sta/Elev= 30
  3112.7  284.84  3225.1   286.2  3367.7  287.41  3588.3   276.5    3755  272.67
  4329.7   272.9  4739.1  271.78  4760.3  269.62  4817.9  268.49  4875.5  270.17
  4979.2  269.19  5049.6  266.41  5050.1  265.91  5077.6  266.41  5078.9  269.52
  5094.1  272.32  5109.4   272.3  5130.6  268.99    5158  272.28  5178.6  271.41
  5188.2  268.55  5230.5  273.08  5239.9  271.79    5267  273.62  5539.4  277.99
  5551.9  278.39  5594.9  280.49  5670.7  281.03  5832.9  286.03  5910.5  286.63
#Mann= 10 ,-1 , 0
  3112.7     .05       0  3225.1     .07       0  4329.7     .12       0
  4979.2     .12       0  5049.6     .05       0  5077.6     .12       0
  5178.6     .07       0  5539.4     .05       0  5551.9    .035       0
  5670.7     .05       0
Bank Sta=5049.6,5077.6
XS Rating Curve= 0 ,0
Exp/Cntr=0.3,0.1

Type RM Length L Ch R = 1 ,19708   ,1314,1314,1314
BEGIN DESCRIPTION:
E20807
END DESCRIPTION:
XS GIS Cut Line= 4
      2439146.13     13603237.66      2439577.77     13602466.87
      2439423.62     13601642.16      2439208.03      13600648.9
#Sta/Elev= 30
  3564.1  284.07  3786.8  282.64  3818.6  282.25  4347.3  274.62  4438.2  275.82
  4487.4  273.94  4632.5  273.36  4796.4   270.8  4857.3  270.42  4876.7  269.53
  4907.2  265.68  4909.6  262.84  4910.1  262.34  4938.1  262.84  4947.9  266.52
  5019.1  265.02  5034.2  266.53    5092   268.3  5232.8  265.62  5290.5  266.78
  5365.5  271.52  5415.6  270.41  5430.2  270.21  5580.4  270.15  5963.8  282.19
  6062.2     283  6137.8  282.12  6255.7  282.32  6285.6  281.21  6302.9  281.51
#Mann= 13 ,-1 , 0
  3564.1     .05       0  3786.8     .07       0  3818.6     .05       0
  4347.3     .07       0  4796.4     .12       0  4857.3     .12       0
  4909.6     .05       0  4938.1     .12       0  5290.5     .12       0
  5415.6     .12       0  5430.2     .05       0  6137.8     .12       0
  6285.6     .05       0
Bank Sta=4909.6,4938.1
XS Rating Curve= 0 ,0
Exp/Cntr=0.3,0.1

Type RM Length L Ch R = 1 ,18394   ,557,557,557
BEGIN DESCRIPTION:
SHOATS CREEK 23.0
END DESCRIPTION:
XS GIS Cut Line= 3
      2440975.01     13603125.02        2440175.       13601575.
      2438724.98     13599974.98
#Sta/Elev= 30
  3251.4  304.04  3355.4  300.52  3372.9  299.75    3468  294.88  3532.8  290.25
  3564.2   290.2  3614.2  286.06  3672.2  284.36    4410  272.44  4566.5  270.26
  4750.3  270.79    4871  270.44    4914  266.55  4965.3  264.87  4973.2  263.64
  4975.2  259.03    4976  258.53  5010.5  259.03    5017  262.33  5023.7  263.39
  5037.9  263.27  5102.1  270.27  5311.5  269.36    5484  267.79  5588.6  268.91
  5937.5  272.54  6064.5     278  6546.4  278.35  6878.9   285.2    7155  286.15
#Mann= 12 ,-1 , 0
  3251.4     .12       0  3355.4     .07       0  3372.9     .12       0
    3468    .035       0  3672.2     .05       0    4410     .12       0
  4750.3     .12       0    4914     .12       0  4975.2     .05       0
  5010.5     .12       0  5311.5     .07       0  5588.6     .05       0
Bank Sta=4975.2,5010.5
XS Rating Curve= 0 ,0
Exp/Cntr=0.3,0.1

Type RM Length L Ch R = 1 ,17837   ,706,706,706
BEGIN DESCRIPTION:
SHOATS CREEK 22.0
END DESCRIPTION:
XS GIS Cut Line= 3
      2442074.97     13602774.97        2440525.       13601225.
      2438925.02     13599625.02
#Sta/Elev= 30
    2803  320.91  3184.8  300.61  3269.6  297.86  3312.1  294.35    3496  287.87
  3580.8  284.37  3609.1   285.6  3671.1  283.05  3821.2  280.58  3849.5  281.75
  4247.1  274.55  4388.4   272.3  4514.2  269.23  4675.3  269.66  4788.1  269.21
  4839.4  269.15  4910.1  262.92  4920.7  259.55  4921.5  259.05  4956.2  259.55
  5009.1   266.5  5136.6  267.56  5277.8  268.22  5362.7  265.03  5475.8  268.82
  5589.4  267.53  5900.1  272.19    6890  280.66  7017.3  283.92  7257.7  286.75
#Mann= 11 ,-1 , 0
    2803     .05       0    3496    .035       0  3671.1     .05       0
  4247.1     .12       0  4388.4     .12       0  4675.3     .07       0
  4788.1     .12       0  4920.7     .05       0  4956.2     .12       0
  5136.6     .07       0  5589.4     .05       0
Bank Sta=4920.7,4956.2
XS Rating Curve= 0 ,0
Exp/Cntr=0.3,0.1