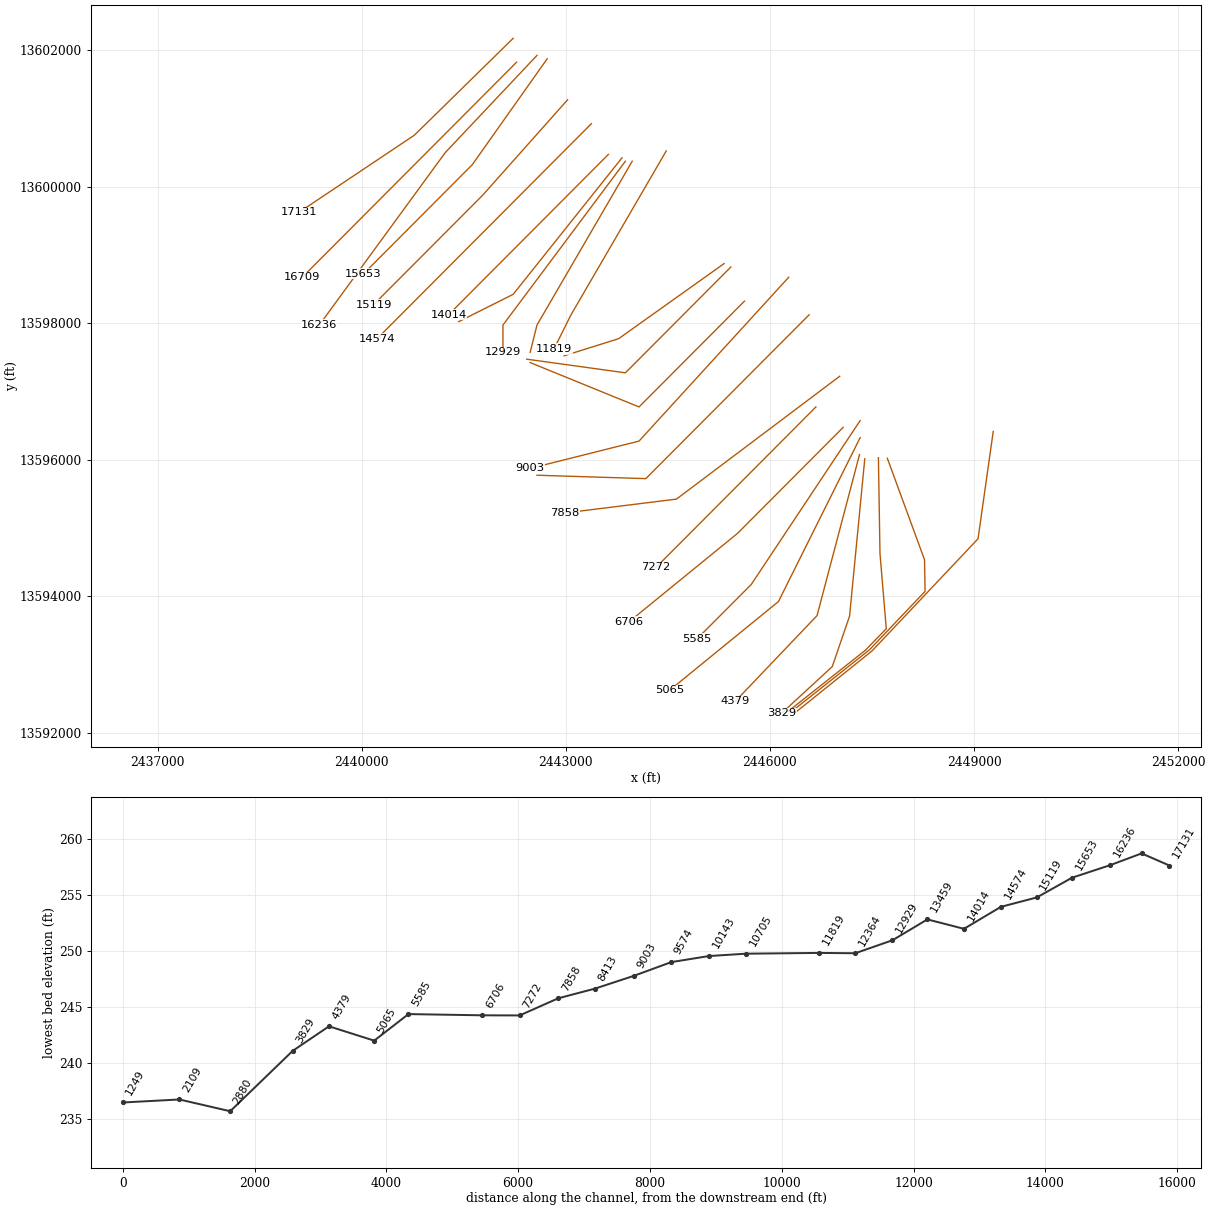
HEC-RAS study SHOATS CREEK.prj: SHOATS CREEK Base Level Engineering

--- SHOATS CREEK.g01 (geometry) --- (continued)

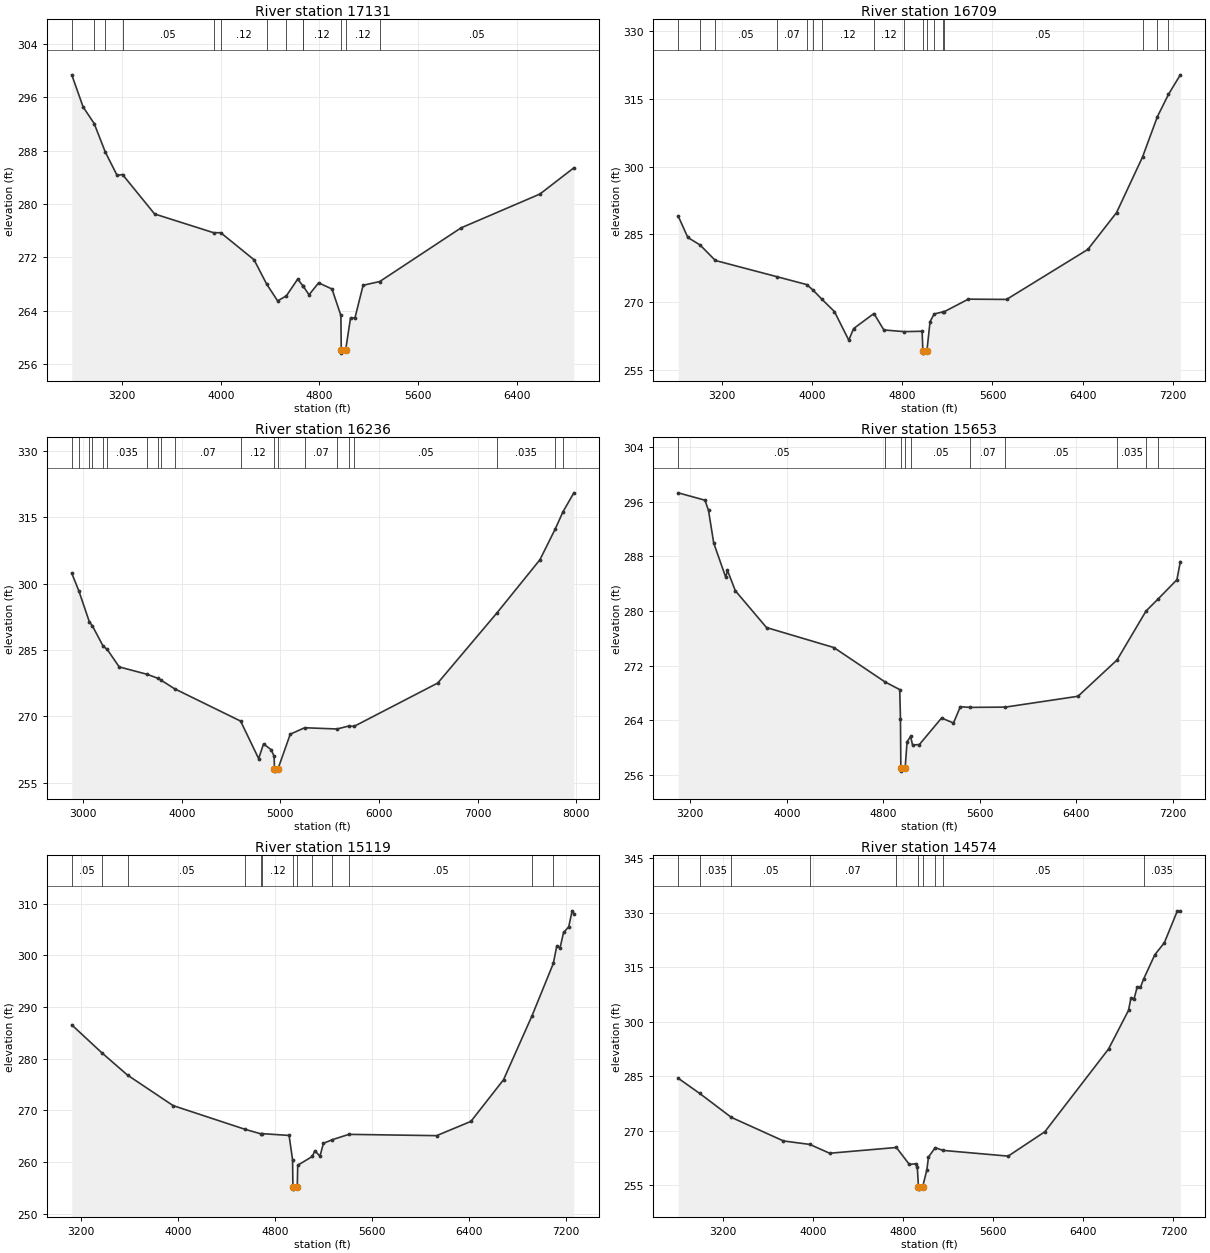
Type RM Length L Ch R = 1 ,17131   ,422,422,422
BEGIN DESCRIPTION:
SHOATS CREEK 21.0
END DESCRIPTION:
XS GIS Cut Line= 3
        2442225.       13602175.      2440772.44     13600755.79
      2439074.99     13599624.99
#Sta/Elev= 30
  2791.7  299.37  2883.6  294.56  2973.5  292.06    3063  287.81  3159.4  284.28
    3203  284.42  3463.4   278.5  3941.9  275.69  3999.6  275.69  4269.7  271.63
  4371.6  267.99  4460.6  265.47  4531.6  266.22  4623.2  268.73  4667.8  267.67
  4668.5  267.66  4715.2  266.38  4792.9  268.17  4901.3  267.25  4973.4  263.28
  4976.6  258.13  4977.4  257.63  5012.3  258.13  5051.5   262.9  5087.6  262.92
  5153.7  267.81  5288.7  268.37  5947.1  276.41  6587.1  281.49  6862.1  285.42
#Mann= 13 ,-1 , 0
  2791.7    .035       0  2973.5     .05       0    3063    .035       0
    3203     .05       0  3941.9     .07       0  3999.6     .12       0
  4371.6     .07       0  4531.6     .12       0  4667.8     .07       0
  4668.5     .12       0  4976.6     .05       0  5012.3     .12       0
  5288.7     .05       0
Bank Sta=4976.6,5012.3
XS Rating Curve= 0 ,0
Exp/Cntr=0.3,0.1

Type RM Length L Ch R = 1 ,16709   ,473,473,473
BEGIN DESCRIPTION:
SHOATS CREEK 20.0
END DESCRIPTION:
XS GIS Cut Line= 3
      2442275.03     13601825.03        2440725.       13600275.
      2439125.01     13598675.01
#Sta/Elev= 30
  2812.1  289.04    2897  284.32  3006.1  282.65  3141.4  279.22  3686.6  275.64
  3952.9  273.88  4010.3  272.61  4088.1  270.61  4198.1  267.91  4325.4  261.58
  4367.8  264.14  4548.5  267.48  4636.5  263.84  4816.6  263.47  4975.9  263.55
  4982.8  259.21  4983.6  258.71  5018.5  259.21  5046.6  265.71  5083.4  267.38
    5158  267.83  5170.1  267.85    5386  270.66  5725.4   270.6  6446.7  281.67
  6701.2  289.82  6931.7  302.13  7063.4  311.05    7162     316  7266.9  320.32
#Mann= 17 ,-1 , 0
  2812.1     .05       0  3006.1    .035       0  3141.4     .05       0
  3686.6     .07       0  3952.9     .12       0  4010.3     .07       0
  4088.1     .12       0  4548.5     .12       0  4816.6     .12       0
  4982.8     .05       0  5018.5     .12       0  5083.4     .05       0
    5158     .07       0  5170.1     .05       0  6931.7     .07       0
  7063.4     .12       0    7162     .07       0
Bank Sta=4982.8,5018.5
XS Rating Curve= 0 ,0
Exp/Cntr=0.3,0.1

Type RM Length L Ch R = 1 ,16236   ,583,583,583
BEGIN DESCRIPTION:
SHOATS CREEK 19.0
END DESCRIPTION:
XS GIS Cut Line= 3
      2442574.97     13601924.97      2441227.19     13600501.44
        2439375.       13597975.
#Sta/Elev= 30
  2884.1  302.33  2955.3  298.38  3062.5  291.36  3094.2  290.41    3202  285.89
  3243.8  285.13  3365.2  281.19  3649.7  279.51  3759.9   278.6  3788.6  278.21
  3927.5  276.25  4596.8  268.96  4779.9  260.49  4829.2  263.81  4907.8  262.49
  4937.1  260.98  4940.1  258.17  4940.9  257.67  4975.8  258.17  5100.4  266.01
  5246.8  267.46  5575.1  267.18  5697.4  267.87    5746  267.75  6596.6  277.55
    7200  293.45  7633.2  305.38  7790.4  312.41  7867.6  316.22  7977.1  320.47
#Mann= 20 ,-1 , 0
  2884.1     .05       0  2955.3    .035       0  3062.5     .05       0
  3094.2    .035       0    3202     .05       0  3243.8    .035       0
  3649.7     .05       0  3759.9    .035       0  3788.6     .05       0
  3927.5     .07       0  4596.8     .12       0  4940.1     .05       0
  4975.8     .12       0  5246.8     .07       0  5575.1     .05       0
  5697.4     .07       0    5746     .05       0    7200    .035       0
  7790.4     .12       0  7867.6    .035       0
Bank Sta=4940.1,4975.8
XS Rating Curve= 0 ,0
Exp/Cntr=0.3,0.1

Type RM Length L Ch R = 1 ,15653   ,534,534,534
BEGIN DESCRIPTION:
SHOATS CREEK 18.0
END DESCRIPTION:
XS GIS Cut Line= 3
        2442725.       13601875.        2441625.       13600325.
        2440025.       13598725.
#Sta/Elev= 30
  3099.6  297.32    3321  296.24  3350.6  294.75  3393.9  289.96  3493.2  284.96
    3508  285.95  3573.2  282.97  3831.6  277.58  4390.1  274.65  4813.6  269.62
  4936.3  268.49  4942.4   264.2  4945.6  257.04  4946.4  256.54  4981.4  257.04
  4997.2  260.84  5026.6  261.63  5042.7  260.36  5099.3  260.44  5283.1  264.32
  5382.1  263.59  5438.7  265.98  5519.9  265.88  5812.1  265.92  6414.5  267.51
  6738.4  272.83  6979.1  280.01  7081.8  281.82  7234.7  284.58    7263  287.23
#Mann= 10 ,-1 , 0
  3099.6     .05       0  4813.6     .07       0  4945.6     .05       0
  4981.4     .07       0  5026.6     .05       0  5519.9     .07       0
  5812.1     .05       0  6738.4    .035       0  6979.1     .05       0
  7081.8    .035       0
Bank Sta=4945.6,4981.4
XS Rating Curve= 0 ,0
Exp/Cntr=0.3,0.1

Type RM Length L Ch R = 1 ,15119   ,545,545,545
BEGIN DESCRIPTION:
SHOATS CREEK 17.0
END DESCRIPTION:
XS GIS Cut Line= 3
      2443024.98     13601274.98        2441775.       13599875.
      2440175.03     13598275.03
#Sta/Elev= 30
  3123.2  286.54  3369.8  281.17  3582.7  276.83  3958.8  270.93  4553.6  266.33
  4682.9  265.47  4690.6  265.51  4915.1  265.16  4943.6  260.44  4946.5  255.28
  4947.3  254.78  4982.4  255.28  4986.2   259.4  5106.1  261.09  5127.3  262.19
  5169.7  261.16    5198  263.64  5272.8  264.35  5408.3  265.37  6131.4  265.12
  6414.2  267.88  6682.9  275.93  6918.6  288.34  7093.8  298.44  7121.3  301.72
  7149.6  301.49  7177.9   304.4  7220.3  305.49  7248.6  308.59  7262.7  308.05
#Mann= 13 ,-1 , 0
  3123.2     .05       0  3369.8    .035       0  3582.7     .05       0
  4553.6    .035       0  4682.9     .07       0  4690.6     .12       0
  4946.5     .05       0  4982.4     .12       0  5106.1     .05       0
  5272.8     .07       0  5408.3     .05       0  6918.6    .035       0
  7093.8     .05       0
Bank Sta=4946.5,4982.4
XS Rating Curve= 0 ,0
Exp/Cntr=0.3,0.1

Type RM Length L Ch R = 1 ,14574   ,560,560,560
BEGIN DESCRIPTION:
SHOATS CREEK 16.0
END DESCRIPTION:
XS GIS Cut Line= 3
      2443374.97     13600924.97        2441825.       13599375.
      2440225.02     13597775.02
#Sta/Elev= 30
  2806.9  284.47  2997.7  280.28  3278.1   273.7  3740.2  267.21  3974.5  266.25
  4150.4  263.82  4742.5  265.41  4857.5  260.73    4914  260.94  4928.2  259.95
  4938.5  254.44  4939.3  253.94  4974.4  254.44    5013  259.27  5027.2  262.78
  5087.6  265.37    5154  264.61  5734.3  263.03  6059.6  269.74  6625.2  292.54
    6802  303.17  6823.2   306.5  6851.5  306.36  6879.8  309.67  6908.1  309.51
  6935.5  311.76  7035.4  318.47  7120.2   321.8  7233.3   330.4  7261.6  330.57
#Mann= 10 ,-1 , 0
  2806.9     .05       0  2997.7    .035       0  3278.1     .05       0
  3974.5     .07       0  4742.5     .12       0  4938.5     .05       0
  4974.4     .12       0  5087.6     .07       0    5154     .05       0
  6935.5    .035       0
Bank Sta=4938.5,4974.4
XS Rating Curve= 0 ,0
Exp/Cntr=0.3,0.1

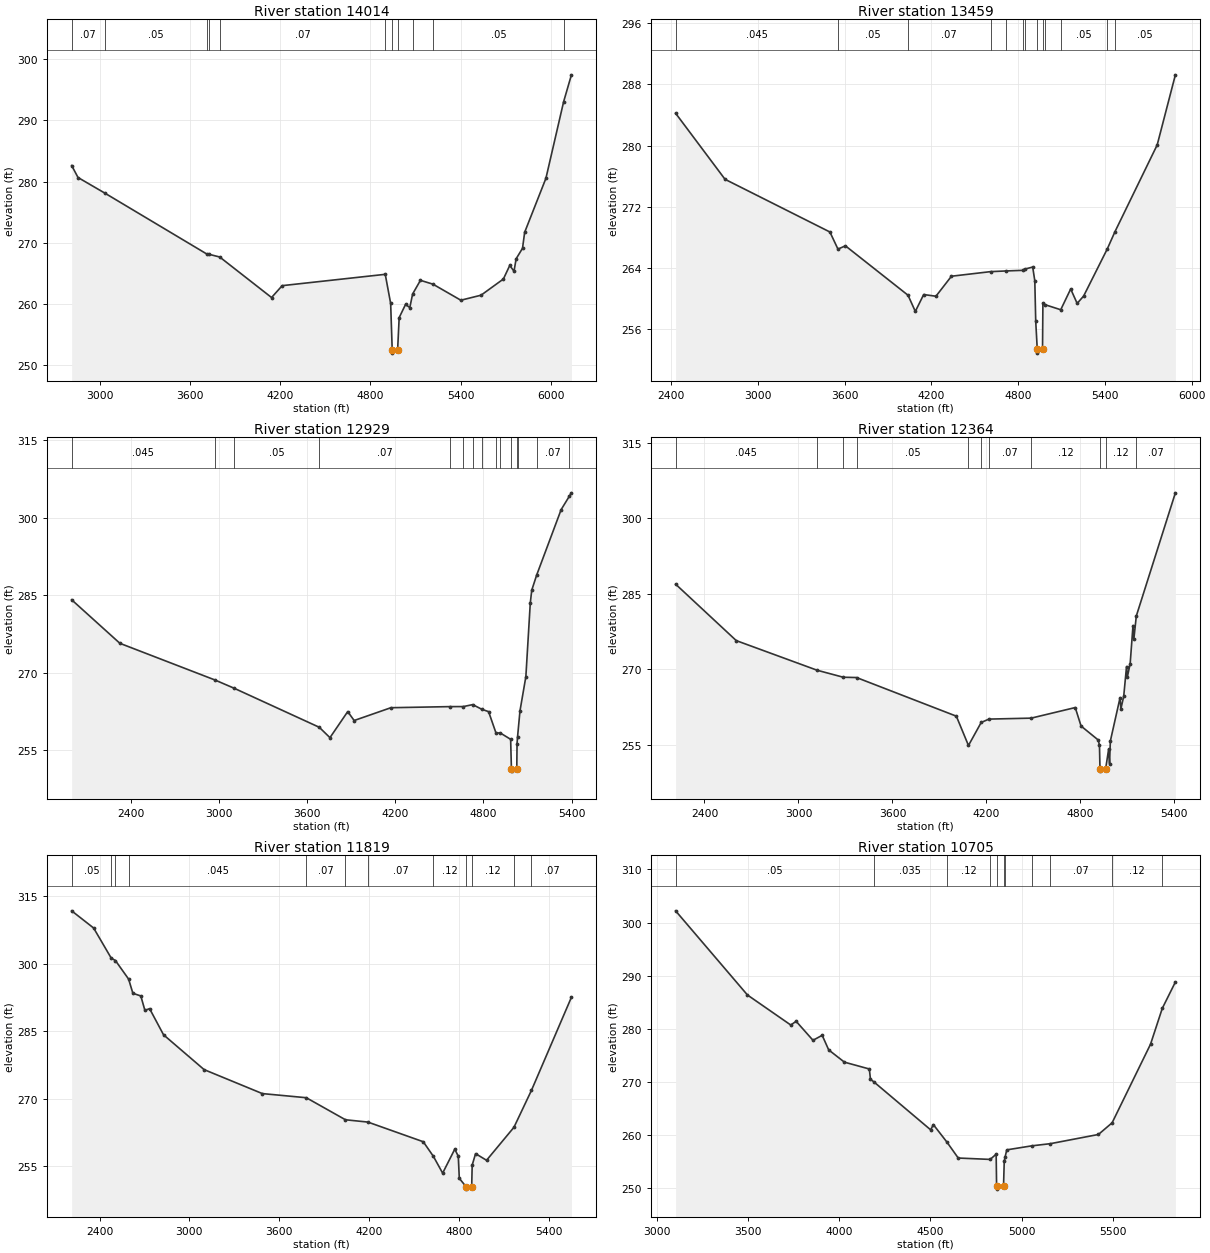
Type RM Length L Ch R = 1 ,14014   ,555,555,555
BEGIN DESCRIPTION:
SHOATS CREEK 15.0
END DESCRIPTION:
XS GIS Cut Line= 3
      2443624.98     13600474.98        2442075.       13598925.
      2441274.99     13598124.99
#Sta/Elev= 30
  2813.1  282.62  2855.5  280.66  3031.8  278.14  3710.8  268.18    3728  268.11
  3797.5  267.68  4142.4  261.06  4213.1     263  4898.4  264.85  4934.4  260.09
  4944.7  252.48  4945.5  251.98  4980.6  252.48    4991  257.78  5033.4  259.93
  5061.7  259.42  5080.5  261.64  5132.4  263.87  5215.8  263.24  5401.1  260.62
  5535.4  261.44  5683.9  264.08  5726.4   266.3  5754.6  265.35  5768.8  267.39
  5811.2   269.1  5825.4  271.71  5966.8  280.53  6084.7  293.05  6136.5  297.43
#Mann= 11 ,-1 , 0
  2813.1     .07       0  3031.8     .05       0  3710.8     .07       0
    3728     .05       0  3797.5     .07       0  4898.4     .12       0
  4944.7     .05       0  4980.6     .12       0  5080.5     .07       0
  5215.8     .05       0  6084.7     .07       0
Bank Sta=4944.7,4980.6
XS Rating Curve= 0 ,0
Exp/Cntr=0.3,0.1

Type RM Length L Ch R = 1 ,13459   ,530,530,530
BEGIN DESCRIPTION:
SHOATS CREEK 14.0
END DESCRIPTION:
XS GIS Cut Line= 3
      2443825.02     13600425.03        2442225.       13598425.
      2441425.01     13598025.01
#Sta/Elev= 30
  2431.8  284.23  2773.6  275.58  3498.8  268.68  3554.4  266.44    3606  266.87
  4038.9   260.4  4089.4  258.28  4147.1  260.49  4231.9  260.27  4339.2  262.89
  4609.5  263.49  4716.7  263.58  4831.5  263.66  4845.9  263.82    4901  264.09
  4915.5  262.29  4921.9  256.97  4932.5  253.32  4933.3  252.82  4968.9  253.32
  4971.5  259.39  4983.5  259.18  5094.7   258.5  5163.6  261.22  5208.3  259.33
    5253  260.29  5416.8  266.47    5470  268.73  5761.7  280.08  5887.5  289.26
#Mann= 13 ,-1 , 0
  2431.8    .045       0  3554.4     .05       0  4038.9     .07       0
  4609.5     .12       0  4716.7     .07       0  4831.5     .12       0
  4845.9     .12       0  4932.5     .05       0  4968.9     .12       0
  4983.5     .12       0  5094.7     .05       0  5416.8     .07       0
    5470     .05       0
Bank Sta=4932.5,4968.9
XS Rating Curve= 0 ,0
Exp/Cntr=0.3,0.1

Type RM Length L Ch R = 1 ,12929   ,565,565,565
BEGIN DESCRIPTION:
SHOATS CREEK 13.0
END DESCRIPTION:
XS GIS Cut Line= 3
      2443874.97     13600374.96        2442075.       13597975.
        2442075.     13597574.95
#Sta/Elev= 30
  1999.2  284.14  2327.3  275.71  2972.2  268.63  3101.5  267.05  3683.8  259.45
  3756.4  257.44  3877.3  262.49    3921  260.76    4171  263.24  4569.8  263.45
  4663.9  263.46  4727.7  263.84  4789.8  262.93  4835.6  262.48  4885.6  258.37
  4915.7  258.34  4985.6  257.12  4990.9  251.46  4991.8  250.96  5027.4  251.46
  5029.2  256.29  5032.4  257.52  5049.2  262.64  5089.2  269.26  5119.2   283.5
  5129.2  285.99  5162.6  288.92  5329.2   301.6    5384  304.15  5399.2  304.85
#Mann= 15 ,-1 , 0
  1999.2    .045       0  2972.2     .07       0  3101.5     .05       0
  3683.8     .07       0  4569.8     .12       0  4663.9     .07       0
  4727.7     .12       0  4789.8     .12       0  4885.6     .05       0
  4915.7     .12       0  4990.9     .05       0  5027.4     .12       0
  5032.4     .12       0  5162.6     .07       0    5384     .05       0
Bank Sta=4990.9,5027.4
XS Rating Curve= 0 ,0
Exp/Cntr=0.3,0.1

Type RM Length L Ch R = 1 ,12364   ,545,545,545
BEGIN DESCRIPTION:
SHOATS CREEK 12.0
END DESCRIPTION:
XS GIS Cut Line= 3
      2443974.99     13600374.99        2442575.       13597975.
        2442475.     13597574.98
#Sta/Elev= 30
  2215.6  286.92    2603  275.71  3119.1  269.83  3285.9  268.44  3370.7  268.38
    4008  260.71  4085.4  254.89  4166.6  259.46  4216.3  260.13  4485.8  260.32
  4767.1  262.42  4804.3  258.75    4913     256  4921.7  254.97    4925   250.3
  4925.9   249.8  4961.5   250.3  4980.4  254.18  4986.2  251.28  4991.2  255.77
  5053.3  264.39  5058.5  262.16  5076.5  264.64  5094.6  270.57  5099.7  268.49
  5117.8  271.16  5135.8   278.7    5141  275.94    5157   280.6  5406.4  305.05
#Mann= 11 ,-1 , 0
  2215.6    .045       0  3119.1     .05       0  3285.9     .07       0
  3370.7     .05       0  4085.4     .07       0  4166.6     .05       0
  4216.3     .07       0  4485.8     .12       0    4925     .05       0
  4961.5     .12       0    5157     .07       0
Bank Sta=4925,4961.5
XS Rating Curve= 0 ,0
Exp/Cntr=0.3,0.1

Type RM Length L Ch R = 1 ,11819   ,1114,1114,1114
BEGIN DESCRIPTION:
SHOATS CREEK 11.0
END DESCRIPTION:
XS GIS Cut Line= 3
      2444474.99     13600524.98        2443075.       13598125.
      2442824.99     13597624.98
#Sta/Elev= 30
  2213.8  311.79  2360.6  307.96  2478.1  301.26  2505.9  300.73    2594   296.6
  2622.7  293.43  2675.6  292.84  2702.9  289.63  2734.3  290.01  2827.4  284.19
  3098.2  276.44  3487.2   271.1  3780.8  270.18  4042.4  265.27  4191.8  264.76
  4561.8  260.38  4629.4  257.13  4691.3  253.39  4772.3  258.73  4795.5  257.16
  4802.5  252.23  4848.7  250.33  4849.6  249.83  4885.2  250.33  4888.5  255.18
  4911.2  257.73  4984.4  256.25  5167.5   263.6  5284.2  271.81  5551.3  292.55
#Mann= 12 ,-1 , 0
  2213.8     .05       0  2478.1     .07       0  2505.9     .05       0
    2594    .045       0  3780.8     .07       0  4042.4     .05       0
  4191.8     .07       0  4629.4     .12       0  4848.7     .05       0
  4885.2     .12       0  5167.5     .12       0  5284.2     .07       0
Bank Sta=4848.7,4885.2
XS Rating Curve= 0 ,0
Exp/Cntr=0.3,0.1

Type RM Length L Ch R = 1 ,10705   ,562,562,562
BEGIN DESCRIPTION:
SHOATS CREEK 10.0
END DESCRIPTION:
XS GIS Cut Line= 3
        2445325.       13598875.        2443775.       13597775.
      2442975.01       13597525.
#Sta/Elev= 30
  3103.6  302.21  3497.3  286.35  3734.7  280.69  3764.2  281.39  3856.5  277.81
  3906.9  278.75  3942.6     276  4028.7  273.69  4165.3   272.4  4171.4  270.47
  4189.5  269.99  4501.5  260.93  4515.9  261.93    4591   258.6  4652.4  255.62
  4827.5  255.36  4860.3  256.35  4862.7  250.26  4863.6  249.76  4900.6  250.26
  4904.6  255.05  4909.5  255.84  4918.4  257.16  5055.8  257.92  5157.9  258.33
  5420.7  260.06  5495.7  262.26  5706.2  277.07  5770.8  283.84  5842.4  288.79
#Mann= 11 ,-1 , 0
  3103.6     .05       0  4189.5    .035       0    4591     .12       0
  4827.5     .12       0  4862.7    .035       0  4900.6     .12       0
  4909.5    .035       0  5055.8     .12       0  5157.9     .07       0
  5495.7     .12       0  5770.8     .05       0
Bank Sta=4862.7,4900.6
XS Rating Curve= 0 ,0
Exp/Cntr=0.3,0.1

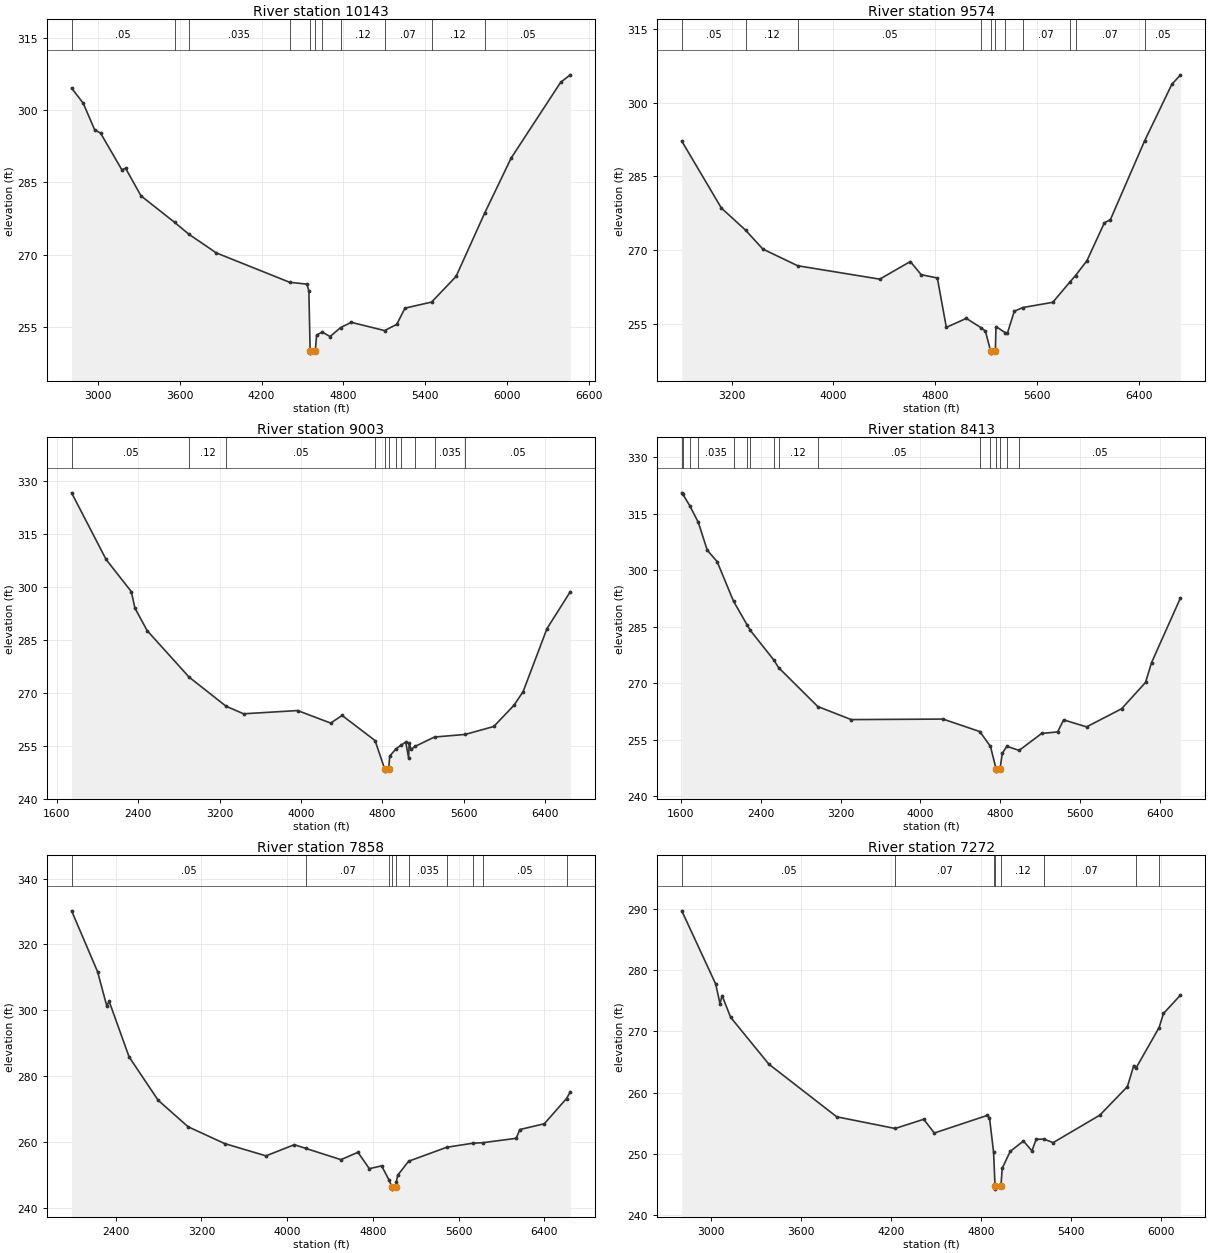
Type RM Length L Ch R = 1 ,10143   ,569,569,569
BEGIN DESCRIPTION:
SHOATS CREEK 9.0
END DESCRIPTION:
XS GIS Cut Line= 3
      2445424.97     13598824.97        2443875.       13597275.
      2442425.02       13597475.
#Sta/Elev= 30
  2807.6  304.56  2892.4  301.43  2977.3  295.86  3019.7  295.22  3175.3  287.63
  3203.5   287.9  3316.7  282.18  3562.7  276.69  3666.7  274.24  3868.2  270.35
  4405.2  264.26  4532.9  263.86    4547  262.45  4556.3  250.05  4557.3  249.55
  4594.3  250.05  4603.6   253.3  4644.6  253.92  4702.6  252.99  4779.9  254.86
  4858.2  255.94    5102  254.23  5191.4  255.52  5251.3  258.88  5446.9  260.15
  5626.1  265.47  5834.6  278.54  6029.2     290  6392.7  305.75  6463.3   307.3
#Mann= 11 ,-1 , 0
  2807.6     .05       0  3562.7     .12       0  3666.7    .035       0
  4405.2     .12       0  4556.3     .05       0  4594.3     .12       0
  4644.6     .12       0  4779.9     .12       0    5102     .07       0
  5446.9     .12       0  5834.6     .05       0
Bank Sta=4556.3,4594.3
XS Rating Curve= 0 ,0
Exp/Cntr=0.3,0.1

Type RM Length L Ch R = 1 ,9574    ,571,571,571
BEGIN DESCRIPTION:
SHOATS CREEK 8.0
END DESCRIPTION:
XS GIS Cut Line= 3
        2445625.       13598325.        2444075.       13596775.
      2442475.02     13597424.99
#Sta/Elev= 30
  2808.1  292.19  3119.2  278.56  3309.3  274.06  3444.5  270.22  3718.4  266.81
  4363.7  264.08  4604.1  267.67    4689     265  4816.3  264.31    4887  254.26
  5044.3  256.09  5161.4  254.16  5194.2   253.5  5234.2  249.51  5235.2  249.01
  5272.2  249.51  5277.2  254.43  5350.7  253.16  5367.1  253.09  5421.1  257.55
  5488.8   258.3  5723.3  259.36  5855.6  263.42  5902.3  264.82  5992.1  267.85
  6128.7  275.54  6176.6  276.22    6445  292.24  6658.8  303.75  6727.1   305.7
#Mann= 11 ,-1 , 0
  2808.1     .05       0  3309.3     .12       0  3718.4     .05       0
  5161.4     .12       0  5234.2     .05       0  5272.2     .12       0
  5350.7     .05       0  5488.8     .07       0  5855.6     .12       0
  5902.3     .07       0    6445     .05       0
Bank Sta=5234.2,5272.2
XS Rating Curve= 0 ,0
Exp/Cntr=0.3,0.1

Type RM Length L Ch R = 1 ,9003    ,590,590,590
BEGIN DESCRIPTION:
SHOATS CREEK 7.0
END DESCRIPTION:
XS GIS Cut Line= 3
      2446274.99     13598674.99        2444075.       13596275.
        2442475.       13595875.
#Sta/Elev= 30
  1743.8   326.7  2083.2   307.8  2331.1  298.69  2366.9     294  2487.1  287.62
  2899.5  274.44  3263.4  266.18  3435.5  264.04  3966.4  264.96    4292  261.41
  4404.8  263.57  4728.6  256.45  4824.8  248.28  4825.8  247.78  4862.9  248.28
  4872.2  252.04  4930.4  253.97  4981.1   255.1  5030.5  256.01  5058.8   251.5
    5064  255.75    5082  253.93  5125.3  254.84  5313.5  257.45  5615.5  258.19
  5896.3  260.44  6094.8  266.45  6184.9  270.33  6419.4  288.18  6648.8  298.66
#Mann= 11 ,-1 , 0
  1743.8     .05       0  2899.5     .12       0  3263.4     .05       0
  4728.6     .12       0  4824.8     .05       0  4862.9     .12       0
  4930.4     .12       0  4981.1     .12       0  5125.3     .07       0
  5313.5    .035       0  5615.5     .05       0
Bank Sta=4824.8,4862.9
XS Rating Curve= 0 ,0
Exp/Cntr=0.3,0.1

Type RM Length L Ch R = 1 ,8413    ,555,555,555
BEGIN DESCRIPTION:
SHOATS CREEK 6.0
END DESCRIPTION:
XS GIS Cut Line= 3
      2446575.03     13598125.03        2444175.       13595725.
      2442575.04       13595775.
#Sta/Elev= 30
  1610.2  320.52  1619.7   320.2  1689.2  317.13    1776  312.65  1864.8   305.3
  1963.8  302.28  2128.1  291.76    2263  285.52    2296  284.02  2531.3  276.16
    2581  274.08  2972.2  263.79  3307.3  260.32  4226.5  260.46  4595.2  257.14
  4701.9   253.2    4759  247.14    4760  246.64  4797.2  247.14  4820.5  251.37
  4865.7  253.24  4988.8  252.14  5214.5  256.64  5374.5  257.05  5434.6  260.25
  5664.7  258.39  6014.8  263.19    6255  270.18    6315  275.43  6605.1  292.64
#Mann= 16 ,-1 , 0
  1610.2     .05       0  1619.7    .035       0  1689.2     .05       0
    1776    .035       0  2128.1     .05       0    2263    .035       0
    2296     .05       0  2531.3    .035       0    2581     .12       0
  2972.2     .05       0  4595.2     .12       0  4701.9     .12       0
    4759     .05       0  4797.2     .12       0  4865.7     .07       0
  4988.8     .05       0
Bank Sta=4759,4797.2
XS Rating Curve= 0 ,0
Exp/Cntr=0.3,0.1

Type RM Length L Ch R = 1 ,7858    ,586,586,586
BEGIN DESCRIPTION:
SHOATS CREEK 5.0
END DESCRIPTION:
XS GIS Cut Line= 3
      2447024.99       13597225.        2444625.       13595425.
      2442984.53     13595221.77
#Sta/Elev= 30
  1988.4   330.2  2231.1  311.71  2316.5  301.33  2338.4  302.79  2524.9  285.89
  2795.7  272.75  3074.9  264.71  3416.5   259.6  3801.9  255.87  4066.5  259.26
  4171.8  258.15  4501.9  254.72  4660.3  256.96  4766.5  251.98  4881.1  252.85
  4951.9  248.43  4978.8  246.28  4979.8  245.78  5018.1  246.28  5018.6  248.05
  5031.4     250  5132.8  254.24  5489.7  258.49  5734.9  259.72  5824.2  259.86
  6137.1   261.2  6170.1  263.85  6399.1  265.61  6606.2  273.27  6641.4  275.26
#Mann= 10 ,-1 , 0
  1988.4     .05       0  4171.8     .07       0  4951.9     .12       0
  4978.8     .05       0  5018.1     .12       0  5132.8    .035       0
  5489.7     .05       0  5734.9    .035       0  5824.2     .05       0
  6606.2     .07       0
Bank Sta=4978.8,5018.1
XS Rating Curve= 0 ,0
Exp/Cntr=0.3,0.1

Type RM Length L Ch R = 1 ,7272    ,566,566,566
BEGIN DESCRIPTION:
SHOATS CREEK 4.0
END DESCRIPTION:
XS GIS Cut Line= 3
      2446674.97     13596774.97        2445125.       13595225.
      2444324.97     13594424.97
#Sta/Elev= 30
    2808  289.68  3034.2  277.71  3062.5  274.53  3076.7  275.84  3133.2  272.31
  3387.8  264.66  3840.3  256.06  4229.4  254.15  4420.2  255.65  4490.9  253.41
  4844.4  256.29  4858.6  255.91    4886  250.25  4895.5  244.75  4896.5  244.25
  4934.8  244.75  4943.4  247.67  4996.5   250.4  5084.8  252.11  5141.4  250.49
  5169.7  252.39  5222.5  252.41  5282.8  251.84    5594  256.33  5777.8  260.99
  5820.2  264.43  5835.7  264.04  5988.9  270.63  6018.2  272.92  6131.4  275.93
#Mann= 8 ,-1 , 0
    2808     .05       0  4229.4     .07       0    4886     .12       0
  4895.5     .05       0  4934.8     .12       0  5222.5     .07       0
  5835.7     .05       0  5988.9     .07       0
Bank Sta=4895.5,4934.8
XS Rating Curve= 0 ,0
Exp/Cntr=0.3,0.1

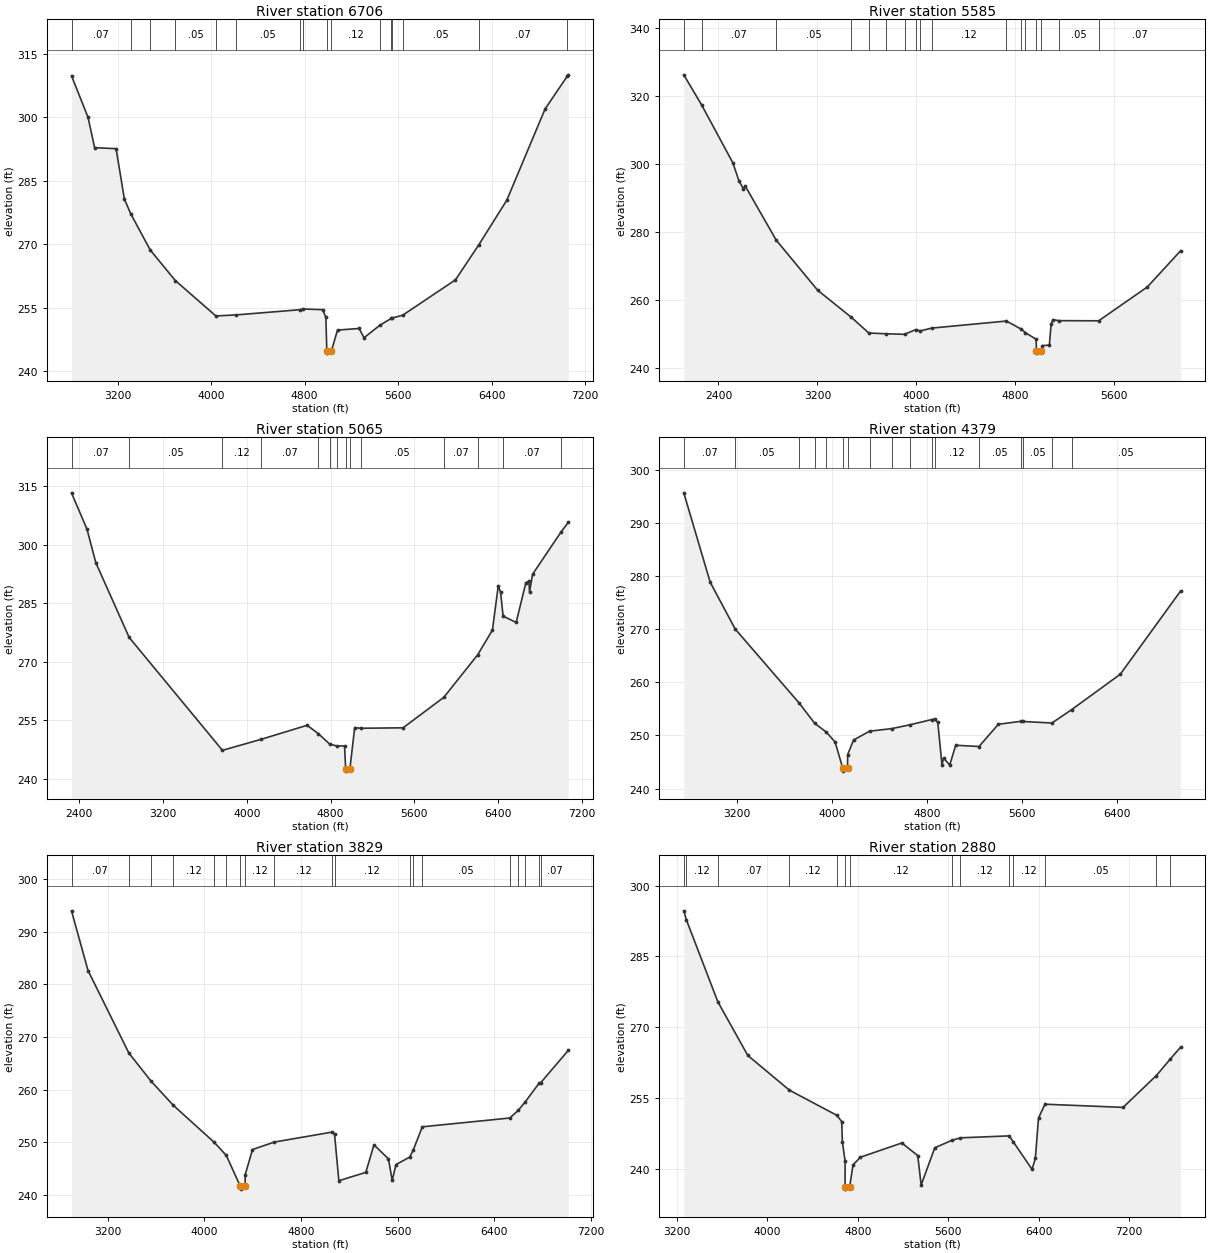
Type RM Length L Ch R = 1 ,6706    ,1121,1121,1121
BEGIN DESCRIPTION:
SHOATS CREEK 3.0
END DESCRIPTION:
XS GIS Cut Line= 3
      2447074.97     13596474.97        2445525.       13594925.
      2443925.03     13593625.03
#Sta/Elev= 30
  2803.7  309.76  2945.1  299.95  3001.6  292.78  3185.5  292.54  3256.2  280.66
  3311.1  277.16  3477.5  268.62  3692.2  261.41  4039.7  253.04  4210.7  253.28
  4763.3  254.52  4788.2  254.67  4953.3  254.53  4981.5  252.76  4989.7  244.76
  4990.7  244.26    5029  244.76  5081.2  249.71  5266.3  250.08  5308.1  247.89
  5442.1   250.8  5543.1   252.5  5548.8  252.54  5639.8  253.22  6090.9  261.56
    6290   269.8  6530.7  280.37  6858.3  301.91    7048  309.65  7057.2  309.98
#Mann= 16 ,-1 , 0
  2803.7     .07       0  3311.1     .05       0  3477.5    .035       0
  3692.2     .05       0  4039.7     .07       0  4210.7     .05       0
  4763.3     .07       0  4788.2     .12       0  4989.7     .05       0
    5029     .12       0  5442.1     .07       0  5543.1     .12       0
  5548.8     .07       0  5639.8     .05       0    6290     .07       0
    7048     .05       0
Bank Sta=4989.7,5029
XS Rating Curve= 0 ,0
Exp/Cntr=0.3,0.1

Type RM Length L Ch R = 1 ,5585    ,520,520,520
BEGIN DESCRIPTION:
SHOATS CREEK 2.0
END DESCRIPTION:
XS GIS Cut Line= 3
      2447324.98     13596574.97        2445725.       13594175.
      2444924.98     13593374.98
#Sta/Elev= 30
  2119.9  326.18  2263.6  317.36  2516.5  300.32  2566.1  294.99  2602.1  292.65
  2617.1  293.47    2867  277.58  3201.5  262.88  3474.5  254.89  3615.9  250.28
    3753  250.06    3905   249.9  3996.4  251.31  4031.8  250.91  4124.2  251.73
  4727.9   253.8  4848.6  251.41    4882  250.35  4968.3  248.45    4971  244.87
    4972  244.37  5010.5  244.87  5018.4  246.57    5075  246.73  5089.2  252.86
  5103.3  254.23  5150.4  253.92  5473.5  253.87    5867  263.82  6135.7  274.45
#Mann= 17 ,-1 , 0
  2119.9     .05       0  2263.6     .07       0    2867     .05       0
  3474.5     .07       0  3615.9     .05       0    3753     .12       0
    3905     .07       0  3996.4     .12       0  4031.8     .07       0
  4124.2     .12       0  4727.9     .07       0  4848.6     .12       0
    4882     .12       0    4971     .05       0  5010.5     .12       0
  5150.4     .05       0  5473.5     .07       0
Bank Sta=4971,5010.5
XS Rating Curve= 0 ,0
Exp/Cntr=0.3,0.1

Type RM Length L Ch R = 1 ,5065    ,686,686,686
BEGIN DESCRIPTION:
SHOATS CREEK 1.0
END DESCRIPTION:
XS GIS Cut Line= 3
      2447324.98     13596324.96        2446125.       13593925.
        2444525.       13592625.
#Sta/Elev= 30
    2326  313.32  2474.1  303.98    2558  295.43  2876.7  276.26  3767.4  247.33
  4134.6  250.13    4576  253.75  4682.3  251.63  4792.1  248.93  4858.3  248.46
  4933.8  248.45  4944.8   242.5  4945.8     242  4984.3   242.5  5030.8  253.15
  5088.8  252.99  5492.7   253.1  5882.2  260.92  6205.5  271.82    6346  278.13
    6402  289.48  6424.3  287.81  6448.2  281.72    6573  280.11  6665.7  290.31
  6694.4  290.64  6700.9  287.87  6729.6  292.45  6999.6  303.21  7070.8  305.76
#Mann= 14 ,-1 , 0
    2326     .07       0  2876.7     .05       0  3767.4     .12       0
  4134.6     .07       0  4682.3     .12       0  4792.1     .07       0
  4858.3     .12       0  4944.8     .05       0  4984.3     .12       0
  5088.8     .05       0  5882.2     .07       0  6205.5     .05       0
  6448.2     .07       0  6999.6     .05       0
Bank Sta=4944.8,4984.3
XS Rating Curve= 0 ,0
Exp/Cntr=0.3,0.1

Type RM Length L Ch R = 1 ,4379    ,550,550,550
BEGIN DESCRIPTION:
E20806
END DESCRIPTION:
XS GIS Cut Line= 3
      2447316.16     13596077.29      2446691.85     13593718.79
      2445489.76     13592462.76
#Sta/Elev= 30
  2755.9  295.63    2978  278.81  3188.3  270.01  3726.5  256.08  3857.1  252.27
  3953.1  250.66    4028  248.78  4093.8  243.78  4094.8  243.28  4133.3  243.78
  4134.1  246.37  4183.7  249.13  4318.3  250.79  4505.7  251.28  4661.5  252.01
  4840.7  252.98  4866.9  253.06  4892.3  252.43  4927.4  244.46  4940.9  245.74
  4992.7  244.43  5042.9  248.15  5239.1  247.91  5401.2  252.09  5588.2  252.64
  5606.9  252.62  5852.3  252.33  6018.3  254.85  6426.8   261.5  6934.2  277.16
#Mann= 17 ,-1 , 0
  2755.9     .07       0  3188.3     .05       0  3726.5     .12       0
  3857.1     .07       0  3953.1     .12       0  4093.8     .05       0
  4133.3     .12       0  4318.3     .07       0  4505.7     .12       0
  4661.5     .12       0  4840.7     .07       0  4866.9     .12       0
  5239.1     .05       0  5588.2     .12       0  5606.9     .05       0
  5852.3     .07       0  6018.3     .05       0
Bank Sta=4093.8,4133.3
XS Rating Curve= 0 ,0
Exp/Cntr=0.3,0.1

Type RM Length L Ch R = 1 ,3829    ,949,949,949
BEGIN DESCRIPTION:
E20805
END DESCRIPTION:
XS GIS Cut Line= 4
      2447393.24     13596015.64      2447169.72     13593711.08
      2446915.37     13592971.16      2446168.87     13592286.22
#Sta/Elev= 30
  2900.6  293.96  3037.3  282.62  3375.3  266.94  3559.7  261.58  3742.3  257.03
  4082.5  249.96  4181.7  247.49  4298.1  241.59  4299.1  241.09  4337.6  241.59
    4338  243.84  4398.2  248.61  4578.8  250.03  5060.1  251.94  5077.2  251.51
    5113  242.69  5335.8  244.27  5403.6  249.51  5523.2  246.84  5554.5  242.74
  5585.7  245.76  5698.2  247.16    5728  248.48  5803.4  252.93  6528.2   254.6
  6597.1  256.06    6653   257.6  6772.8   261.3  6783.1   261.3  7011.5  267.45
#Mann= 19 ,-1 , 0
  2900.6     .07       0  3375.3     .05       0  3559.7     .07       0
  3742.3     .12       0  4082.5     .07       0  4181.7     .12       0
  4298.1     .05       0  4337.6     .12       0  4578.8     .12       0
  5060.1     .12       0  5077.2     .12       0  5698.2     .12       0
    5728     .07       0  5803.4     .05       0  6528.2     .12       0
  6597.1     .05       0    6653     .07       0  6772.8    .035       0
  6783.1     .07       0
Bank Sta=4298.1,4337.6
XS Rating Curve= 0 ,0
Exp/Cntr=0.3,0.1

Type RM Length L Ch R = 1 ,2880    ,771,771,771
BEGIN DESCRIPTION:
E20804
END DESCRIPTION:
XS GIS Cut Line= 5
      2447593.63     13596031.06      2447616.76     13594628.28
      2447709.25      13593526.1      2447400.94     13593210.09
      2446268.96     13592316.82
#Sta/Elev= 30
  3262.4  294.66    3286  292.71    3563  275.41  3828.5  264.02  4196.6  256.66
  4616.2  251.33  4658.7  250.01  4664.5  245.76  4688.7  241.63  4688.9   236.2
  4689.9   235.7  4729.1   236.2    4759  240.85    4824  242.46  5190.5  245.48
    5331  242.81  5361.1  236.57  5481.5  244.46  5633.4  246.04  5708.5  246.57
  6138.6  246.98  6173.7  245.79  6341.9  239.89  6370.7  242.21  6398.8  250.77
  6455.6  253.69  7146.7  253.02  7440.4  259.75  7565.5   263.3  7654.9  265.77
#Mann= 14 ,-1 , 0
  3262.4     .07       0    3286     .12       0    3563     .07       0
  4196.6     .12       0  4616.2     .12       0  4688.9     .05       0
  4729.1     .12       0  5633.4     .12       0  5708.5     .12       0
  6138.6     .12       0  6173.7     .12       0  6455.6     .05       0
  7440.4    .035       0  7565.5     .07       0
Bank Sta=4688.9,4729.1
XS Rating Curve= 0 ,0
Exp/Cntr=0.3,0.1

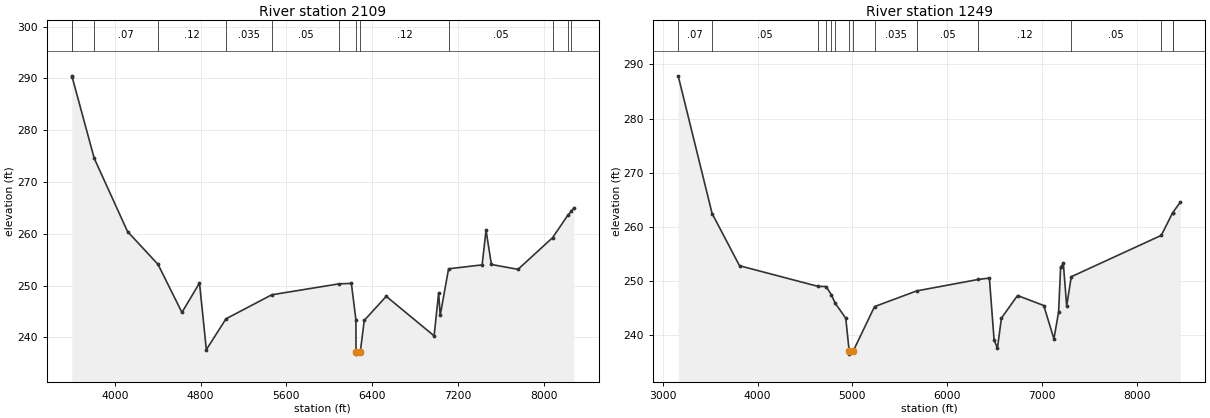
Type RM Length L Ch R = 1 ,2109    ,860,860,860
BEGIN DESCRIPTION:
E20803
END DESCRIPTION:
XS GIS Cut Line= 5
      2447724.66     13596023.34       2448271.9     13594535.79
      2448279.61     13594073.34       2447462.6      13593217.8
      2446321.91     13592316.03
#Sta/Elev= 30
  3598.4  290.49  3600.9  290.34  3807.9  274.56  4118.7  260.42  4403.5  254.07
  4626.2   244.8    4790  250.48  4853.9  237.61    5037  243.57  5464.4  248.21
  6091.4  250.32  6206.9  250.41  6249.3  243.39  6250.3  237.25  6251.3  236.75
  6290.5  237.25    6327  243.26  6532.1  247.91  6978.8  240.28  7021.2  248.61
  7035.6  244.23  7113.8  253.23  7426.7  253.98  7463.2  260.67  7513.3  254.06
  7761.7  253.12  8083.8  259.23  8228.8  263.64  8259.5  264.31    8283  265.01
#Mann= 13 ,-1 , 0
  3598.4     .07       0  3600.9     .12       0  3807.9     .07       0
  4403.5     .12       0    5037    .035       0  5464.4     .05       0
  6091.4     .12       0  6250.3     .05       0  6290.5     .12       0
  7113.8     .05       0  8083.8    .035       0  8228.8     .07       0
  8259.5    .035       0
Bank Sta=6250.3,6290.5
XS Rating Curve= 0 ,0
Exp/Cntr=0.3,0.1

Type RM Length L Ch R = 1 ,1249    ,0,0,0
BEGIN DESCRIPTION:
E20802
END DESCRIPTION:
XS GIS Cut Line= 4
      2449281.59     13596416.44      2449058.07     13594844.09
      2447501.14     13593202.38      2446375.83     13592300.59
#Sta/Elev= 30
  3163.2   287.9  3520.7  262.46    3810  252.81  4637.2     249  4722.4  248.97
  4777.2  247.47  4817.4  245.91  4929.6  243.12    4966  236.98    4967  236.48
  5006.4  236.98  5232.8  245.26    5677  248.16  6327.6  250.28  6443.6  250.53
    6493  239.13  6528.2  237.58  6570.6  243.14  6740.5  247.31  7016.6  245.46
  7123.8   239.3  7173.4  244.31  7194.2  252.58    7223  253.23  7258.2  245.38
  7306.7  250.78  8255.3  258.42  8375.1  262.59  8376.2  262.62    8456  264.55
#Mann= 15 ,-1 , 0
  3163.2     .07       0  3520.7     .05       0  4637.2     .07       0
  4722.4     .05       0  4777.2     .07       0  4817.4     .12       0
    4966     .05       0  5006.4     .12       0  5232.8    .035       0
    5677     .05       0  6327.6     .12       0  7306.7     .05       0
  8255.3    .035       0  8375.1     .05       0  8376.2     .07       0
Bank Sta=4966,5006.4
XS Rating Curve= 0 ,0
Exp/Cntr=0.3,0.1

Chan Stop Cuts=-1
Use User Specified Reach Order=0
Composite Channel Slope=5