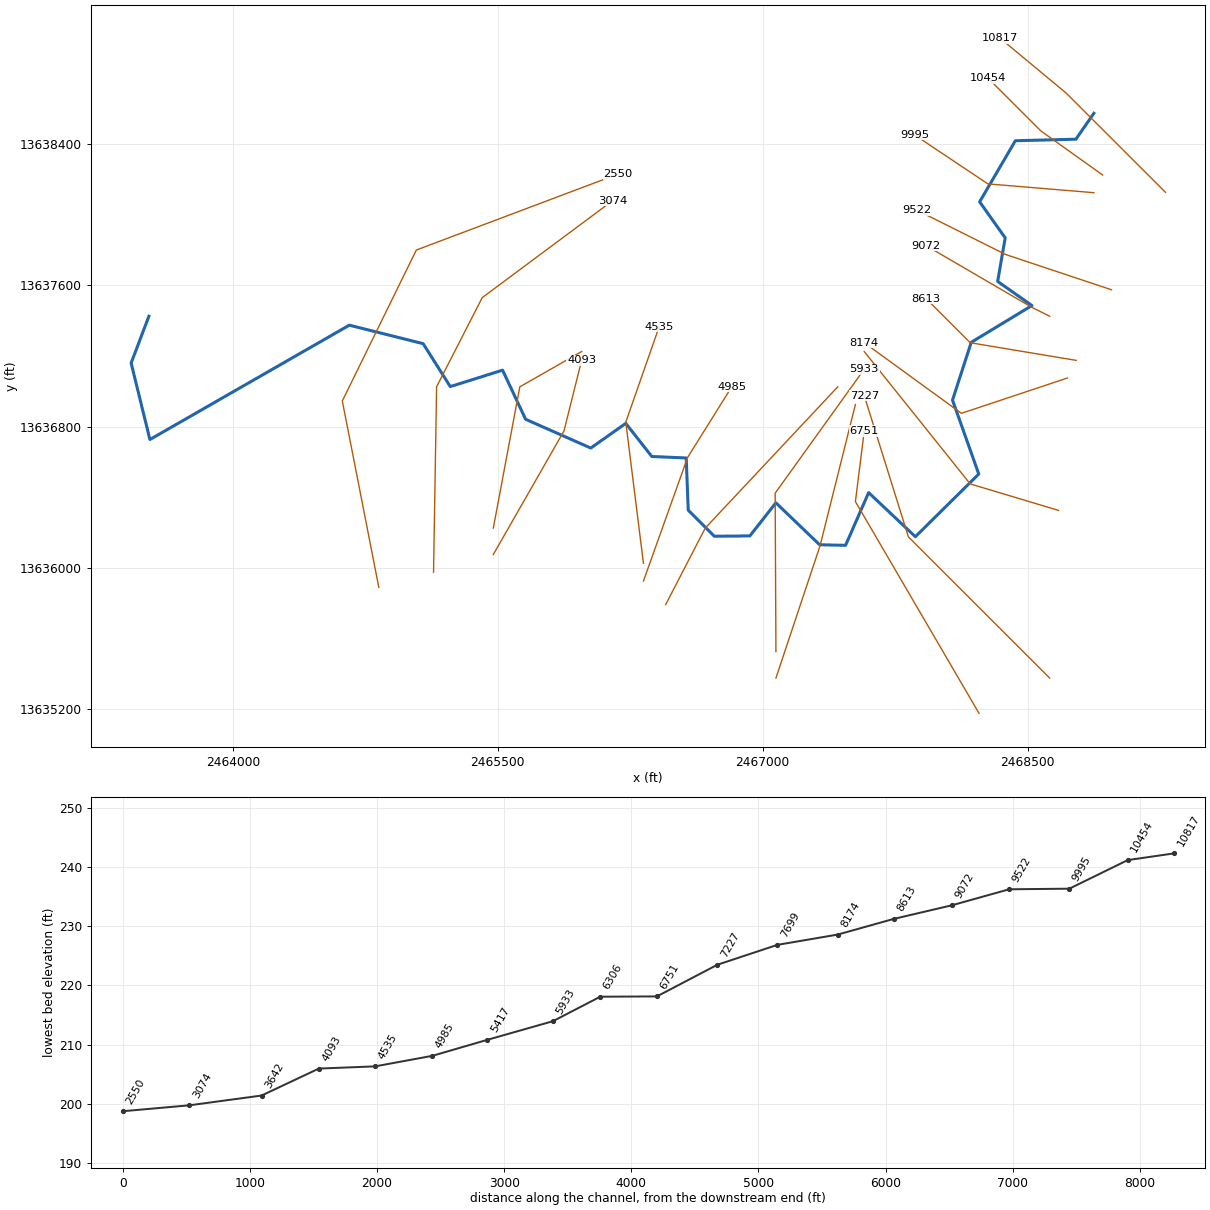
--- Stream0759.prj (project) ---

Proj Title=Stream0759 Base Level Engineering
Current Plan=p01
Default Exp/Contr=0.3,0.1
English Units
Geom File=g01
Flow File=f01
Plan File=p01
BEGIN DESCRIPTION:
Stream0759
END DESCRIPTION:

--- Stream0759.p01 (plan) ---

Plan Title=Multiple Run
Short Identifier=Multiple
Geom File=g01
Flow File=f01
Subcritical Flow
K Sum by GR= 0
Std Step Tol= 0.01
Critical Tol= 0.01
Num of Std Step Trials= 20
Max Error Tol= 0.3
Flow Tol Ratio= 0.001
Split Flow NTrial= 30
Split Flow Tol= 0.02
Split Flow Ratio= 0.02
Log Output Level= 0
Friction Slope Method= 1
Unsteady Friction Slope Method= 2
Unsteady Bridges Friction Slope Method= 1
Parabolic Critical Depth
Global Vel Dist=  1 , 1 , 1
Global Log Level= 0
CheckData=True
Encroach Param= -1, 0, 0, 0
BEGIN DESCRIPTION:
Multiple Run
END DESCRIPTION:

--- Stream0759.f01 (steady flow) ---

Flow Title=Multiple
Number of Profiles=7
Profile Names=10-year,25-year,50-year,1pct_min,100-year,1pct_plu,500-year
River Rch & RM= Stream0759,Reach-1,10817
     864    1418    1928    1269    2533    5053    4328
River Rch & RM= Stream0759,Reach-1,7699
    1092    1805    2464    1627    3245    6476    5577
Boundary for River Rch & Prof#=Stream0759,Reach-1,1
Up Type=0
Dn Type=3
Dn Slope=0.005
Boundary for River Rch & Prof#=Stream0759,Reach-1,2
Up Type=0
Dn Type=3
Dn Slope=0.005
Boundary for River Rch & Prof#=Stream0759,Reach-1,3
Up Type=0
Dn Type=3
Dn Slope=0.005
Boundary for River Rch & Prof#=Stream0759,Reach-1,4
Up Type=0
Dn Type=3
Dn Slope=0.005
Boundary for River Rch & Prof#=Stream0759,Reach-1,5
Up Type=0
Dn Type=3
Dn Slope=0.005
Boundary for River Rch & Prof#=Stream0759,Reach-1,6
Up Type=0
Dn Type=3
Dn Slope=0.005
Boundary for River Rch & Prof#=Stream0759,Reach-1,7
Up Type=0
Dn Type=3
Dn Slope=0.005

--- Stream0759.g01 (geometry) ---

Geom Title=Existing Conditions

River Reach=Stream0759,Reach-1
Reach XY= 30
      2468875.00     13638575.00      2468773.38     13638428.11
      2468430.61     13638419.41      2468228.31     13638073.26
      2468373.04     13637869.11      2468330.28     13637622.29
      2468524.47     13637485.69      2468180.83     13637277.33
      2468074.76     13636949.91      2468223.38     13636531.03
      2467864.51     13636175.93      2467599.91     13636425.63
      2467469.16     13636127.05      2467322.30     13636130.35
      2467074.78     13636368.01      2466927.47     13636180.45
      2466726.46     13636178.53      2466578.54     13636326.46
      2466567.09     13636622.09      2466372.30     13636630.36
      2466225.01     13636817.93      2466026.74     13636678.31
      2465657.87     13636841.20      2465527.47     13637119.55
      2465231.42     13637026.42      2465077.74     13637269.66
      2464659.78     13637374.50      2463530.80     13636726.54
      2463424.53     13637159.84      2463525.00     13637425.00

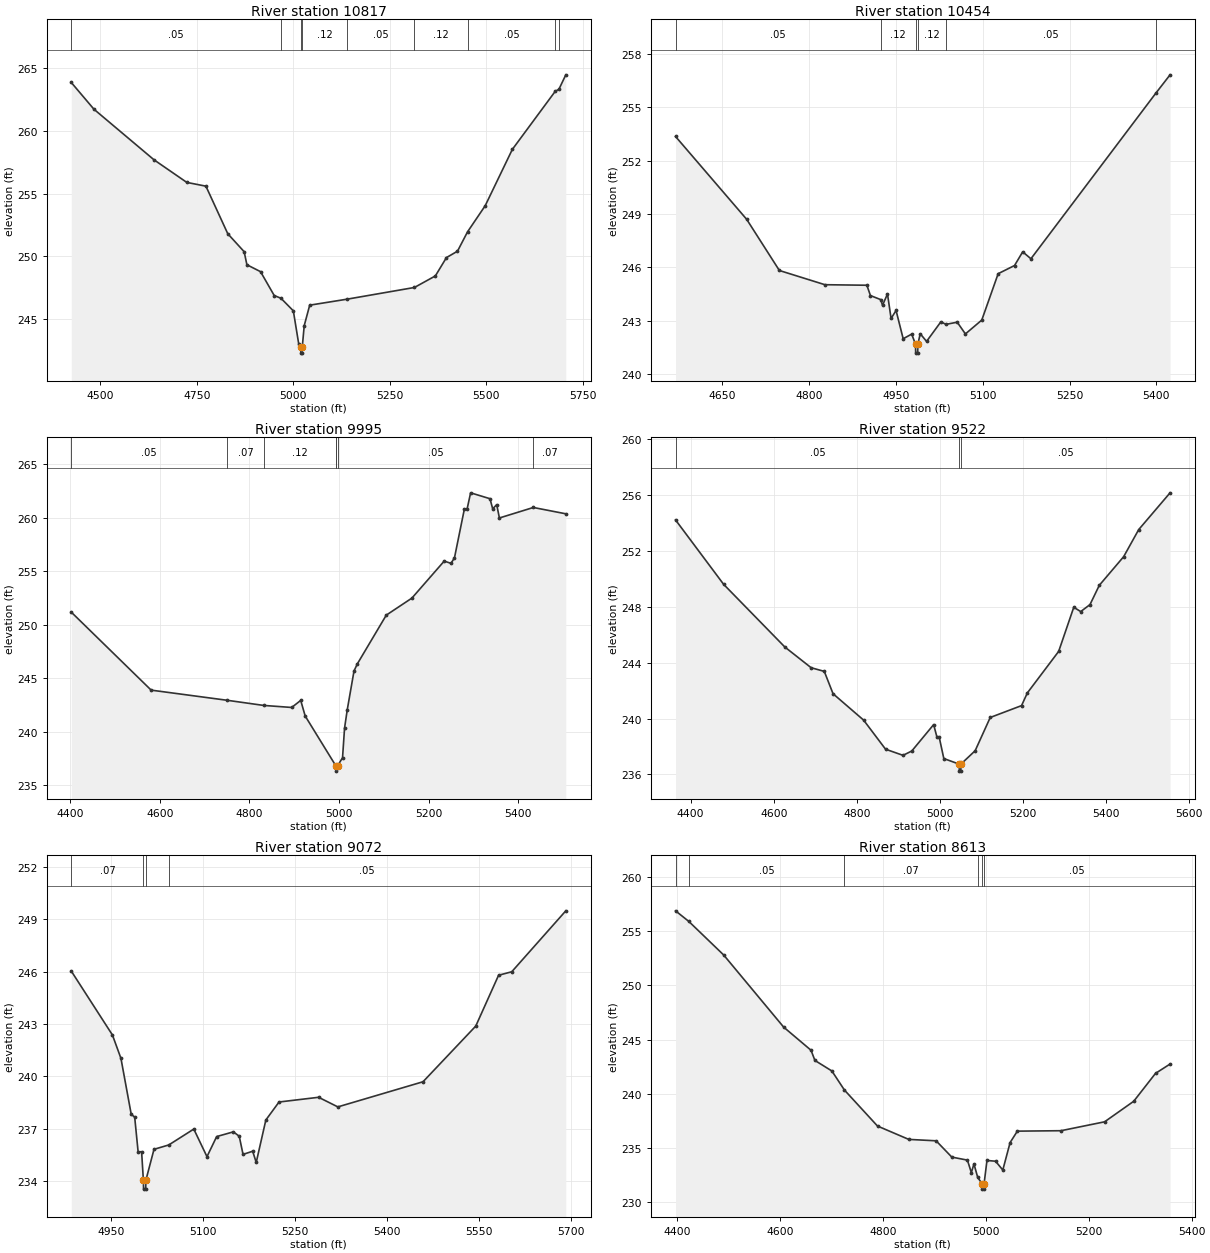
Type RM Length L Ch R = 1,10817,363,363,363
BEGIN DESCRIPTION:
XS7672
END DESCRIPTION:
XS GIS Cut Line= 3
      2469280.27     13638127.29      2468717.87     13638689.70
      2468344.86     13638999.58
#Sta/Elev= 30
  4425.2  263.86  4483.9  261.73  4639.4  257.70  4724.3  255.90  4773.8  255.60
  4830.4  251.81  4872.8  250.38  4879.9  249.34  4915.2  248.79  4950.6  246.89
  4968.1  246.67  5000.1  245.67  5014.2  243.01  5019.3  242.80  5019.5  242.30
  5023.0  242.30  5023.3  242.80  5028.3  244.49  5042.5  246.12  5139.7  246.60
  5313.6  247.53  5367.8  248.45  5396.5  249.91  5425.1  250.42  5451.1  251.96
  5496.8  254.04  5567.1  258.53  5678.0  263.15  5687.7  263.32  5705.5  264.47
#Mann=9,-1,0
  4425.2    0.05       0  4968.1    0.12       0  5019.3    0.05       0
  5023.3    0.12       0  5139.7    0.05       0  5313.6    0.12       0
  5451.1    0.05       0  5678.0    0.07       0  5687.7    0.05       0
Bank Sta=5019.3,5023.3
Exp/Cntr=0.3,0.1

Type RM Length L Ch R = 1,10454,459,459,459
BEGIN DESCRIPTION:
Stream0759 19.0
END DESCRIPTION:
XS GIS Cut Line= 3
      2468925.01     13638225.00      2468575.00     13638475.00
      2468274.99     13638775.01
#Sta/Elev= 30
  4569.2  253.36  4692.1  248.70  4748.6  245.82  4827.3  245.02  4899.8  244.99
  4905.9  244.41  4923.8  244.18  4926.8  243.86  4935.4  244.50  4941.6  243.12
  4950.2  243.57  4962.5  241.98  4977.2  242.24  4983.8  241.67  4984.1  241.17
  4987.6  241.17  4987.8  241.67  4992.0  242.26  5002.9  241.83  5027.6  242.93
  5036.5  242.79  5055.9  242.91  5070.0  242.25  5098.3  243.03  5126.6  245.64
  5154.9  246.10  5169.0  246.87  5183.2  246.48  5398.6  255.78  5423.6  256.83
#Mann=6,-1,0
  4569.2    0.05       0  4923.8    0.12       0  4983.8    0.05       0
  4987.8    0.12       0  5036.5    0.05       0  5398.6    0.07       0
Bank Sta=4983.8,4987.8
Exp/Cntr=0.3,0.1

Type RM Length L Ch R = 1,9995,473,473,473
BEGIN DESCRIPTION:
Stream0759 18.0
END DESCRIPTION:
XS GIS Cut Line= 3
      2468875.04     13638125.00      2468275.00     13638175.00
      2467858.49     13638453.39
#Sta/Elev= 30
  4402.7  251.20  4580.9  243.91  4750.7  242.96  4831.9  242.48  4894.4  242.29
  4914.5  242.95  4924.5  241.49  4992.2  236.88  4992.8  236.84  4993.0  236.34
  4996.8  236.84  5007.8  237.59  5012.3  240.36  5018.3  242.07  5033.4  245.70
  5040.9  246.37  5105.4  250.92  5162.5  252.51  5234.6  255.97  5249.6  255.76
  5257.4  256.26  5279.6  260.84  5285.6  260.83  5293.5  262.35  5336.7  261.80
  5342.7  260.86  5351.7  261.24  5357.7  260.00  5433.4  260.98  5505.8  260.39
#Mann=7,-1,0
  4402.7    0.05       0  4750.7    0.07       0  4831.9    0.12       0
  4992.2    0.05       0  4992.8    0.05       0  4996.8    0.05       0
  5433.4    0.07       0
Bank Sta=4992.8,4996.8
Exp/Cntr=0.3,0.1

Type RM Length L Ch R = 1,9522,450,450,450
BEGIN DESCRIPTION:
Stream0759 17.0
END DESCRIPTION:
XS GIS Cut Line= 3
      2468974.99     13637575.00      2468375.00     13637775.00
      2467874.96     13638025.02
#Sta/Elev= 30
  4363.5  254.22  4479.4  249.61  4627.0  245.12  4690.3  243.64  4721.9  243.38
  4743.0  241.78  4816.7  239.89  4869.5  237.81  4911.6  237.37  4932.7  237.68
  4985.4  239.57  4993.3  238.68  4998.7  238.68  5009.9  237.14  5047.0  236.74
  5047.3  236.24  5050.8  236.24  5051.0  236.74  5085.4  237.70  5121.7  240.08
  5197.2  240.93  5211.2  241.84  5286.6  244.81  5323.0  247.97  5339.7  247.66
  5362.1  248.16  5384.5  249.54  5443.2  251.59  5479.5  253.53  5555.0  256.16
#Mann=3,-1,0
  4363.5    0.05       0  5047.0    0.05       0  5051.0    0.05       0
Bank Sta=5047,5051
Exp/Cntr=0.3,0.1

Type RM Length L Ch R = 1,9072,459,459,459
BEGIN DESCRIPTION:
Stream0759 16.0
END DESCRIPTION:
XS GIS Cut Line= 3
      2468624.97     13637425.01      2468525.00     13637475.00
      2467924.99     13637825.00
#Sta/Elev= 30
  4884.7  246.03  4951.8  242.37  4965.7  241.03  4982.5  237.82  4988.1  237.67
  4993.7  235.68  4999.4  235.68  5002.3  234.04  5002.6  233.54  5006.1  233.54
  5006.3  234.04  5019.6  235.82  5043.7  236.07  5084.5  236.98  5106.0  235.40
  5121.8  236.55  5149.0  236.82  5158.6  236.57  5164.8  235.53  5180.5  235.71
  5186.3  235.07  5202.0  237.50  5223.5  238.53  5288.0  238.80  5319.4  238.25
  5458.3  239.69  5544.3  242.88  5581.5  245.79  5603.0  245.99  5691.1  249.48
#Mann=4,-1,0
  4884.7    0.07       0  5002.3    0.05       0  5006.3    0.07       0
  5043.7    0.05       0
Bank Sta=5002.3,5006.3
Exp/Cntr=0.3,0.1

Type RM Length L Ch R = 1,8613,439,439,439
BEGIN DESCRIPTION:
Stream0759 15.0
END DESCRIPTION:
XS GIS Cut Line= 3
      2468774.95     13637175.01      2468175.00     13637275.00
      2467924.99     13637525.01
#Sta/Elev= 30
  4396.2  256.86  4421.9  255.89  4489.9  252.79  4606.5  246.15  4659.7  244.02
  4667.3  243.08  4700.3  242.11  4724.6  240.36  4789.0  237.04  4849.8  235.81
  4903.0  235.68  4933.5  234.18  4963.9  233.90  4971.5  232.75  4976.6  233.55
  4983.9  232.31  4992.3  231.73  4992.5  231.23  4996.0  231.23  4996.3  231.73
  5001.9  233.87  5018.6  233.80  5032.7  232.99  5046.9  235.52  5061.0  236.57
  5145.9  236.61  5230.7  237.43  5287.3  239.32  5329.7  241.89  5358.0  242.75
#Mann=6,-1,0
  4396.2   0.035       0  4421.9    0.05       0  4724.6    0.07       0
  4983.9    0.05       0  4992.3    0.05       0  4996.3    0.05       0
Bank Sta=4992.3,4996.3
Exp/Cntr=0.3,0.1

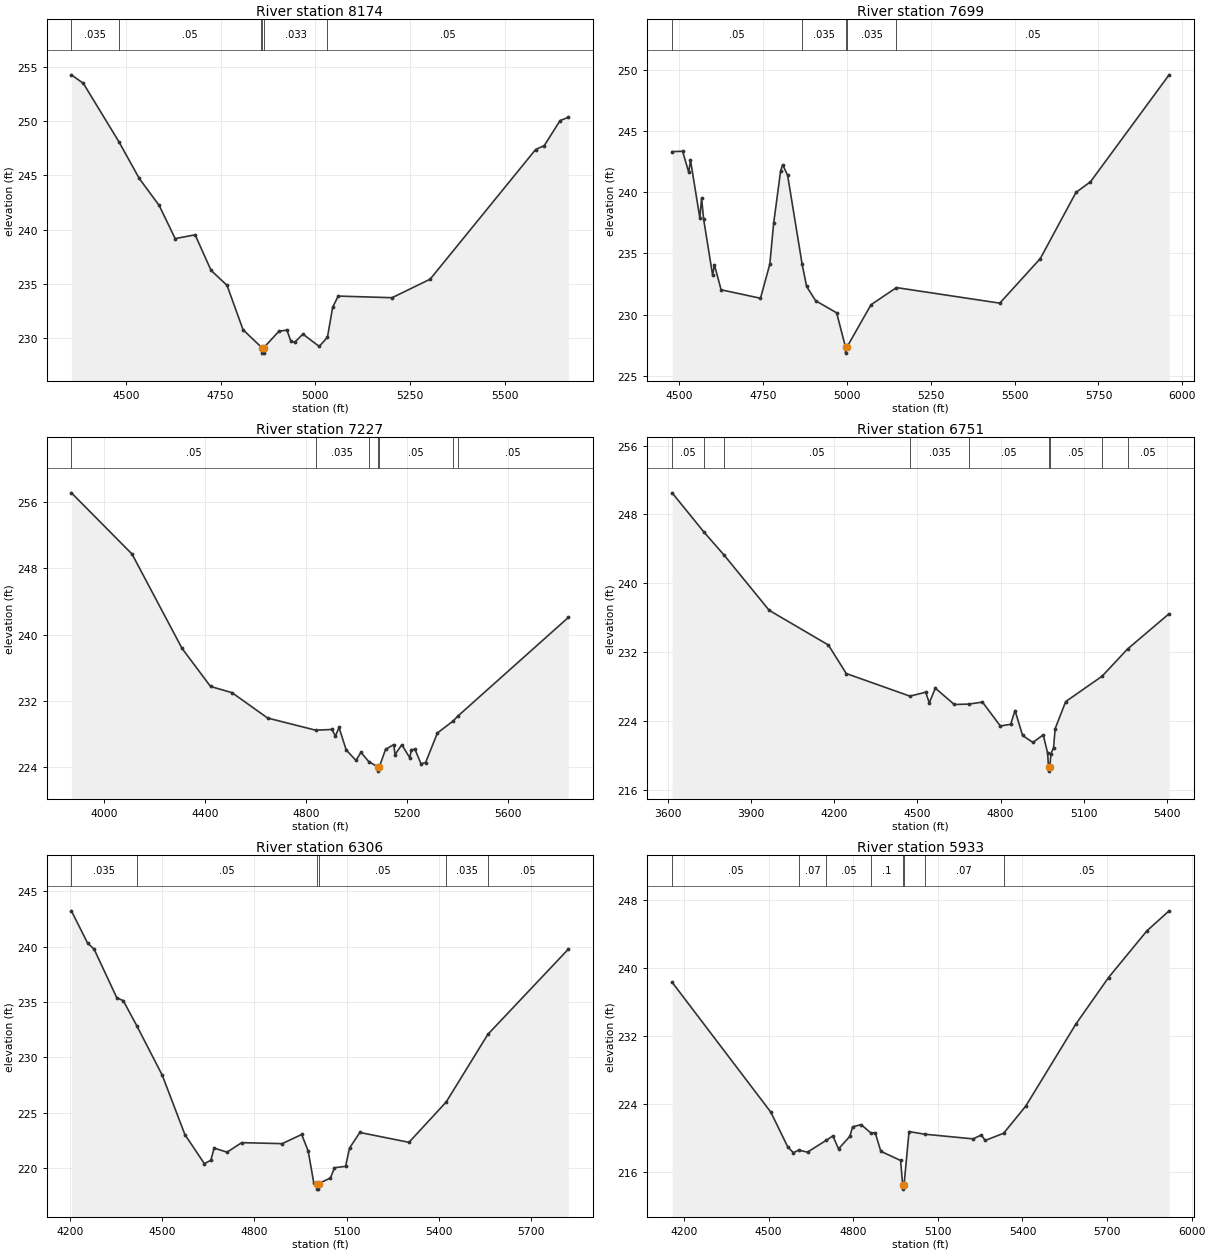
Type RM Length L Ch R = 1,8174,475,475,475
BEGIN DESCRIPTION:
Stream0759 14.0
END DESCRIPTION:
XS GIS Cut Line= 3
      2468725.02     13637075.01      2468125.00     13636875.00
      2467575.04     13637274.97
#Sta/Elev= 30
  4355.8  254.30  4387.4  253.51  4481.6  248.10  4535.0  244.73  4587.7  242.23
  4629.9  239.17  4682.6  239.52  4724.7  236.23  4766.9  234.85  4809.1  230.75
  4856.6  229.17  4859.8  229.09  4860.0  228.59  4863.5  228.59  4863.8  229.09
  4903.9  230.61  4925.0  230.72  4935.6  229.67  4946.1  229.61  4967.2  230.35
  5010.3  229.21  5032.0  230.05  5045.8  232.83  5060.5  233.86  5202.7  233.71
  5303.2  235.42  5581.8  247.40  5604.6  247.76  5646.3  250.07  5668.3  250.38
#Mann=6,-1,0
  4355.8   0.035       0  4481.6    0.05       0  4856.6   0.033       0
  4859.8   0.033       0  4863.8   0.033       0  5032.0    0.05       0
Bank Sta=4859.8,4863.8
Exp/Cntr=0.3,0.1

Type RM Length L Ch R = 1,7699,472,472,472
BEGIN DESCRIPTION:
Stream0759 13.0
END DESCRIPTION:
XS GIS Cut Line= 3
      2468674.98     13636325.00      2468175.00     13636475.00
      2467574.98     13637225.02
#Sta/Elev= 30
  4478.3  243.30  4509.6  243.33  4527.9  241.61  4533.1  242.61  4560.9  237.89
  4566.2  239.52  4572.2  237.80  4599.2  233.20  4604.4  234.07  4624.4  232.02
  4741.9  231.33  4769.7  234.11  4781.1  237.44  4801.9  241.72  4808.0  242.23
  4822.8  241.37  4866.1  234.11  4879.4  232.30  4906.3  231.13  4969.0  230.14
  4995.5  227.35  4995.8  226.85  4999.9  227.35  5071.5  230.80  5147.5  232.20
  5455.7  230.93  5576.6  234.57  5683.0  239.97  5726.3  240.84  5960.8  249.57
#Mann=5,-1,0
  4478.3    0.05       0  4866.1   0.035       0  4995.5   0.035       0
  4999.9   0.035       0  5147.5    0.05       0
Bank Sta=4995.5,4999.9
Exp/Cntr=0.3,0.1

Type RM Length L Ch R = 1,7227,476,476,476
BEGIN DESCRIPTION:
Stream0759 12.0
END DESCRIPTION:
XS GIS Cut Line= 3
      2468624.99     13635375.01      2467825.00     13636175.00
      2467575.00     13636974.99
#Sta/Elev= 30
  3869.9  257.15  4110.3  249.74  4308.3  238.34  4421.4  233.73  4506.3  232.98
  4647.7  229.91  4838.1  228.44  4902.3  228.53  4916.4  227.73  4930.5  228.78
  4958.8  226.06  4997.7  224.78  5017.5  225.76  5048.4  224.64  5085.3  223.99
  5085.6  223.49  5090.1  223.99  5114.9  226.12  5147.4  226.70  5152.6  225.49
  5179.4  226.69  5210.8  225.10  5217.6  226.09  5231.7  226.12  5255.3  224.38
  5273.7  224.53  5320.3  228.10  5382.9  229.56  5400.1  230.11  5839.4  242.08
#Mann=7,-1,0
  3869.9    0.05       0  4838.1   0.035       0  5048.4    0.05       0
  5085.3   0.035       0  5090.1    0.05       0  5382.9   0.035       0
  5400.1    0.05       0
Bank Sta=5085.3,5090.1
Exp/Cntr=0.3,0.1

Type RM Length L Ch R = 1,6751,445,445,445
BEGIN DESCRIPTION:
Stream0759 11.0
END DESCRIPTION:
XS GIS Cut Line= 3
      2468225.01     13635174.98      2467525.00     13636375.00
      2467575.00     13636775.01
#Sta/Elev= 30
  3615.5  250.51  3728.9  246.00  3803.2  243.26  3965.7  236.84  4179.1  232.81
  4243.6  229.49  4473.4  226.86  4530.1  227.32  4542.9  226.08  4564.8  227.79
  4633.1  225.89  4685.9  225.94  4734.8  226.17  4799.3  223.39  4836.5  223.59
  4852.2  225.19  4879.5  222.29  4916.7  221.48  4953.9  222.36  4969.6  220.27
  4973.0  218.64  4973.3  218.14  4977.9  218.64  4981.6  220.18  4991.1  220.86
  4996.9  223.08  5035.0  226.23  5166.2  229.18  5257.9  232.34  5407.9  236.45
#Mann=9,-1,0
  3615.5    0.05       0  3728.9    0.07       0  3803.2    0.05       0
  4473.4   0.035       0  4685.9    0.05       0  4973.0    0.05       0
  4977.9    0.05       0  5166.2   0.035       0  5257.9    0.05       0
Bank Sta=4973,4977.9
Exp/Cntr=0.3,0.1

Type RM Length L Ch R = 1,6306,373,373,373
BEGIN DESCRIPTION:
Stream0759 10.0
END DESCRIPTION:
XS GIS Cut Line= 3
      2467075.00     13635374.99      2467325.00     13636125.00
      2467525.00     13636925.00
#Sta/Elev= 30
  4205.7  243.24  4258.4  240.32  4279.5  239.78  4353.3  235.38  4374.4  235.12
  4418.7  232.83  4500.9  228.39  4574.6  223.02  4637.9  220.39  4659.0  220.70
  4669.5  221.80  4711.7  221.43  4759.1  222.29  4890.9  222.20  4954.1  223.03
  4975.2  221.54  4993.6  218.64  5004.1  218.59  5004.5  218.09  5008.7  218.09
  5009.0  218.59  5047.8  219.10  5060.7  220.02  5096.8  220.15  5109.7  221.80
  5143.2  223.21  5302.9  222.32  5424.0  225.97  5559.0  232.07  5820.9  239.78
#Mann=6,-1,0
  4205.7   0.035       0  4418.7    0.05       0  5004.1    0.05       0
  5009.0    0.05       0  5424.0   0.035       0  5559.0    0.05       0
Bank Sta=5004.1,5009
Exp/Cntr=0.3,0.1

Type RM Length L Ch R = 1,5933,516,516,516
BEGIN DESCRIPTION:
Stream0759 9.0
END DESCRIPTION:
XS GIS Cut Line= 3
      2467075.00     13635524.95      2467070.74     13636422.74
      2467575.03     13637125.04
#Sta/Elev= 30
  4157.6  238.28  4507.7  223.00  4567.7  218.91  4587.7  218.23  4606.1  218.54
  4637.7  218.30  4704.9  219.71  4727.7  220.21  4747.7  218.69  4787.7  220.15
  4797.7  221.27  4827.7  221.54  4863.0  220.54  4877.7  220.59  4897.7  218.40
  4967.7  217.32  4975.2  214.45  4975.6  213.95  4980.1  214.45  4997.7  220.72
  5053.1  220.41  5225.0  219.86  5254.4  220.32  5267.5  219.67  5333.1  220.52
  5411.6  223.71  5589.7  233.38  5705.1  238.83  5841.4  244.33  5920.0  246.68
#Mann=8,-1,0
  4157.6    0.05       0  4606.1    0.07       0  4704.9    0.05       0
  4863.0     0.1       0  4975.2    0.05       0  4980.1     0.1       0
  5053.1    0.07       0  5333.1    0.05       0
Bank Sta=4975.2,4980.1
Exp/Cntr=0.3,0.1

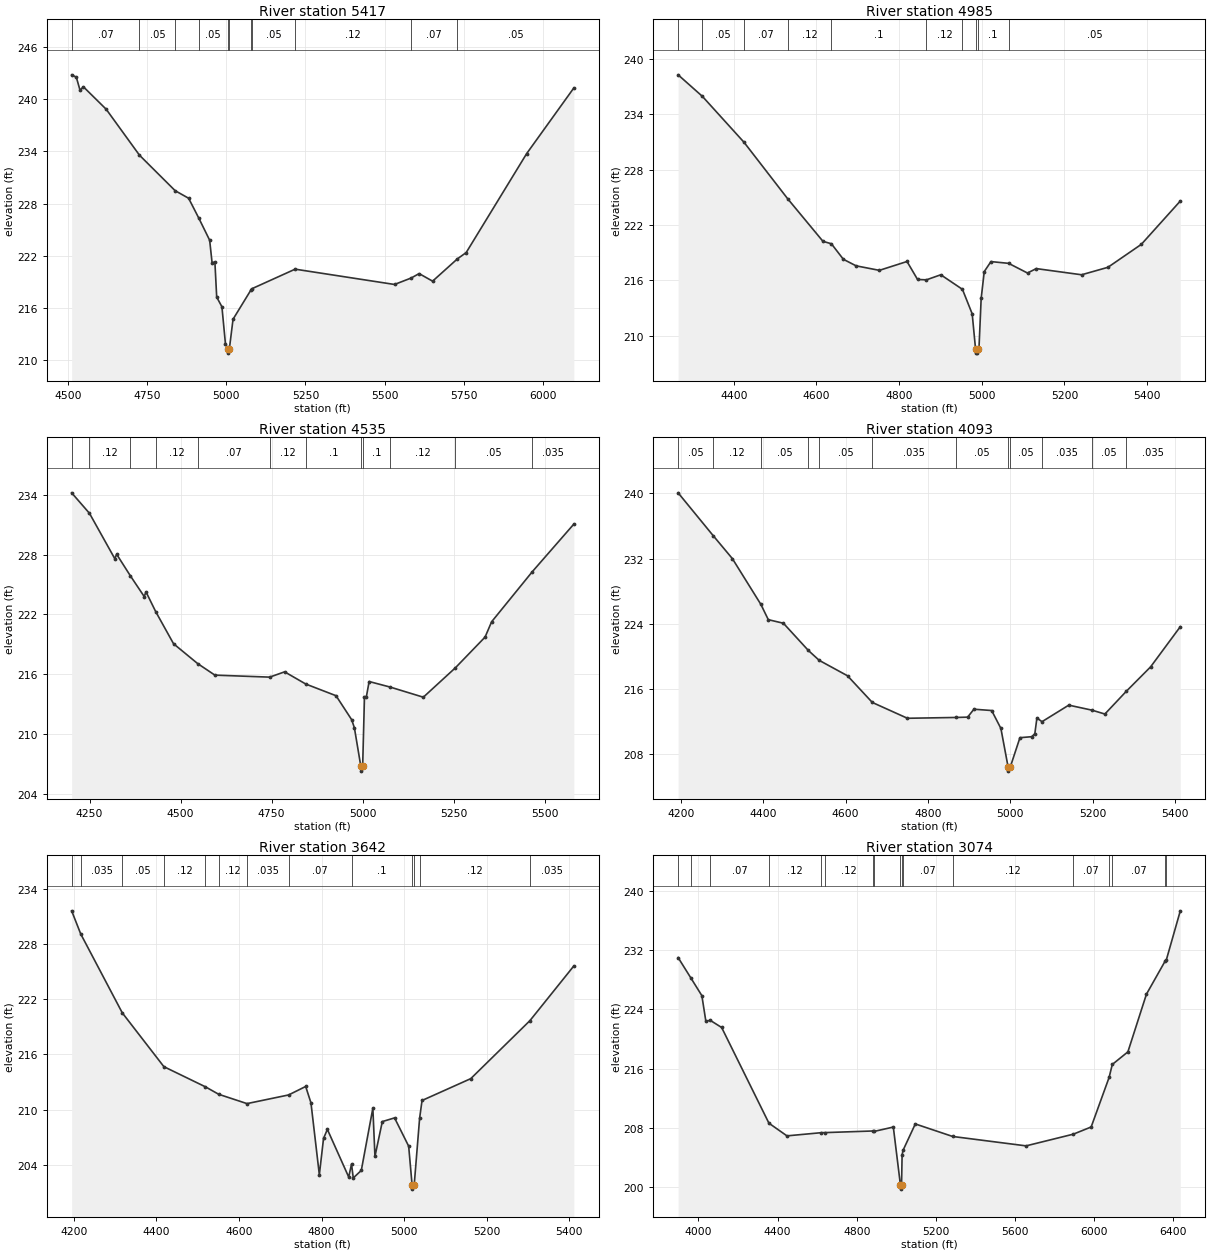
Type RM Length L Ch R = 1,5417,432,432,432
BEGIN DESCRIPTION:
Stream0759 8.0
END DESCRIPTION:
XS GIS Cut Line= 3
      2466450.90     13635791.41      2466675.00     13636225.00
      2467425.02     13637025.02
#Sta/Elev= 30
  4512.2  242.82  4526.9  242.55  4538.8  241.03  4549.1  241.45  4621.2  238.86
  4726.3  233.57  4838.8  229.49  4881.3  228.62  4913.6  226.32  4947.7  223.79
  4955.3  221.21  4964.2  221.29  4969.9  217.25  4986.4  216.13  4997.5  211.87
  5004.8  211.30  5005.2  210.80  5009.9  211.30  5021.5  214.70  5078.7  218.11
  5080.3  218.20  5217.4  220.46  5531.0  218.70  5583.5  219.44  5608.7  219.95
  5651.2  219.08  5729.6  221.65  5757.2  222.37  5948.1  233.76  6096.9  241.31
#Mann=11,-1,0
  4512.2    0.07       0  4726.3    0.05       0  4838.8    0.12       0
  4913.6    0.05       0  5004.8    0.05       0  5009.9    0.05       0
  5078.7     0.1       0  5080.3    0.05       0  5217.4    0.12       0
  5583.5    0.07       0  5729.6    0.05       0
Bank Sta=5004.8,5009.9
Exp/Cntr=0.3,0.1

Type RM Length L Ch R = 1,4985,450,450,450
BEGIN DESCRIPTION:
Stream0759 7.0
END DESCRIPTION:
XS GIS Cut Line= 3
      2466325.00     13635924.99      2466575.00     13636625.00
      2466824.99     13637024.99
#Sta/Elev= 30
  4265.2  238.29  4324.0  235.95  4424.7  230.97  4530.4  224.84  4615.6  220.23
  4636.1  219.96  4665.0  218.28  4695.8  217.57  4752.1  217.08  4819.0  218.04
  4844.5  216.09  4865.9  216.05  4900.7  216.60  4953.1  215.02  4976.7  212.36
  4984.7  208.60  4985.1  208.10  4989.4  208.10  4989.8  208.60  4993.1  208.62
  4998.4  214.03  5005.9  216.95  5022.1  218.03  5064.8  217.84  5110.5  216.79
  5131.7  217.27  5241.4  216.60  5305.1  217.41  5385.9  219.90  5480.2  224.60
#Mann=10,-1,0
  4265.2    0.07       0  4324.0    0.05       0  4424.7    0.07       0
  4530.4    0.12       0  4636.1     0.1       0  4865.9    0.12       0
  4953.1     0.1       0  4984.7    0.05       0  4989.8     0.1       0
  5064.8    0.05       0
Bank Sta=4984.7,4989.8
Exp/Cntr=0.3,0.1

Type RM Length L Ch R = 1,4535,442,442,442
BEGIN DESCRIPTION:
Stream0759 6.0
END DESCRIPTION:
XS GIS Cut Line= 3
      2466325.00     13636024.97      2466225.00     13636825.00
      2466413.81     13637364.98
#Sta/Elev= 30
  4201.0  234.18  4249.9  232.13  4319.4  227.59  4324.5  228.03  4362.2  225.87
  4400.1  223.80  4405.1  224.26  4431.8  222.28  4480.7  219.07  4546.7  217.09
  4594.1  215.93  4744.5  215.73  4785.5  216.26  4843.5  215.04  4926.6  213.87
  4969.5  211.47  4977.0  210.66  4994.6  206.82  4995.0  206.32  4999.7  206.82
  5004.7  213.77  5009.9  213.77  5017.5  215.29  5075.6  214.73  5166.2  213.72
  5254.4  216.67  5335.7  219.74  5353.6  221.27  5465.2  226.28  5579.3  231.05
#Mann=12,-1,0
  4201.0    0.07       0  4249.9    0.12       0  4362.2    0.07       0
  4431.8    0.12       0  4546.7    0.07       0  4744.5    0.12       0
  4843.5     0.1       0  4994.6    0.05       0  4999.7     0.1       0
  5075.6    0.12       0  5254.4    0.05       0  5465.2   0.035       0
Bank Sta=4994.6,4999.7
Exp/Cntr=0.3,0.1

Type RM Length L Ch R = 1,4093,451,451,451
BEGIN DESCRIPTION:
Stream0759 5.0
END DESCRIPTION:
XS GIS Cut Line= 3
      2465475.01     13636075.02      2465875.00     13636775.00
      2465975.00     13637174.99
#Sta/Elev= 30
  4193.8  240.07  4279.2  234.80  4325.5  232.00  4394.5  226.40  4412.6  224.52
  4449.3  224.08  4509.9  220.74  4536.2  219.53  4604.8  217.64  4665.0  214.37
  4750.2  212.43  4869.0  212.53  4896.3  212.57  4911.5  213.54  4954.6  213.38
  4977.0  211.18  4994.5  206.45  4994.9  205.95  4999.7  206.45  5023.2  210.05
  5051.5  210.17  5059.3  210.53  5064.4  212.47  5076.7  212.01  5141.7  214.04
  5198.3  213.42  5229.3  212.95  5281.3  215.74  5340.2  218.73  5412.3  223.66
#Mann=12,-1,0
  4193.8    0.05       0  4279.2    0.12       0  4394.5    0.05       0
  4509.9   0.035       0  4536.2    0.05       0  4665.0   0.035       0
  4869.0    0.05       0  4994.5    0.05       0  4999.7    0.05       0
  5076.7   0.035       0  5198.3    0.05       0  5281.3   0.035       0
Bank Sta=4994.5,4999.7
Exp/Cntr=0.3,0.1

Type RM Length L Ch R = 1,3642,568,568,568
BEGIN DESCRIPTION:
Stream0759 4.0
END DESCRIPTION:
XS GIS Cut Line= 3
      2465475.00     13636224.98      2465625.00     13637025.00
      2465975.02     13637225.01
#Sta/Elev= 30
  4194.4  231.59  4216.4  229.08  4317.1  220.52  4417.9  214.68  4518.7  212.49
  4550.9  211.68  4619.4  210.67  4720.2  211.61  4761.6  212.53  4774.4  210.75
  4794.7  202.95  4804.9  206.90  4814.2  207.87  4865.9  202.70  4872.7  204.11
  4876.9  202.60  4896.4  203.42  4924.4  210.17  4929.5  204.94  4947.3  208.72
  4977.0  209.12  5011.2  206.05  5019.4  201.89  5019.8  201.39  5024.7  201.89
  5037.7  209.07  5043.6  211.01  5161.7  213.38  5305.0  219.67  5411.5  225.61
#Mann=13,-1,0
  4194.4    0.12       0  4216.4   0.035       0  4317.1    0.05       0
  4417.9    0.12       0  4518.7   0.035       0  4550.9    0.12       0
  4619.4   0.035       0  4720.2    0.07       0  4872.7     0.1       0
  5019.4    0.05       0  5024.7     0.1       0  5037.7    0.12       0
  5305.0   0.035       0
Bank Sta=5019.4,5024.7
Exp/Cntr=0.3,0.1

Type RM Length L Ch R = 1,3074,524,524,524
BEGIN DESCRIPTION:
XS7671
END DESCRIPTION:
XS GIS Cut Line= 4
      2465136.65     13635975.06      2465153.87     13637025.35
      2465412.13     13637530.39      2466150.37     13638079.78
#Sta/Elev= 30
  3897.5  231.00  3962.3  228.23  4017.5  225.86  4037.5  222.44  4060.8  222.51
  4117.5  221.56  4356.5  208.64  4447.5  206.93  4621.1  207.36  4639.5  207.37
  4881.7  207.59  4887.8  207.53  4985.1  208.12  5021.3  200.24  5021.7  199.74
  5026.6  200.24  5029.5  204.39  5034.4  204.99  5096.2  208.54  5284.8  206.85
  5655.9  205.58  5894.9  207.16  5984.9  208.13  6075.6  214.82  6091.7  216.57
  6170.5  218.27  6264.3  226.06  6359.5  230.56  6364.2  230.63  6435.4  237.31
#Mann=17,-1,0
  3897.5    0.05       0  3962.3   0.035       0  4060.8    0.07       0
  4356.5    0.12       0  4621.1    0.07       0  4639.5    0.12       0
  4881.7    0.07       0  4887.8    0.12       0  5021.3    0.05       0
  5026.6    0.12       0  5034.4    0.07       0  5284.8    0.12       0
  5894.9    0.07       0  6075.6    0.12       0  6091.7    0.07       0
  6359.5    0.05       0  6364.2    0.07       0
Bank Sta=5021.3,5026.6
Exp/Cntr=0.3,0.1

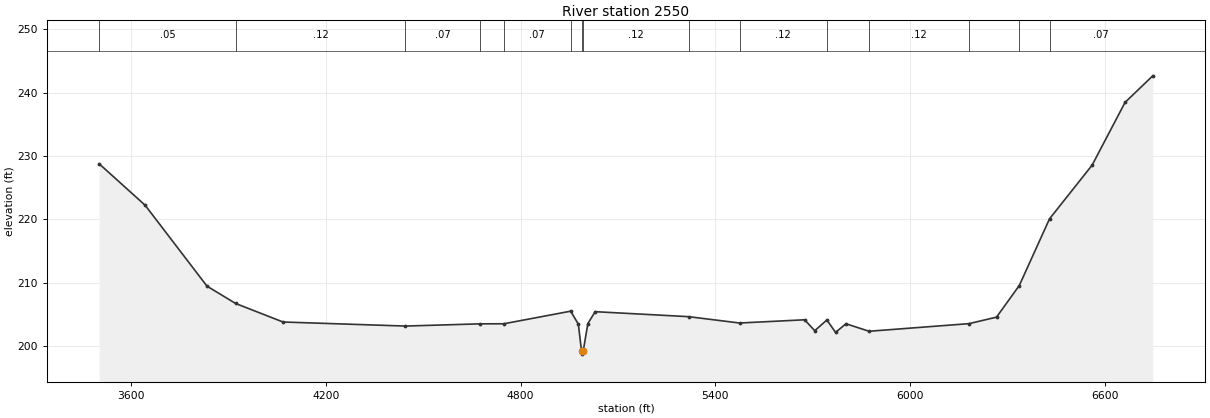
Type RM Length L Ch R = 1,2550,0,0,0
BEGIN DESCRIPTION:
XS7670
END DESCRIPTION:
XS GIS Cut Line= 4
      2464826.74     13635888.99      2464620.13     13636945.00
      2465039.09     13637800.13      2466179.88     13638230.08
#Sta/Elev= 30
  3501.2  228.77  3642.7  222.24  3833.4  209.47  3921.8  206.73  4067.8  203.81
  4445.0  203.17  4675.5  203.52  4748.3  203.53  4954.4  205.52  4978.1  203.47
  4987.8  199.24  4988.2  198.74  4993.1  199.24  5007.4  203.56  5029.9  205.44
  5318.3  204.65  5475.2  203.65  5675.5  204.16  5706.8  202.44  5744.2  204.13
  5770.9  202.17  5803.0  203.53  5874.3  202.35  6182.3  203.55  6267.1  204.58
  6337.3  209.57  6430.4  220.09  6561.7  228.56  6663.3  238.47  6748.6  242.66
#Mann=15,-1,0
  3501.2    0.05       0  3921.8    0.12       0  4445.0    0.07       0
  4675.5    0.12       0  4748.3    0.07       0  4954.4    0.12       0
  4987.8    0.05       0  4993.1    0.12       0  5318.3    0.07       0
  5475.2    0.12       0  5744.2    0.07       0  5874.3    0.12       0
  6182.3    0.07       0  6337.3    0.12       0  6430.4    0.07       0
Bank Sta=4987.8,4993.1
Exp/Cntr=0.3,0.1

Chan Stop Cuts=-1