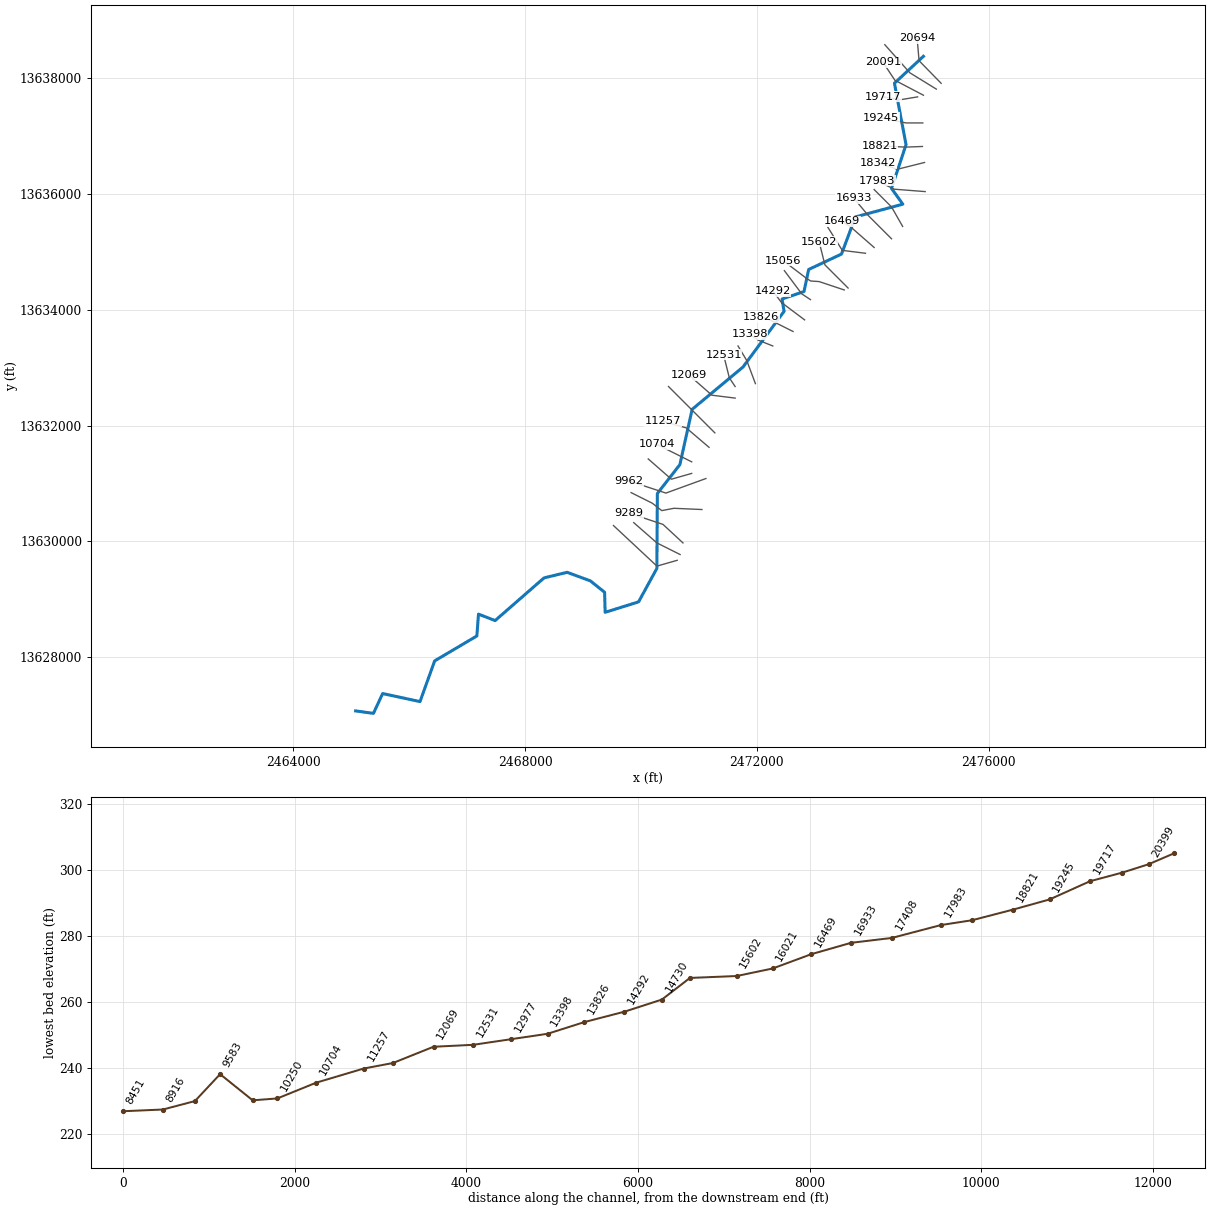
--- Stream0762.prj (project) ---

Proj Title=Stream0762 Base Level Engineering
Current Plan=p01
Default Exp/Contr=0.3,0.1
English Units
Geom File=g01
Flow File=f01
Plan File=p01
BEGIN DESCRIPTION:
Stream0762
END DESCRIPTION:

--- Stream0762.p01 (plan) ---

Plan Title=Multiple Run
Short Identifier=Multiple
Geom File=g01
Flow File=f01
Subcritical Flow
K Sum by GR= 0
Std Step Tol= 0.01
Critical Tol= 0.01
Num of Std Step Trials= 20
Max Error Tol= 0.3
Flow Tol Ratio= 0.001
Split Flow NTrial= 30
Split Flow Tol= 0.02
Split Flow Ratio= 0.02
Log Output Level= 0
Friction Slope Method= 1
Unsteady Friction Slope Method= 2
Unsteady Bridges Friction Slope Method= 1
Parabolic Critical Depth
Global Vel Dist=  1 , 1 , 1
Global Log Level= 0
CheckData=True
Encroach Param= -1, 0, 0, 0
BEGIN DESCRIPTION:
Multiple Run
END DESCRIPTION:

--- Stream0762.f01 (steady flow) ---

Flow Title=Multiple
Number of Profiles=7
Profile Names=10-year,25-year,50-year,1pct_min,100-year,1pct_plu,500-year
River Rch & RM= Stream0762,Reach-1,20694
     861    1424    1945    1288    2571    5129    4444
River Rch & RM= Stream0762,Reach-1,16933
    1195    1992    2736    1818    3627    7237    6313
River Rch & RM= Stream0762,Reach-1,8010
    1467    2473    3421    2286    4561    9100    8036
Boundary for River Rch & Prof#=Stream0762,Reach-1,1
Up Type=0
Dn Type=3
Dn Slope=0.005
Boundary for River Rch & Prof#=Stream0762,Reach-1,2
Up Type=0
Dn Type=3
Dn Slope=0.005
Boundary for River Rch & Prof#=Stream0762,Reach-1,3
Up Type=0
Dn Type=3
Dn Slope=0.005
Boundary for River Rch & Prof#=Stream0762,Reach-1,4
Up Type=0
Dn Type=3
Dn Slope=0.005
Boundary for River Rch & Prof#=Stream0762,Reach-1,5
Up Type=0
Dn Type=3
Dn Slope=0.005
Boundary for River Rch & Prof#=Stream0762,Reach-1,6
Up Type=0
Dn Type=3
Dn Slope=0.005
Boundary for River Rch & Prof#=Stream0762,Reach-1,7
Up Type=0
Dn Type=3
Dn Slope=0.005

--- Stream0762.g01 (geometry) ---

Geom Title=Existing Conditions

River Reach=Stream0762,Reach-1
Reach XY= 30
      2474875.00     13638375.00      2474375.18     13637909.92
      2474575.32     13636849.80      2474324.96     13636094.98
      2474520.05     13635822.42      2473701.26     13635602.70
      2473461.53     13634961.43      2472894.43     13634695.09
      2472814.04     13634314.57      2472435.03     13634185.06
      2472469.72     13633972.29      2471761.38     13633011.78
      2470883.02     13632281.34      2470671.26     13631326.56
      2470282.76     13630828.39      2470274.23     13629535.69
      2469958.37     13628957.44      2469380.84     13628777.05
      2469371.99     13629123.57      2469127.43     13629319.48
      2468725.34     13629467.78      2468326.46     13629371.46
      2467481.66     13628634.31      2467194.88     13628746.00
      2467166.86     13628368.94      2466438.23     13627938.67
      2466185.50     13627235.96      2465540.21     13627374.77
      2465381.52     13627032.67      2465075.00     13627075.00

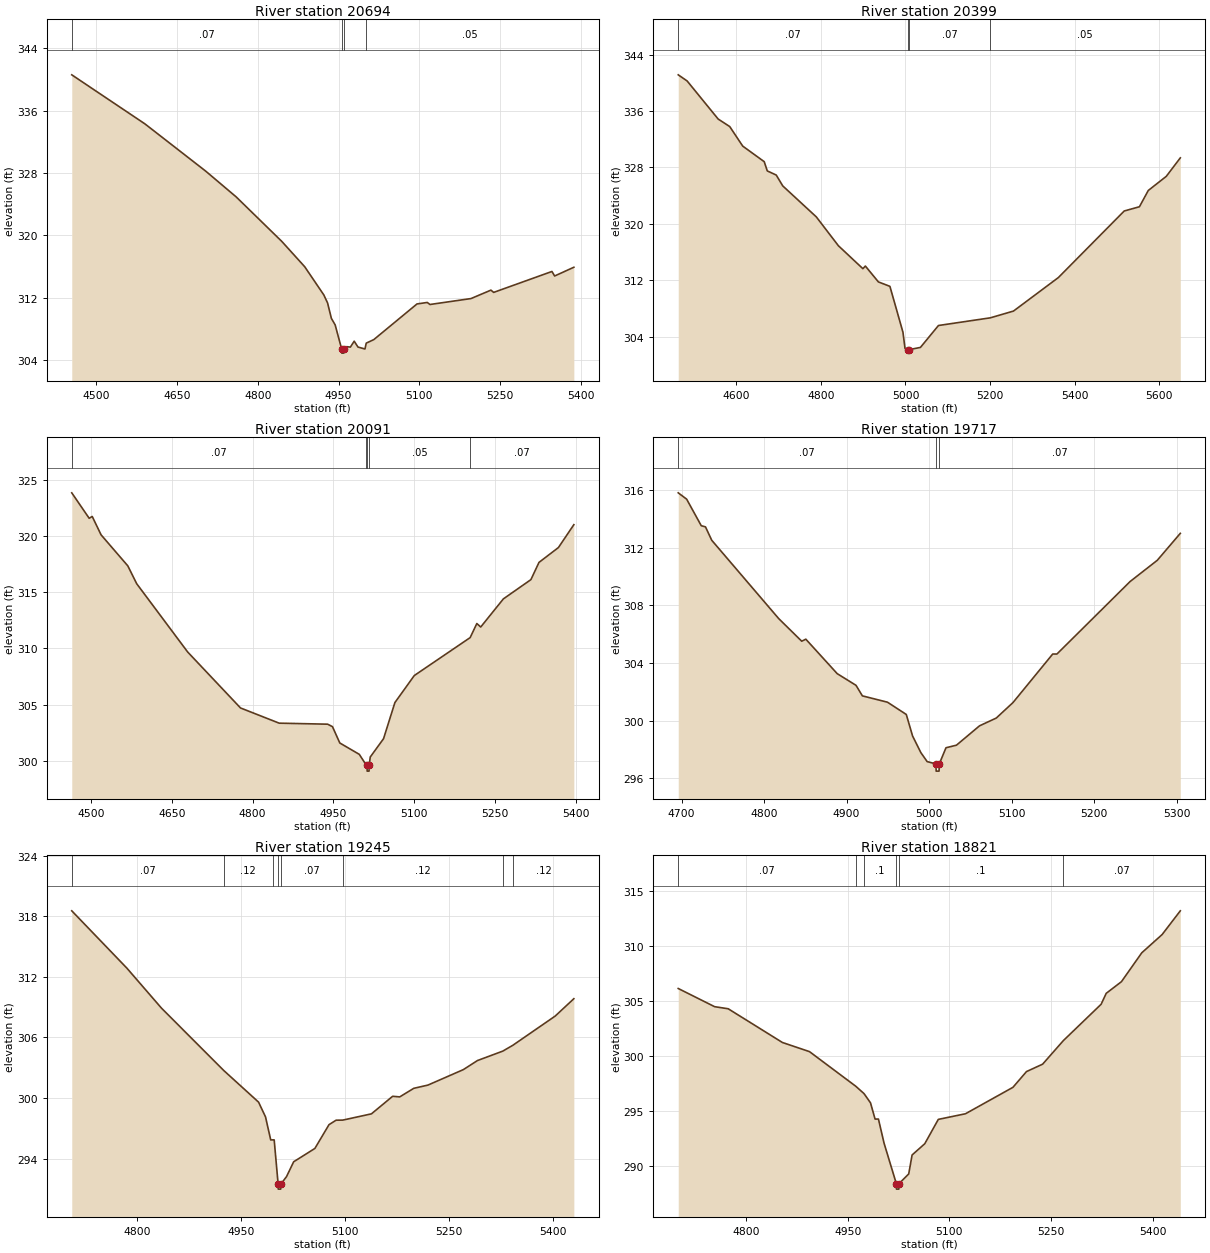
Type RM Length L Ch R = 1,20694,295,295,295
BEGIN DESCRIPTION:
Stream0762 39.0
END DESCRIPTION:
XS GIS Cut Line= 3
      2475181.44     13637909.19      2474800.30     13638298.68
      2474766.92     13638685.40
#Sta/Elev= 30
  4454.1  340.58  4590.0  334.30  4703.1  328.24  4759.7  324.94  4844.6  319.23
  4887.0  316.00  4922.5  312.39  4929.5  311.36  4936.6  309.38  4943.6  308.55
  4955.8  305.43  4956.0  304.93  4959.5  304.93  4959.8  305.43  4964.9  305.76
  4971.9  305.70  4979.0  306.46  4986.0  305.71  4999.0  305.46  5001.4  306.21
  5015.4  306.66  5095.7  311.23  5114.8  311.42  5119.8  311.16  5196.1  311.92
  5233.1  313.00  5238.2  312.71  5346.5  315.39  5351.5  314.81  5387.2  315.93
#Mann=4,-1,0
  4454.1    0.07       0  4955.8    0.05       0  4959.8    0.07       0
  5001.4    0.05       0
Bank Sta=4955.8,4959.8
Exp/Cntr=0.3,0.1

Type RM Length L Ch R = 1,20399,308,308,308
BEGIN DESCRIPTION:
XS7682
END DESCRIPTION:
XS GIS Cut Line= 3
      2475098.01     13637809.02      2474641.72     13638090.02
      2474208.85     13638575.62
#Sta/Elev= 30
  4463.1  341.15  4484.1  340.28  4557.5  334.87  4584.7  333.81  4615.5  331.03
  4666.3  328.82  4673.5  327.51  4694.7  326.92  4710.1  325.38  4789.4  320.98
  4841.5  316.89  4899.4  313.63  4905.3  314.00  4936.1  311.75  4963.3  311.12
  4994.1  304.61  4999.0  302.30  5005.0  302.14  5005.2  301.64  5009.0  302.14
  5035.4  302.45  5078.0  305.56  5200.5  306.65  5255.3  307.61  5361.4  312.37
  5517.0  321.82  5552.9  322.42  5573.8  324.73  5616.4  326.74  5649.5  329.36
#Mann=4,-1,0
  4463.1    0.07       0  5005.0    0.05       0  5009.0    0.07       0
  5200.5    0.05       0
Bank Sta=5005,5009
Exp/Cntr=0.3,0.1

Type RM Length L Ch R = 1,20091,374,374,374
BEGIN DESCRIPTION:
Stream0762 38.0
END DESCRIPTION:
XS GIS Cut Line= 3
      2474875.46     13637703.29      2474382.99     13637962.05
      2474174.99     13638275.02
#Sta/Elev= 30
  4464.2  323.82  4496.5  321.56  4502.2  321.72  4518.6  320.09  4568.3  317.33
  4584.7  315.75  4679.4  309.68  4777.5  304.71  4849.3  303.36  4939.2  303.27
  4948.2  303.05  4961.8  301.60  4998.0  300.59  5011.0  299.63  5012.4  299.60
  5012.6  299.10  5016.1  299.10  5016.4  299.60  5018.3  300.35  5043.0  301.98
  5064.1  305.19  5100.1  307.59  5203.8  310.96  5216.2  312.21  5223.4  311.90
  5265.5  314.40  5316.6  316.11  5331.6  317.64  5367.7  318.96  5396.3  320.99
#Mann=5,-1,0
  4464.2    0.07       0  5011.0    0.05       0  5012.4    0.05       0
  5016.4    0.05       0  5203.8    0.07       0
Bank Sta=5012.4,5016.4
Exp/Cntr=0.3,0.1

Type RM Length L Ch R = 1,19717,472,472,472
BEGIN DESCRIPTION:
Stream0762 37.0
END DESCRIPTION:
XS GIS Cut Line= 3
      2474775.02     13637675.00      2474475.00     13637625.00
      2474175.00     13637675.00
#Sta/Elev= 30
  4696.0  315.80  4706.2  315.36  4723.9  313.52  4729.0  313.44  4736.6  312.51
  4817.7  307.08  4845.6  305.51  4850.6  305.65  4888.6  303.26  4911.4  302.45
  4919.1  301.72  4949.5  301.28  4972.3  300.43  4979.9  298.94  4990.0  297.78
  4997.6  297.16  5008.3  297.00  5008.5  296.50  5012.0  296.50  5012.3  297.00
  5020.4  298.12  5033.1  298.30  5061.0  299.64  5081.3  300.18  5101.5  301.25
  5149.7  304.62  5154.8  304.62  5243.5  309.65  5276.4  311.12  5304.3  312.99
#Mann=3,-1,0
  4696.0    0.07       0  5008.3    0.05       0  5012.3    0.07       0
Bank Sta=5008.3,5012.3
Exp/Cntr=0.3,0.1

Type RM Length L Ch R = 1,19245,424,424,424
BEGIN DESCRIPTION:
Stream0762 36.0
END DESCRIPTION:
XS GIS Cut Line= 5
      2474864.49     13637225.00      2474675.00     13637225.00
      2474575.00     13637225.00      2474325.00     13637275.00
      2474148.63     13637310.27
#Sta/Elev= 30
  4705.7  318.55  4785.2  312.87  4835.2  308.90  4924.9  302.73  4975.2  299.59
  4985.2  298.13  4992.7  295.85  4995.8  295.85  4997.7  295.85  5003.4  291.47
  5003.6  290.97  5007.1  290.97  5007.4  291.47  5015.6  292.22  5025.8  293.68
  5056.4  295.00  5076.8  297.36  5087.0  297.80  5096.7  297.81  5138.0  298.43
  5168.6  300.17  5178.8  300.11  5199.1  300.96  5219.5  301.28  5270.5  302.81
  5290.9  303.71  5327.6  304.65  5342.1  305.23  5403.1  308.12  5430.0  309.84
#Mann=8,-1,0
  4705.7    0.07       0  4924.9    0.12       0  4995.8    0.07       0
  5003.4    0.05       0  5007.4    0.07       0  5096.7    0.12       0
  5327.6    0.07       0  5342.1    0.12       0
Bank Sta=5003.4,5007.4
Exp/Cntr=0.3,0.1

Type RM Length L Ch R = 1,18821,479,479,479
BEGIN DESCRIPTION:
Stream0762 35.0
END DESCRIPTION:
XS GIS Cut Line= 4
      2474858.71     13636818.61      2474566.61     13636807.48
      2474225.00     13636825.00      2474118.21     13636830.48
#Sta/Elev= 30
  4699.7  306.11  4753.4  304.46  4773.5  304.27  4853.5  301.21  4893.5  300.38
  4961.8  297.24  4974.0  296.57  4983.6  295.73  4990.3  294.26  4995.3  294.26
  5003.6  292.07  5021.7  288.40  5021.9  287.90  5025.4  287.90  5025.7  288.40
  5040.0  289.28  5045.0  291.00  5063.7  292.02  5083.7  294.23  5123.8  294.74
  5193.9  297.14  5213.9  298.57  5237.7  299.24  5268.3  301.38  5324.1  304.68
  5331.6  305.67  5354.1  306.73  5384.1  309.35  5414.2  311.01  5441.0  313.16
#Mann=6,-1,0
  4699.7    0.07       0  4961.8    0.12       0  4974.0     0.1       0
  5021.7    0.05       0  5025.7     0.1       0  5268.3    0.07       0
Bank Sta=5021.7,5025.7
Exp/Cntr=0.3,0.1

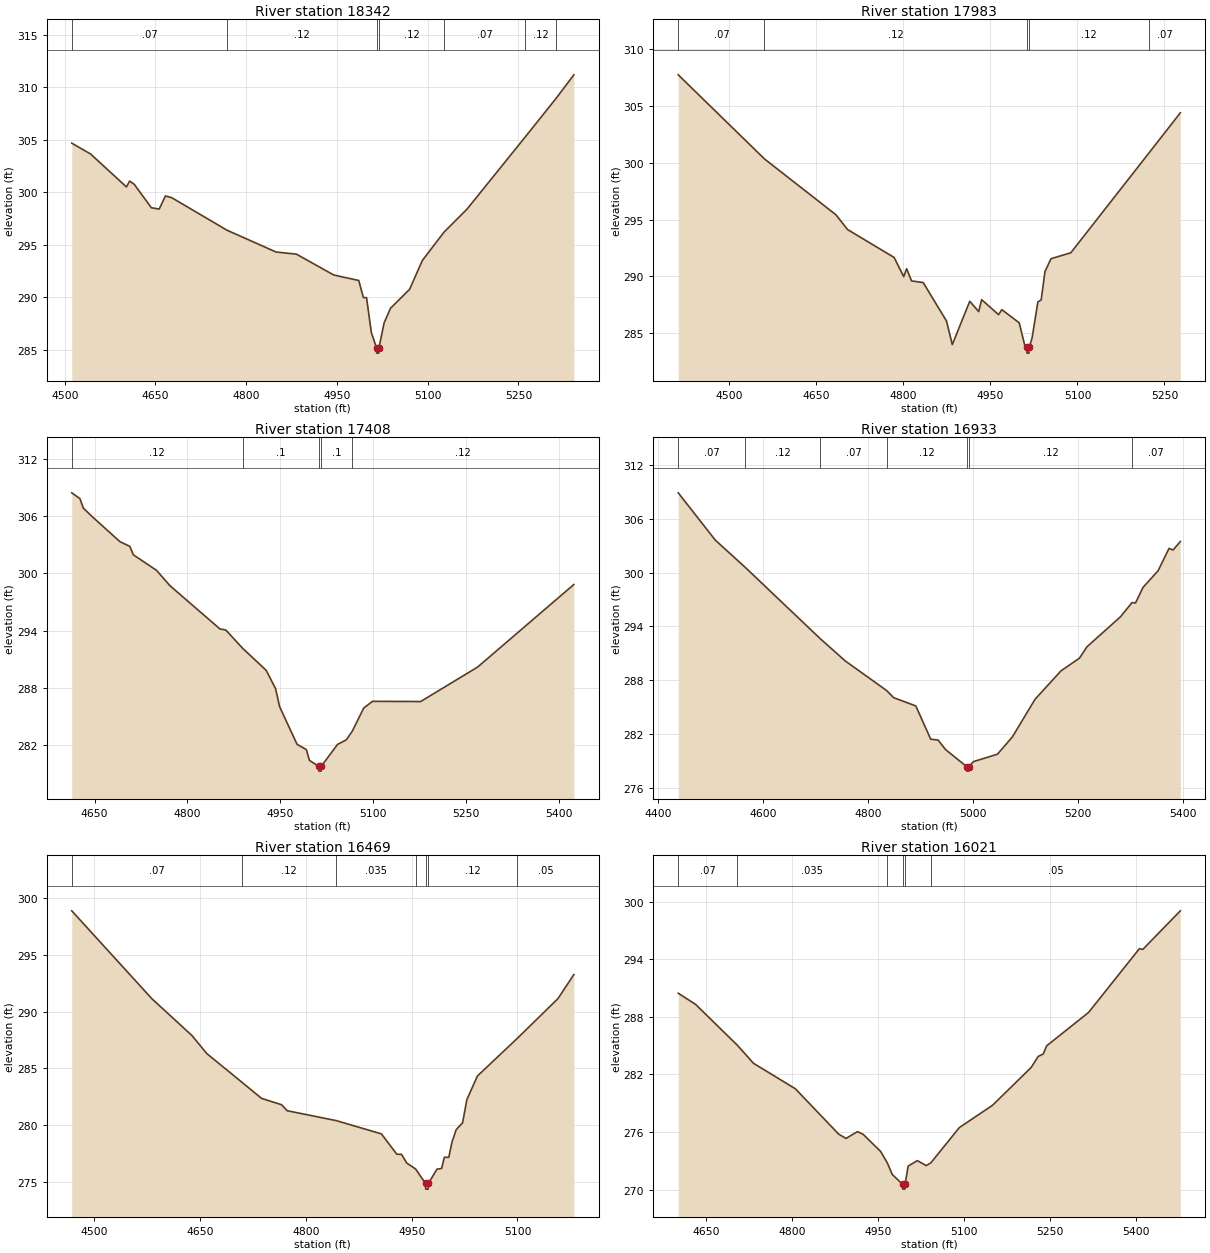
Type RM Length L Ch R = 1,18342,359,359,359
BEGIN DESCRIPTION:
Stream0762 34.0
END DESCRIPTION:
XS GIS Cut Line= 5
      2474895.22     13636542.55      2474625.00     13636475.00
      2474425.00     13636425.00      2474275.00     13636475.00
      2474097.41     13636534.20
#Sta/Elev= 30
  4511.7  304.67  4542.8  303.64  4602.1  300.50  4607.3  301.06  4615.0  300.75
  4643.3  298.52  4656.2  298.39  4666.5  299.64  4676.9  299.48  4768.3  296.38
  4849.5  294.30  4883.0  294.10  4944.9  292.11  4986.1  291.59  4993.8  289.96
  4999.0  289.96  5006.9  286.65  5015.5  285.17  5015.7  284.67  5019.2  284.67
  5019.5  285.17  5028.0  287.54  5038.6  288.94  5070.2  290.75  5091.3  293.50
  5127.3  296.21  5165.0  298.38  5261.2  305.25  5312.8  308.97  5341.7  311.18
#Mann=7,-1,0
  4511.7    0.07       0  4768.3    0.12       0  5015.5    0.05       0
  5019.5    0.12       0  5127.3    0.07       0  5261.2    0.12       0
  5312.8    0.07       0
Bank Sta=5015.5,5019.5
Exp/Cntr=0.3,0.1

Type RM Length L Ch R = 1,17983,575,575,575
BEGIN DESCRIPTION:
Stream0762 33.0
END DESCRIPTION:
XS GIS Cut Line= 3
      2474906.05     13636039.62      2474371.86     13636081.35
      2474075.01     13636225.00
#Sta/Elev= 30
  4411.7  307.75  4560.4  300.34  4683.6  295.42  4703.6  294.12  4783.9  291.66
  4800.4  289.97  4805.4  290.67  4814.0  289.59  4834.0  289.45  4874.2  286.06
  4884.2  283.98  4914.3  287.80  4929.7  286.89  4934.8  287.94  4964.0  286.62
  4969.6  287.06  4999.6  285.90  5009.2  283.90  5012.8  283.73  5013.0  283.23
  5016.5  283.23  5016.8  283.73  5021.8  284.58  5031.8  287.75  5037.4  287.91
  5044.0  290.42  5054.4  291.55  5088.5  292.07  5224.1  300.92  5277.3  304.40
#Mann=5,-1,0
  4411.7    0.07       0  4560.4    0.12       0  5012.8    0.05       0
  5016.8    0.12       0  5224.1    0.07       0
Bank Sta=5012.8,5016.8
Exp/Cntr=0.3,0.1

Type RM Length L Ch R = 1,17408,475,475,475
BEGIN DESCRIPTION:
Stream0762 32.0
END DESCRIPTION:
XS GIS Cut Line= 3
      2474516.51     13635438.72      2474325.00     13635775.00
      2474024.96     13636075.04
#Sta/Elev= 30
  4613.0  308.42  4626.1  307.82  4631.8  306.81  4647.7  305.83  4690.9  303.31
  4706.8  302.82  4712.5  301.94  4750.0  300.31  4771.6  298.71  4852.3  294.19
  4861.9  294.07  4889.1  292.16  4927.2  289.85  4942.4  287.93  4948.8  286.06
  4977.0  282.12  4992.1  281.56  4997.1  280.43  5012.1  279.81  5012.4  279.31
  5015.9  279.31  5016.1  279.81  5042.4  282.10  5056.6  282.58  5066.2  283.48
  5084.8  285.91  5099.0  286.61  5176.8  286.59  5268.7  290.19  5424.3  298.83
#Mann=5,-1,0
  4613.0    0.12       0  4889.1     0.1       0  5012.1    0.05       0
  5016.1     0.1       0  5066.2    0.12       0
Bank Sta=5012.1,5016.1
Exp/Cntr=0.3,0.1

Type RM Length L Ch R = 1,16933,464,464,464
BEGIN DESCRIPTION:
Stream0762 31.0
END DESCRIPTION:
XS GIS Cut Line= 3
      2474324.98     13635225.02      2473925.00     13635625.00
      2473674.98     13635925.03
#Sta/Elev= 30
  4438.9  308.91  4509.6  303.62  4565.9  300.62  4709.2  292.63  4757.1  290.13
  4835.6  286.84  4849.0  286.04  4891.4  285.11  4919.7  281.40  4933.8  281.30
  4948.0  280.24  4988.4  278.33  4988.7  277.83  4992.2  277.83  4992.4  278.33
  5001.0  278.89  5046.9  279.72  5075.5  281.67  5118.5  285.86  5167.9  289.03
  5203.1  290.45  5217.4  291.72  5281.2  295.07  5303.1  296.65  5309.8  296.61
  5324.1  298.35  5352.8  300.21  5373.6  302.70  5381.4  302.53  5395.1  303.47
#Mann=7,-1,0
  4438.9    0.07       0  4565.9    0.12       0  4709.2    0.07       0
  4835.6    0.12       0  4988.4    0.05       0  4992.4    0.12       0
  5303.1    0.07       0
Bank Sta=4988.4,4992.4
Exp/Cntr=0.3,0.1

Type RM Length L Ch R = 1,16469,448,448,448
BEGIN DESCRIPTION:
Stream0762 30.0
END DESCRIPTION:
XS GIS Cut Line= 3
      2474025.01     13635074.99      2473625.00     13635425.00
      2473475.00     13635525.00
#Sta/Elev= 30
  4468.1  298.86  4581.5  291.14  4638.5  287.89  4659.4  286.31  4708.8  283.81
  4737.2  282.36  4765.7  281.80  4773.3  281.28  4842.8  280.41  4907.1  279.24
  4928.9  277.45  4935.6  277.44  4943.1  276.67  4955.6  276.15  4969.6  274.88
  4969.9  274.38  4973.4  274.38  4973.7  274.88  4985.9  276.14  4992.5  276.20
  4996.3  277.18  5002.6  277.18  5007.1  278.51  5013.1  279.61  5022.2  280.22
  5028.2  282.25  5043.2  284.33  5099.7  287.64  5157.4  291.14  5179.9  293.25
#Mann=7,-1,0
  4468.1    0.07       0  4708.8    0.12       0  4842.8   0.035       0
  4955.6    0.12       0  4969.6    0.05       0  4973.7    0.12       0
  5099.7    0.05       0
Bank Sta=4969.6,4973.7
Exp/Cntr=0.3,0.1

Type RM Length L Ch R = 1,16021,419,419,419
BEGIN DESCRIPTION:
Stream0762 29.0
END DESCRIPTION:
XS GIS Cut Line= 3
      2473875.00     13634975.00      2473475.00     13635025.00
      2473225.00     13635424.99
#Sta/Elev= 30
  4601.7  290.46  4631.9  289.30  4704.8  285.04  4732.7  283.17  4805.8  280.51
  4881.4  275.78  4894.0  275.34  4914.1  276.05  4924.2  275.75  4954.4  273.98
  4966.0  272.79  4974.6  271.59  4992.6  270.56  4992.9  270.06  4996.6  270.06
  4996.9  270.56  5002.3  272.46  5018.4  273.03  5033.7  272.51  5041.9  272.80
  5091.5  276.47  5149.3  278.79  5216.5  282.72  5228.9  283.88  5237.7  284.13
  5243.6  284.98  5316.7  288.46  5405.2  295.10  5411.1  295.02  5476.5  299.04
#Mann=6,-1,0
  4601.7    0.07       0  4704.8   0.035       0  4966.0    0.07       0
  4992.6    0.05       0  4996.9    0.07       0  5041.9    0.05       0
Bank Sta=4992.6,4996.9
Exp/Cntr=0.3,0.1

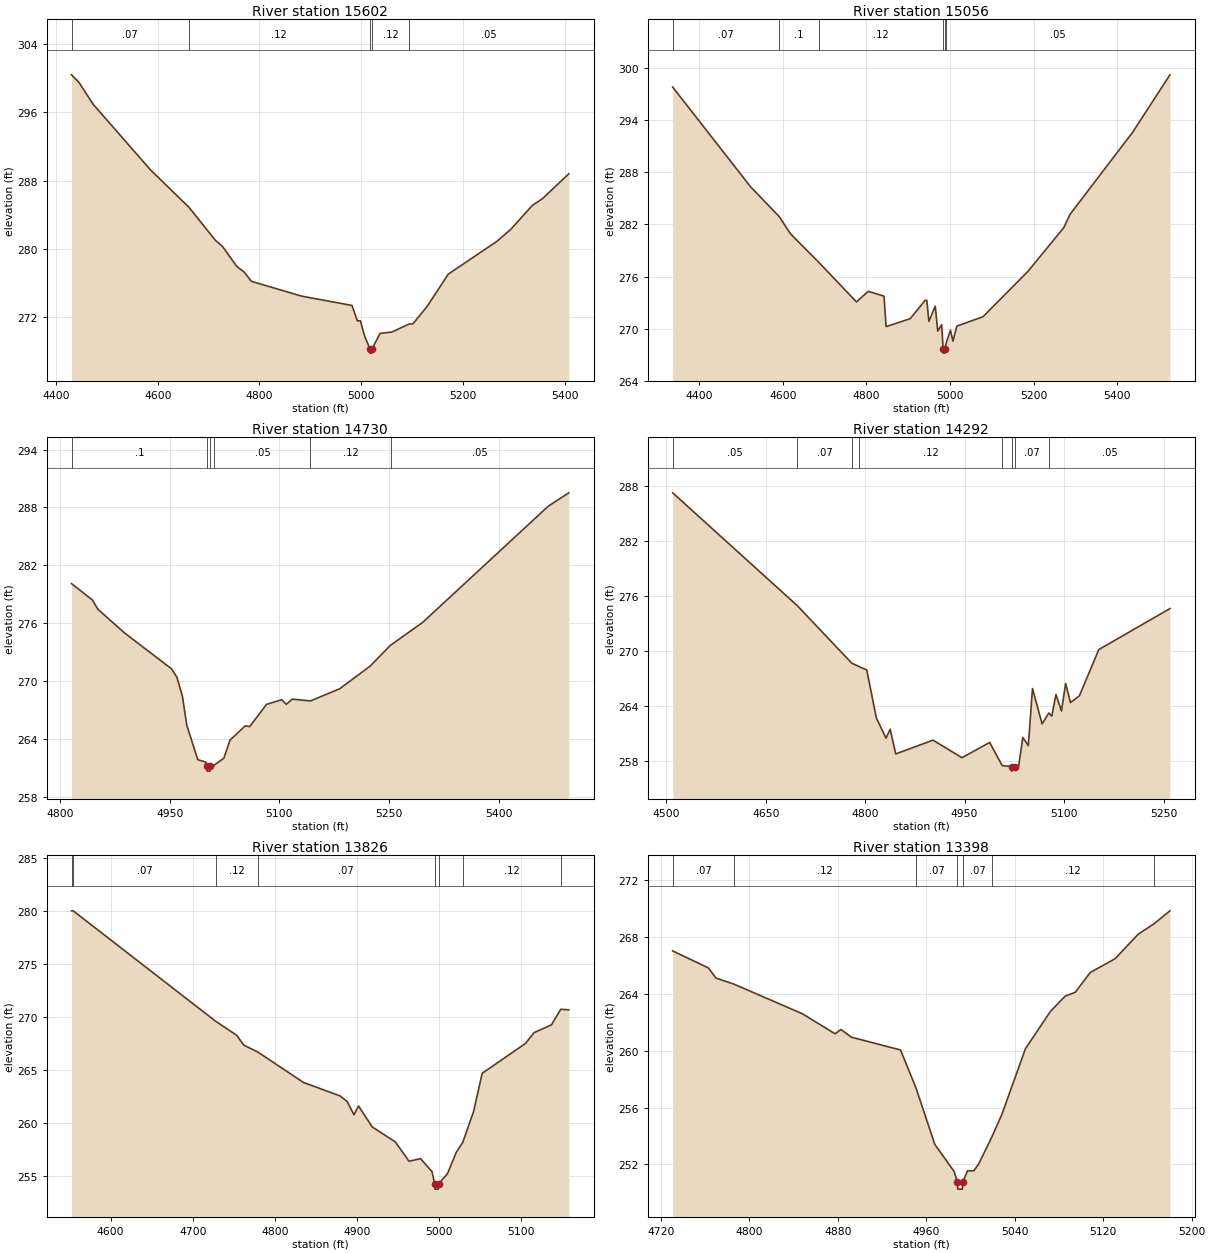
Type RM Length L Ch R = 1,15602,546,546,546
BEGIN DESCRIPTION:
Stream0762 28.0
END DESCRIPTION:
XS GIS Cut Line= 3
      2473575.03     13634374.97      2473175.00     13634775.00
      2473075.01     13635174.96
#Sta/Elev= 30
  4430.4  300.39  4444.6  299.54  4472.9  296.94  4586.0  289.23  4661.0  284.89
  4713.3  281.00  4727.4  280.27  4755.7  277.91  4769.9  277.28  4784.0  276.19
  4883.0  274.45  4982.0  273.36  4992.6  271.55  4998.7  271.55  5006.4  269.85
  5017.2  268.27  5017.5  267.77  5021.2  267.77  5021.5  268.27  5037.4  270.09
  5060.6  270.24  5093.9  271.17  5101.8  271.20  5130.1  273.27  5171.4  277.03
  5266.7  280.86  5295.1  282.32  5336.3  285.06  5356.9  285.89  5408.4  288.79
#Mann=5,-1,0
  4430.4    0.07       0  4661.0    0.12       0  5017.2    0.05       0
  5021.5    0.12       0  5093.9    0.05       0
Bank Sta=5017.2,5021.5
Exp/Cntr=0.3,0.1

Type RM Length L Ch R = 1,15056,326,326,326
BEGIN DESCRIPTION:
Stream0762 27.0
END DESCRIPTION:
XS GIS Cut Line= 5
      2473508.90     13634341.78      2473074.63     13634486.53
      2472928.29     13634496.71      2472859.31     13634540.82
      2472458.79     13634843.91
#Sta/Elev= 30
  4336.9  297.80  4523.2  286.32  4591.8  282.89  4618.1  280.94  4686.7  277.61
  4776.2  273.08  4804.3  274.30  4842.0  273.75  4847.0  270.24  4904.6  271.15
  4940.5  273.27  4944.4  273.27  4949.3  270.84  4964.5  272.60  4970.5  269.72
  4979.8  270.46  4983.4  267.69  4983.7  267.19  4987.6  267.19  4987.9  267.69
  4991.2  268.45  5000.9  269.83  5006.8  268.57  5016.1  270.30  5078.8  271.38
  5186.5  276.62  5271.8  281.63  5286.4  283.14  5436.2  292.59  5525.5  299.21
#Mann=6,-1,0
  4336.9    0.07       0  4591.8     0.1       0  4686.7    0.12       0
  4983.4    0.05       0  4987.9    0.12       0  4991.2    0.05       0
Bank Sta=4983.4,4987.9
Exp/Cntr=0.3,0.1

Type RM Length L Ch R = 1,14730,438,438,438
BEGIN DESCRIPTION:
Stream0762 26.0
END DESCRIPTION:
XS GIS Cut Line= 3
      2472924.97     13634175.02      2472775.00     13634275.00
      2472475.03     13634674.96
#Sta/Elev= 30
  4815.8  280.09  4844.3  278.40  4851.8  277.44  4887.9  275.00  4952.5  271.26
  4960.0  270.38  4967.5  268.40  4973.5  265.39  4988.5  261.83  4999.2  261.58
  5001.1  261.14  5001.4  260.64  5005.3  260.64  5005.6  261.14  5011.1  261.27
  5024.2  261.98  5032.5  263.85  5053.3  265.33  5059.6  265.27  5082.5  267.56
  5103.3  268.05  5109.6  267.57  5117.9  268.11  5142.5  267.92  5182.5  269.18
  5224.2  271.53  5252.2  273.70  5296.0  276.06  5467.9  288.12  5496.0  289.51
#Mann=6,-1,0
  4815.8     0.1       0  5001.1    0.05       0  5005.6     0.1       0
  5011.1    0.05       0  5142.5    0.12       0  5252.2    0.05       0
Bank Sta=5001.1,5005.6
Exp/Cntr=0.3,0.1

Type RM Length L Ch R = 1,14292,466,466,466
BEGIN DESCRIPTION:
Stream0762 25.0
END DESCRIPTION:
XS GIS Cut Line= 3
      2472824.96     13633825.03      2472425.00     13634125.00
      2472274.97     13634325.04
#Sta/Elev= 30
  4509.7  287.22  4697.6  274.95  4779.7  268.70  4790.8  268.32  4802.4  267.96
  4816.9  262.73  4831.5  260.54  4837.8  261.51  4846.1  258.82  4902.4  260.32
  4946.1  258.41  4987.8  260.07  5006.7  257.55  5020.9  257.45  5021.2  256.95
  5025.5  257.45  5031.5  257.48  5037.8  260.61  5046.1  259.73  5052.4  265.93
  5066.9  262.09  5077.0  263.27  5081.5  262.93  5087.8  265.29  5096.1  263.49
  5102.4  266.49  5109.7  264.41  5123.2  265.15  5152.4  270.17  5259.7  274.63
#Mann=8,-1,0
  4509.7    0.05       0  4697.6    0.07       0  4779.7    0.05       0
  4790.8    0.12       0  5006.7    0.07       0  5020.9    0.05       0
  5025.5    0.07       0  5077.0    0.05       0
Bank Sta=5020.9,5025.5
Exp/Cntr=0.3,0.1

Type RM Length L Ch R = 1,13826,428,428,428
BEGIN DESCRIPTION:
Stream0762 24.0
END DESCRIPTION:
XS GIS Cut Line= 3
      2472624.99     13633625.01      2472225.00     13633825.00
      2472075.01     13633875.00
#Sta/Elev= 30
  4552.5  280.00  4554.5  280.00  4727.8  269.62  4753.7  268.28  4762.1  267.37
  4779.3  266.71  4834.8  263.85  4879.5  262.58  4887.9  262.07  4896.3  260.81
  4901.9  261.63  4918.6  259.66  4946.6  258.26  4963.4  256.43  4977.3  256.68
  4991.3  255.46  4994.6  254.31  4994.9  253.81  4998.9  253.81  4999.3  254.31
  5010.2  255.27  5020.8  257.27  5028.9  258.24  5041.9  261.11  5052.4  264.71
  5105.1  267.52  5115.6  268.54  5136.7  269.27  5148.0  270.73  5157.8  270.69
#Mann=8,-1,0
  4552.5   0.035       0  4554.5    0.07       0  4727.8    0.12       0
  4779.3    0.07       0  4994.6    0.05       0  4999.3    0.07       0
  5028.9    0.12       0  5148.0    0.07       0
Bank Sta=4994.6,4999.3
Exp/Cntr=0.3,0.1

Type RM Length L Ch R = 1,13398,421,421,421
BEGIN DESCRIPTION:
Stream0762 23.0
END DESCRIPTION:
XS GIS Cut Line= 3
      2472275.04     13633374.98      2472025.00     13633475.00
      2471874.99     13633575.01
#Sta/Elev= 30
  4730.7  267.02  4763.1  265.82  4769.8  265.11  4786.2  264.68  4847.9  262.60
  4877.5  261.19  4882.9  261.49  4892.3  260.95  4936.7  260.05  4950.5  257.42
  4967.7  253.41  4985.2  251.50  4988.2  250.76  4988.5  250.26  4992.6  250.26
  4993.0  250.76  4997.3  251.55  5003.0  251.55  5007.5  252.05  5019.5  253.96
  5028.6  255.57  5049.6  260.13  5072.1  262.75  5085.6  263.84  5094.7  264.11
  5108.2  265.50  5130.7  266.47  5151.7  268.20  5166.1  268.94  5180.3  269.84
#Mann=7,-1,0
  4730.7    0.07       0  4786.2    0.12       0  4950.5    0.07       0
  4988.2    0.05       0  4993.0    0.07       0  5019.5    0.12       0
  5166.1    0.07       0
Bank Sta=4988.2,4993
Exp/Cntr=0.3,0.1

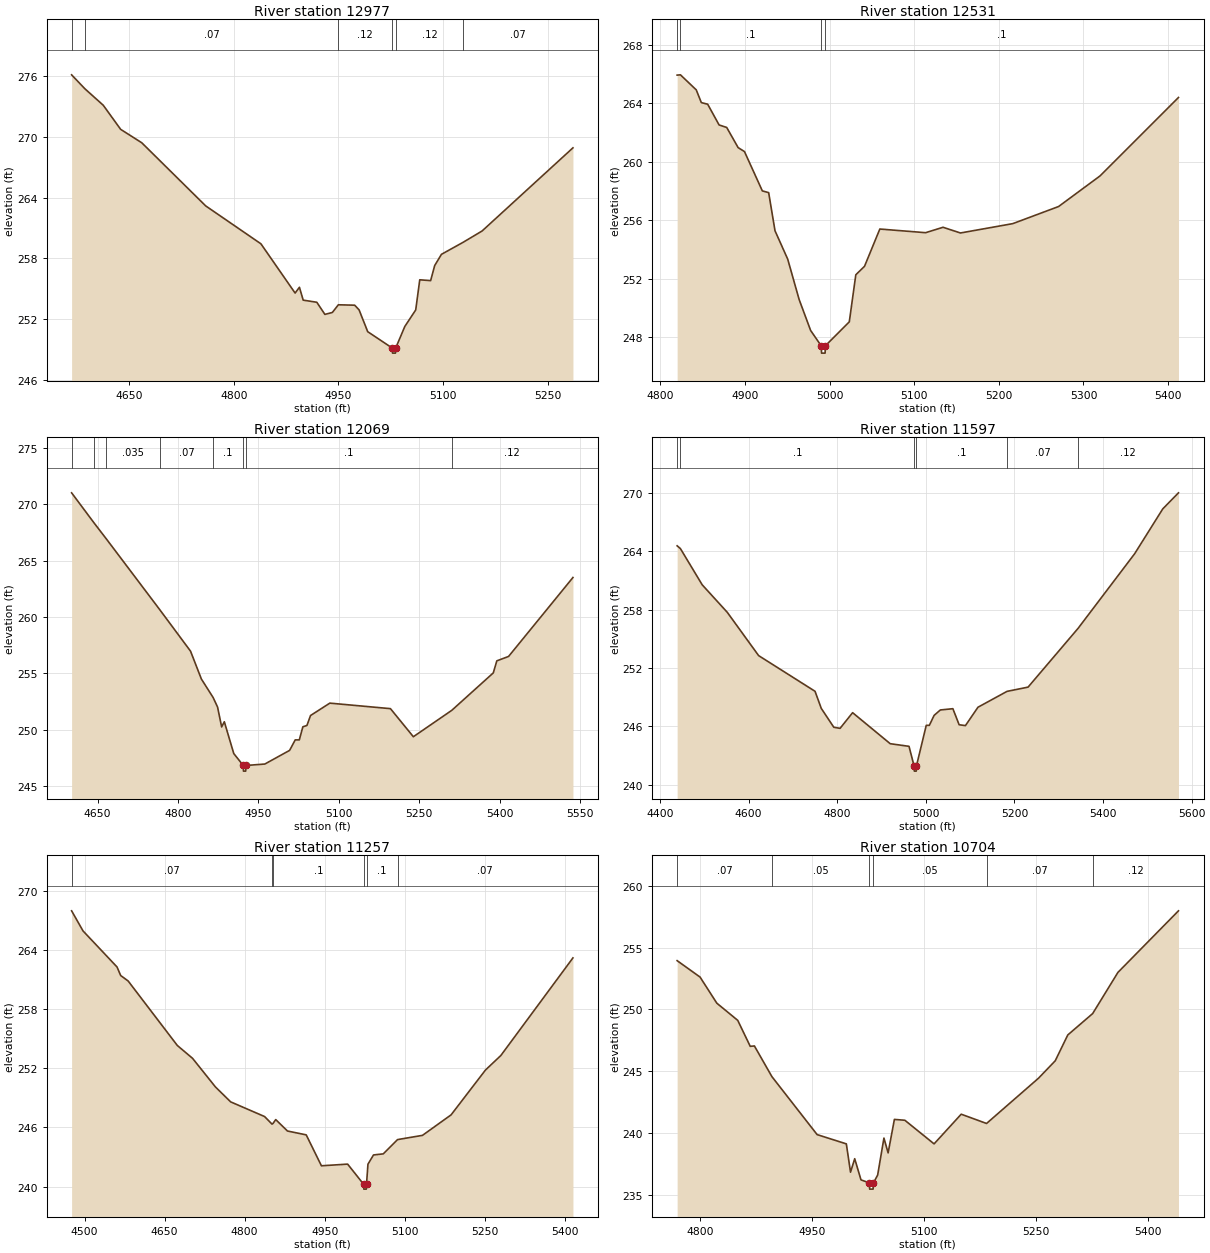
Type RM Length L Ch R = 1,12977,446,446,446
BEGIN DESCRIPTION:
Stream0762 22.0
END DESCRIPTION:
XS GIS Cut Line= 3
      2471975.00     13632725.01      2471825.00     13633125.00
      2471675.02     13633374.97
#Sta/Elev= 30
  4567.4  276.16  4586.3  274.79  4612.8  273.15  4637.7  270.77  4668.0  269.44
  4759.6  263.20  4838.8  259.45  4887.8  254.58  4894.0  255.15  4899.4  253.88
  4918.9  253.67  4930.5  252.47  4941.2  252.66  4949.8  253.42  4973.2  253.38
  4979.5  252.92  4991.9  250.76  5027.1  249.14  5027.5  248.64  5031.6  248.64
  5032.0  249.14  5045.1  251.28  5060.7  252.91  5066.5  255.89  5082.1  255.81
  5087.9  257.30  5097.6  258.41  5128.7  259.60  5155.9  260.72  5286.1  268.94
#Mann=6,-1,0
  4567.4    0.05       0  4586.3    0.07       0  4949.8    0.12       0
  5027.1    0.05       0  5032.0    0.12       0  5128.7    0.07       0
Bank Sta=5027.1,5032
Exp/Cntr=0.3,0.1

Type RM Length L Ch R = 1,12531,462,462,462
BEGIN DESCRIPTION:
Stream0762 21.0
END DESCRIPTION:
XS GIS Cut Line= 3
      2471625.01     13632674.98      2471525.00     13632825.00
      2471425.00     13633224.99
#Sta/Elev= 30
  4819.7  265.94  4823.6  265.96  4842.3  264.93  4848.3  264.06  4855.8  263.95
  4869.3  262.53  4878.3  262.36  4891.8  260.98  4899.3  260.71  4920.4  258.02
  4927.9  257.90  4935.4  255.29  4950.4  253.35  4963.9  250.59  4977.5  248.47
  4990.0  247.42  4990.4  246.92  4994.6  246.92  4994.9  247.42  5023.2  249.06
  5030.9  252.28  5041.2  252.86  5059.3  255.41  5113.4  255.16  5134.0  255.53
  5154.6  255.14  5216.5  255.78  5270.6  256.95  5319.5  259.04  5412.3  264.41
#Mann=4,-1,0
  4819.7   0.035       0  4823.6     0.1       0  4990.0    0.05       0
  4994.9     0.1       0
Bank Sta=4990,4994.9
Exp/Cntr=0.3,0.1

Type RM Length L Ch R = 1,12069,472,472,472
BEGIN DESCRIPTION:
Stream0762 20.0
END DESCRIPTION:
XS GIS Cut Line= 3
      2471625.00     13632475.00      2471225.00     13632525.00
      2470825.02     13632874.98
#Sta/Elev= 30
  4601.7  271.01  4643.1  268.37  4666.5  266.92  4766.0  260.65  4823.4  256.97
  4843.6  254.50  4865.5  252.86  4873.8  252.01  4881.4  250.25  4886.4  250.71
  4904.0  247.89  4921.7  246.83  4922.1  246.33  4926.3  246.33  4926.6  246.83
  4962.0  246.96  5008.1  248.17  5018.6  249.10  5026.2  249.10  5032.8  250.26
  5040.4  250.38  5047.1  251.26  5083.1  252.36  5196.1  251.87  5238.8  249.38
  5310.4  251.72  5387.8  255.04  5394.4  256.11  5416.3  256.50  5536.3  263.50
#Mann=8,-1,0
  4601.7   0.035       0  4643.1    0.07       0  4666.5   0.035       0
  4766.0    0.07       0  4865.5     0.1       0  4921.7    0.05       0
  4926.6     0.1       0  5310.4    0.12       0
Bank Sta=4921.7,4926.6
Exp/Cntr=0.3,0.1

Type RM Length L Ch R = 1,11597,340,340,340
BEGIN DESCRIPTION:
Stream0762 19.0
END DESCRIPTION:
XS GIS Cut Line= 3
      2471275.02     13631874.98      2470875.00     13632275.00
      2470475.00     13632675.00
#Sta/Elev= 30
  4438.9  264.58  4446.2  264.30  4495.5  260.57  4552.1  257.74  4622.8  253.29
  4750.1  249.62  4764.2  247.86  4792.5  245.92  4806.6  245.81  4834.9  247.42
  4919.8  244.23  4962.2  243.96  4973.8  241.91  4974.2  241.41  4978.5  241.41
  4978.8  241.91  5001.1  246.12  5008.1  246.12  5018.8  247.14  5032.9  247.70
  5061.2  247.83  5075.3  246.18  5089.5  246.09  5117.8  247.98  5183.3  249.61
  5230.9  250.05  5343.7  256.09  5471.3  263.76  5534.9  268.38  5570.3  270.03
#Mann=6,-1,0
  4438.9    0.07       0  4446.2     0.1       0  4973.8    0.05       0
  4978.8     0.1       0  5183.3    0.07       0  5343.7    0.12       0
Bank Sta=4973.8,4978.8
Exp/Cntr=0.3,0.1

Type RM Length L Ch R = 1,11257,553,553,553
BEGIN DESCRIPTION:
Stream0762 18.0
END DESCRIPTION:
XS GIS Cut Line= 3
      2471174.98     13631625.02      2470780.51     13631961.60
      2470375.01     13632075.00
#Sta/Elev= 30
  4475.7  268.00  4497.1  265.96  4560.8  262.30  4567.7  261.43  4581.6  260.88
  4673.8  254.33  4702.4  253.02  4745.2  250.12  4773.8  248.60  4837.4  247.11
  4851.3  246.34  4853.1  246.41  4858.3  246.80  4880.3  245.64  4915.4  245.25
  4943.9  242.11  4993.0  242.28  5022.9  240.24  5023.4  239.74  5028.0  239.74
  5028.4  240.24  5031.1  242.27  5041.5  243.21  5059.8  243.32  5086.6  244.77
  5133.3  245.20  5186.9  247.28  5251.3  251.83  5280.2  253.31  5415.3  263.22
#Mann=6,-1,0
  4475.7    0.07       0  4851.3    0.05       0  4853.1     0.1       0
  5022.9    0.05       0  5028.4     0.1       0  5086.6    0.07       0
Bank Sta=5022.9,5028.4
Exp/Cntr=0.3,0.1

Type RM Length L Ch R = 1,10704,454,454,454
BEGIN DESCRIPTION:
Stream0762 17.0
END DESCRIPTION:
XS GIS Cut Line= 3
      2470875.00     13631375.00      2470675.00     13631475.00
      2470275.02     13631674.99
#Sta/Elev= 30
  4769.4  253.94  4800.1  252.61  4822.5  250.50  4850.5  249.11  4867.2  247.01
  4872.8  247.04  4896.2  244.56  4956.7  239.87  4995.8  239.12  5001.4  236.83
  5007.0  237.92  5015.4  236.21  5026.6  235.96  5027.0  235.46  5031.6  235.46
  5032.1  235.96  5037.7  236.60  5046.1  239.59  5051.7  238.39  5060.1  241.10
  5074.1  241.03  5113.2  239.12  5149.5  241.52  5183.4  240.77  5252.9  244.43
  5275.3  245.84  5292.1  247.93  5325.4  249.66  5359.2  252.99  5440.2  257.97
#Mann=6,-1,0
  4769.4    0.07       0  4896.2    0.05       0  5026.6    0.05       0
  5032.1    0.05       0  5183.4    0.07       0  5325.4    0.12       0
Bank Sta=5026.6,5032.1
Exp/Cntr=0.3,0.1

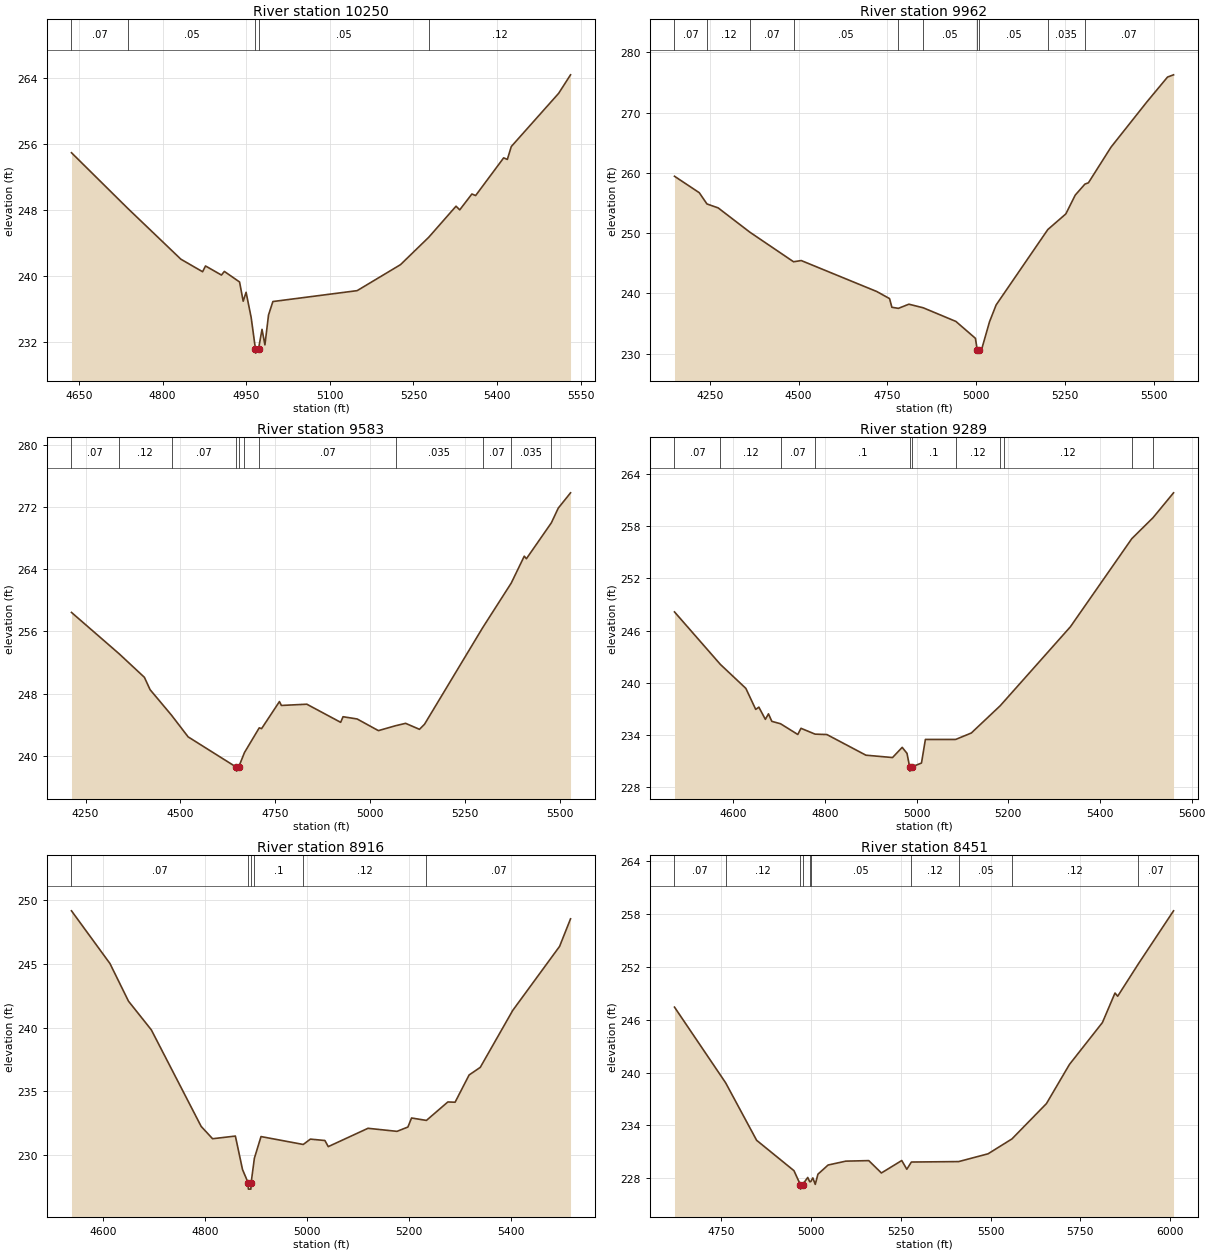
Type RM Length L Ch R = 1,10250,288,288,288
BEGIN DESCRIPTION:
Stream0762 16.0
END DESCRIPTION:
XS GIS Cut Line= 3
      2470875.01     13631175.00      2470525.00     13631075.00
      2470125.02     13631424.98
#Sta/Elev= 30
  4636.5  254.95  4737.0  248.24  4832.8  242.05  4871.8  240.53  4877.0  241.23
  4905.6  240.13  4910.8  240.57  4938.1  239.29  4944.6  236.96  4949.8  238.04
  4958.9  235.00  4966.6  231.17  4967.0  230.67  4972.1  231.17  4978.4  233.55
  4983.6  231.67  4990.1  235.30  4997.9  236.92  5149.1  238.24  5226.9  241.39
  5277.6  244.71  5326.5  248.47  5333.2  248.03  5355.0  249.95  5361.7  249.76
  5412.0  254.33  5418.6  254.14  5425.7  255.70  5510.7  262.15  5532.0  264.39
#Mann=5,-1,0
  4636.5    0.07       0  4737.0    0.05       0  4966.6    0.05       0
  4972.1    0.05       0  5277.6    0.12       0
Bank Sta=4966.6,4972.1
Exp/Cntr=0.3,0.1

Type RM Length L Ch R = 1,9962,379,379,379
BEGIN DESCRIPTION:
Stream0762 15.0
END DESCRIPTION:
XS GIS Cut Line= 3
      2471120.57     13631086.60      2470430.36     13630835.62
      2469792.40     13631044.78
#Sta/Elev= 30
  4150.4  259.45  4220.2  256.72  4241.9  254.85  4273.4  254.20  4362.7  250.17
  4485.8  245.26  4507.5  245.46  4720.3  240.32  4756.2  239.15  4762.8  237.71
  4781.2  237.53  4810.7  238.22  4851.2  237.62  4943.1  235.36  4998.1  232.56
  5003.4  230.60  5003.9  230.10  5009.0  230.60  5016.8  230.97  5037.8  235.30
  5056.5  238.10  5202.1  250.61  5252.8  253.20  5279.3  256.32  5306.6  258.15
  5316.4  258.36  5380.1  264.28  5480.9  271.77  5539.3  275.91  5556.2  276.28
#Mann=10,-1,0
  4150.4    0.07       0  4241.9    0.12       0  4362.7    0.07       0
  4485.8    0.05       0  4781.2    0.07       0  4851.2    0.05       0
  5003.4    0.05       0  5009.0    0.05       0  5202.1   0.035       0
  5306.6    0.07       0
Bank Sta=5003.4,5009
Exp/Cntr=0.3,0.1

Type RM Length L Ch R = 1,9583,294,294,294
BEGIN DESCRIPTION:
E21333
END DESCRIPTION:
XS GIS Cut Line= 5
      2471051.80     13630551.58      2470568.53     13630572.80
      2470358.74     13630532.72      2470196.09     13630660.02
      2469829.16     13630843.48
#Sta/Elev= 30
  4213.0  258.45  4338.2  253.14  4405.0  250.10  4420.0  248.51  4476.5  245.22
  4520.1  242.44  4647.4  238.53  4647.9  238.03  4653.0  238.53  4668.5  240.42
  4707.4  243.60  4713.6  243.50  4760.6  246.98  4765.7  246.48  4832.7  246.64
  4921.8  244.31  4928.1  245.03  4965.2  244.74  5021.2  243.24  5066.2  243.87
  5092.8  244.18  5129.3  243.41  5142.6  244.06  5295.8  256.49  5371.0  262.23
  5405.3  265.69  5410.9  265.36  5476.6  269.98  5494.8  271.87  5527.1  273.84
#Mann=11,-1,0
  4213.0    0.07       0  4338.2    0.12       0  4476.5    0.07       0
  4647.4    0.05       0  4653.0    0.07       0  4668.5     0.1       0
  4707.4    0.07       0  5066.2   0.035       0  5295.8    0.07       0
  5371.0   0.035       0  5476.6    0.07       0
Bank Sta=4647.4,4653
Exp/Cntr=0.3,0.1

Type RM Length L Ch R = 1,9289,373,373,373
BEGIN DESCRIPTION:
Stream0762 14.0
END DESCRIPTION:
XS GIS Cut Line= 3
      2470725.01     13629974.99      2470379.95     13630294.64
      2469793.44     13630490.15
#Sta/Elev= 30
  4471.9  248.15  4572.0  242.12  4627.5  239.37  4649.1  236.95  4655.9  237.21
  4670.1  235.81  4676.9  236.44  4684.2  235.58  4703.3  235.30  4740.9  234.07
  4747.8  234.78  4778.6  234.11  4804.4  234.06  4889.5  231.69  4947.5  231.42
  4968.6  232.59  4979.1  231.90  4984.8  230.36  4985.3  229.86  4990.4  230.36
  5010.7  230.79  5019.2  233.50  5085.3  233.50  5119.4  234.24  5182.4  237.37
  5190.0  237.82  5335.5  246.44  5469.4  256.56  5515.9  258.98  5560.5  261.83
#Mann=11,-1,0
  4471.9    0.07       0  4572.0    0.12       0  4703.3    0.07       0
  4778.6     0.1       0  4984.8    0.05       0  4990.4     0.1       0
  5085.3    0.12       0  5182.4    0.07       0  5190.0    0.12       0
  5469.4    0.07       0  5515.9   0.035       0
Bank Sta=4984.8,4990.4
Exp/Cntr=0.3,0.1

Type RM Length L Ch R = 1,8916,465,465,465
BEGIN DESCRIPTION:
Stream0762 13.0
END DESCRIPTION:
XS GIS Cut Line= 3
      2470674.96     13629775.02      2470275.00     13629975.00
      2469874.98     13630325.02
#Sta/Elev= 30
  4537.4  249.18  4612.8  245.04  4649.2  242.08  4693.9  239.83  4791.7  232.24
  4814.1  231.27  4858.8  231.48  4872.8  228.85  4883.8  227.81  4884.3  227.31
  4889.2  227.31  4889.7  227.81  4896.1  229.74  4909.1  231.44  4991.9  230.82
  5005.9  231.24  5034.4  231.13  5041.0  230.65  5118.9  232.09  5175.8  231.85
  5197.2  232.19  5204.3  232.90  5233.5  232.71  5275.5  234.16  5289.7  234.14
  5317.2  236.28  5339.1  236.88  5402.7  241.35  5494.7  246.39  5516.1  248.55
#Mann=6,-1,0
  4537.4    0.07       0  4883.8    0.05       0  4889.7    0.07       0
  4896.1     0.1       0  4991.9    0.12       0  5233.5    0.07       0
Bank Sta=4883.8,4889.7
Exp/Cntr=0.3,0.1

Type RM Length L Ch R = 1,8451,441,441,441
BEGIN DESCRIPTION:
Stream0762 12.0
END DESCRIPTION:
XS GIS Cut Line= 3
      2470625.04     13629675.01      2470275.00     13629575.00
      2469524.97     13630275.03
#Sta/Elev= 30
  4619.7  247.41  4762.1  238.84  4848.5  232.32  4952.5  228.88  4970.3  227.29
  4970.8  226.79  4976.3  227.29  4990.8  228.11  4996.4  227.63  4999.3  227.64
  5005.0  228.06  5011.8  227.33  5019.2  228.48  5047.5  229.52  5096.8  229.96
  5160.8  230.02  5196.0  228.62  5252.7  230.03  5266.8  229.04  5279.5  229.86
  5411.2  229.91  5493.0  230.79  5559.7  232.48  5655.7  236.48  5719.7  240.91
  5811.6  245.66  5846.7  249.01  5854.1  248.64  5911.1  252.27  6009.7  258.32
#Mann=10,-1,0
  4619.7    0.07       0  4762.1    0.12       0  4970.3    0.05       0
  4976.3    0.12       0  4996.4     0.1       0  4999.3    0.05       0
  5279.5    0.12       0  5411.2    0.05       0  5559.7    0.12       0
  5911.1    0.07       0
Bank Sta=4970.3,4976.3
Exp/Cntr=0.3,0.1