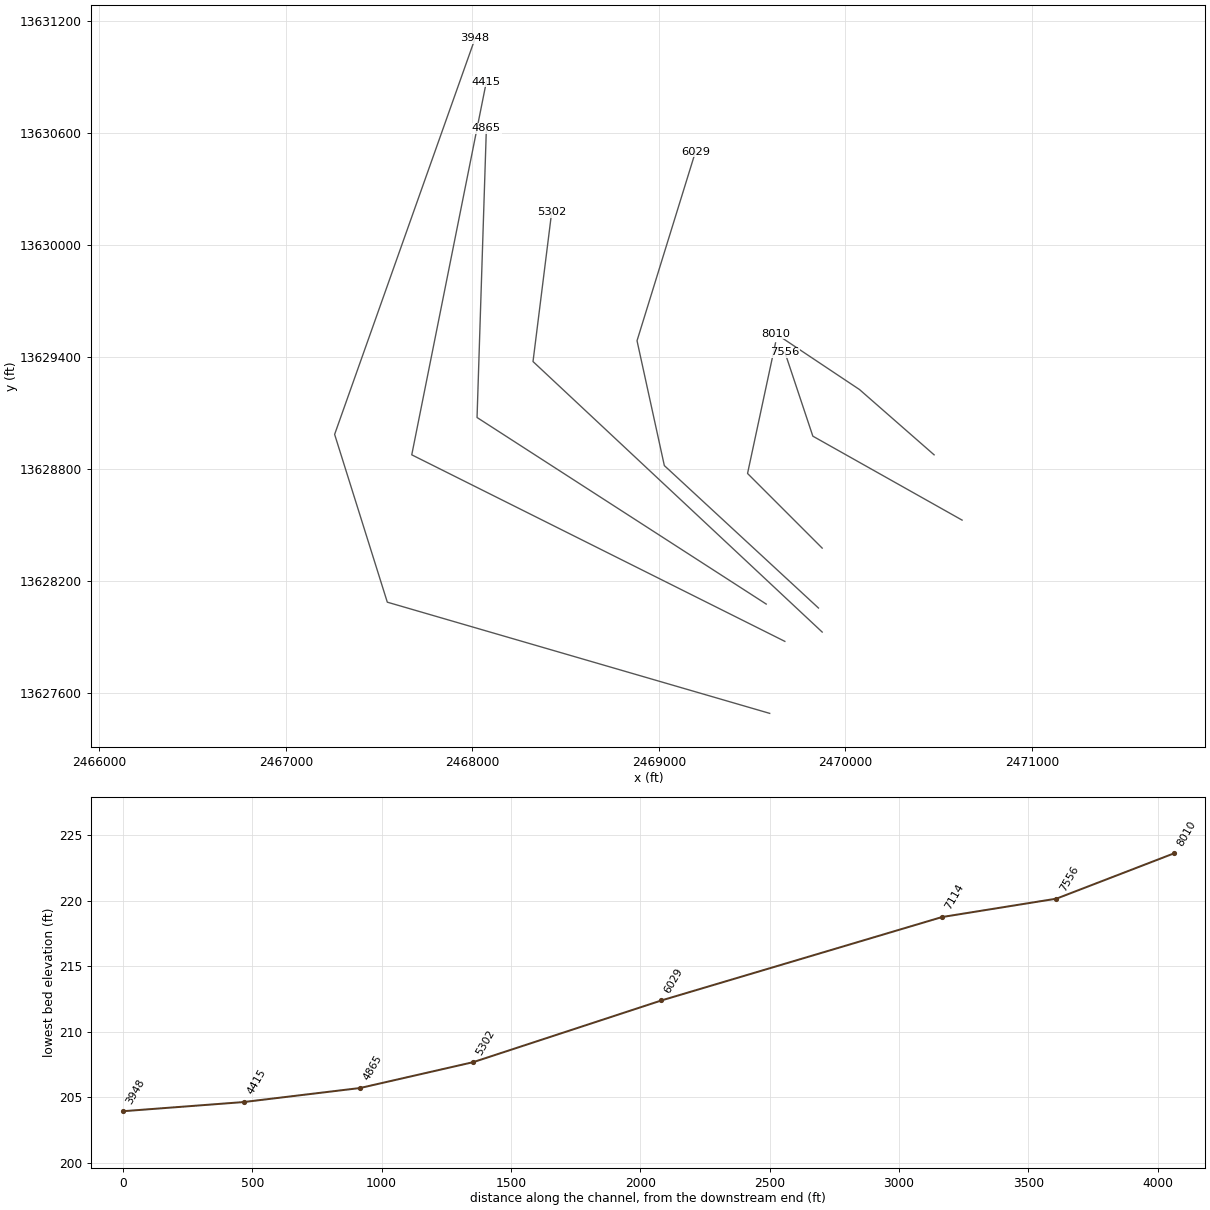
HEC-RAS study Stream0762.prj: Stream0762 Base Level Engineering

--- Stream0762.g01 (geometry) --- (continued)

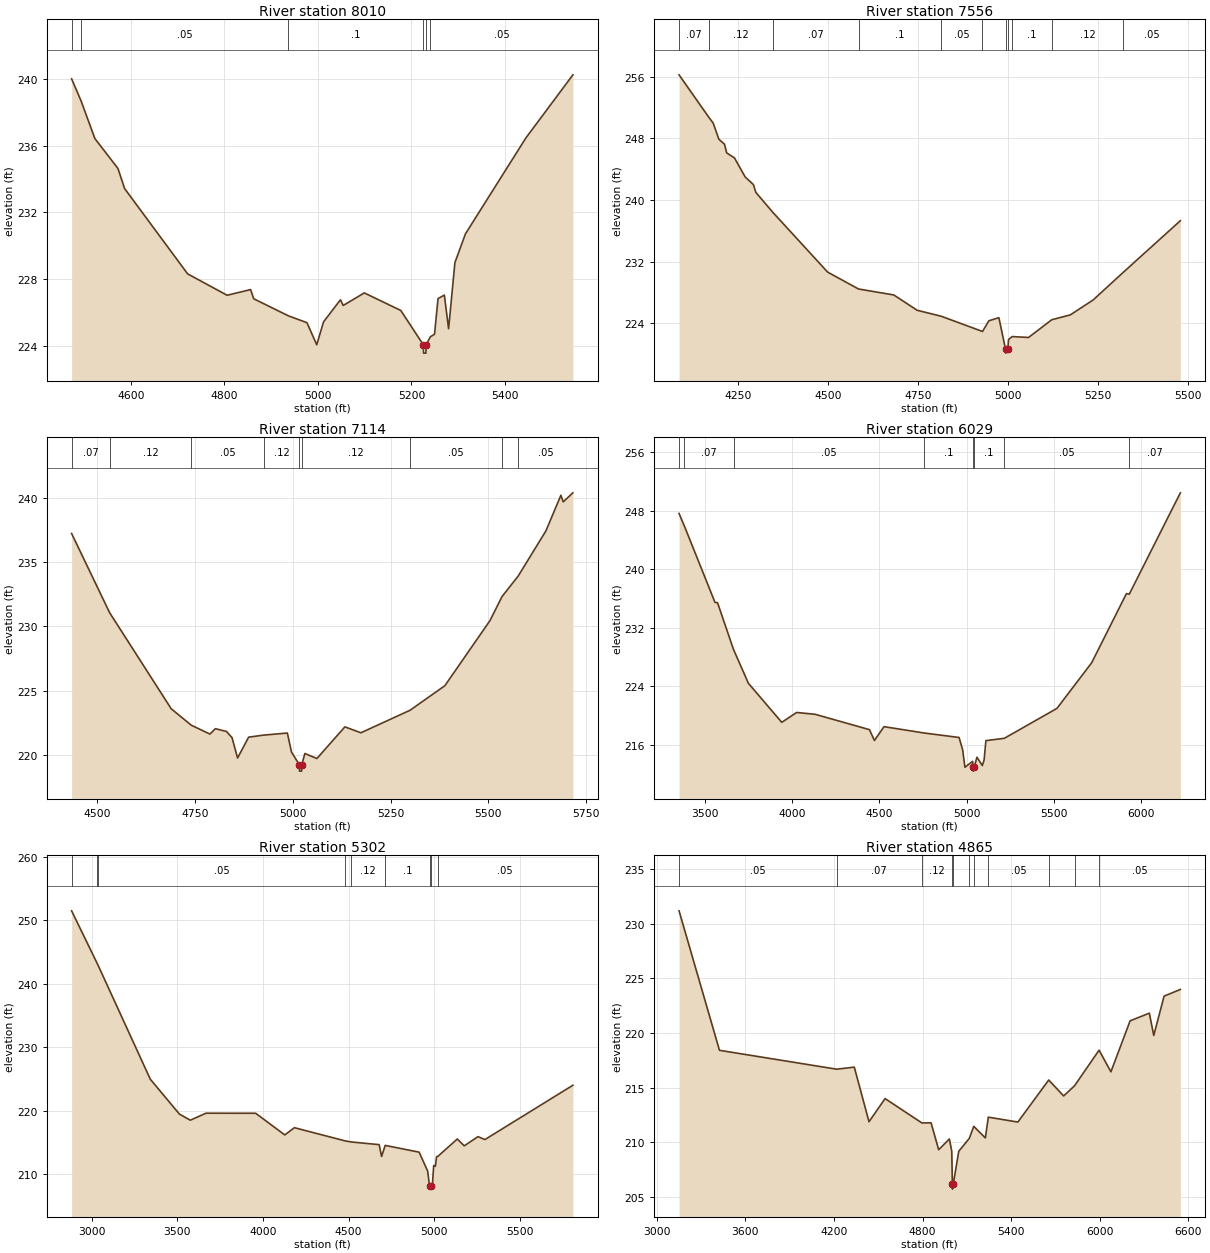
Type RM Length L Ch R = 1,8010,454,454,454
BEGIN DESCRIPTION:
Stream0762 11.0
END DESCRIPTION:
XS GIS Cut Line= 3
      2470475.01     13628874.99      2470075.00     13629225.00
      2469624.97     13629525.02
#Sta/Elev= 30
  4473.1  239.99  4493.4  238.67  4522.9  236.42  4572.3  234.63  4586.5  233.43
  4721.3  228.33  4805.8  227.05  4856.1  227.39  4862.7  226.84  4936.9  225.82
  4976.6  225.41  4997.5  224.09  5012.1  225.46  5048.2  226.78  5054.2  226.44
  5099.3  227.19  5177.4  226.14  5225.5  224.09  5226.0  223.59  5231.0  223.59
  5231.5  224.09  5240.6  224.57  5249.5  224.72  5257.0  226.85  5270.5  227.06
  5279.6  225.05  5293.1  229.00  5315.6  230.72  5444.8  236.45  5545.5  240.23
#Mann=6,-1,0
  4473.1    0.07       0  4493.4    0.05       0  4936.9     0.1       0
  5225.5    0.05       0  5231.5     0.1       0  5240.6    0.05       0
Bank Sta=5225.5,5231.5
Exp/Cntr=0.3,0.1

Type RM Length L Ch R = 1,7556,442,442,442
BEGIN DESCRIPTION:
Stream0762 10.0
END DESCRIPTION:
XS GIS Cut Line= 3
      2470625.00     13628525.00      2469825.00     13628975.00
      2469675.01     13629424.98
#Sta/Elev= 30
  4086.7  256.25  4168.9  250.77  4181.4  250.00  4197.3  247.89  4212.9  247.25
  4219.0  246.12  4240.6  245.47  4270.3  243.00  4293.2  242.01  4299.9  241.00
  4346.9  238.42  4499.4  230.65  4585.2  228.46  4683.0  227.69  4748.0  225.70
  4814.6  224.93  4929.4  222.95  4947.2  224.34  4974.9  224.74  4993.5  220.64
  4994.0  220.14  4999.7  220.64  5001.7  221.90  5011.9  222.29  5057.3  222.17
  5121.7  224.47  5173.2  225.10  5236.5  227.03  5320.5  230.63  5478.9  237.32
#Mann=11,-1,0
  4086.7    0.07       0  4168.9    0.12       0  4346.9    0.07       0
  4585.2     0.1       0  4814.6    0.05       0  4929.4    0.12       0
  4993.5    0.05       0  4999.7    0.12       0  5011.9     0.1       0
  5121.7    0.12       0  5320.5    0.05       0
Bank Sta=4993.5,4999.7
Exp/Cntr=0.3,0.1

Type RM Length L Ch R = 1,7114,1085,1085,1085
BEGIN DESCRIPTION:
Stream0762 9.0
END DESCRIPTION:
XS GIS Cut Line= 3
      2469875.02     13628374.98      2469475.00     13628775.00
      2469625.00     13629474.99
#Sta/Elev= 30
  4434.5  237.21  4531.8  231.05  4689.1  223.59  4740.4  222.31  4788.1  221.62
  4802.2  222.04  4830.5  221.82  4844.7  221.34  4858.8  219.76  4887.1  221.38
  4925.7  221.54  4986.1  221.70  4996.7  220.22  5016.7  219.24  5017.2  218.74
  5022.5  218.74  5023.0  219.24  5030.9  220.11  5061.6  219.72  5133.2  222.18
  5174.1  221.72  5299.7  223.47  5388.8  225.38  5503.9  230.43  5535.0  232.31
  5576.0  233.89  5647.1  237.41  5685.4  240.18  5691.4  239.67  5716.1  240.37
#Mann=9,-1,0
  4434.5    0.07       0  4531.8    0.12       0  4740.4    0.05       0
  4925.7    0.12       0  5016.7    0.05       0  5023.0    0.12       0
  5299.7    0.05       0  5535.0    0.12       0  5576.0    0.05       0
Bank Sta=5016.7,5023
Exp/Cntr=0.3,0.1

Type RM Length L Ch R = 1,6029,727,727,727
BEGIN DESCRIPTION:
XS7681
END DESCRIPTION:
XS GIS Cut Line= 4
      2469855.16     13628053.77      2469028.98     13628817.21
      2468882.57     13629486.52      2469196.01     13630500.01
#Sta/Elev= 30
  3353.2  247.61  3383.8  245.88  3559.2  235.44  3573.4  235.42  3665.0  229.02
  3750.3  224.39  3941.4  219.05  4026.4  220.40  4132.5  220.15  4443.7  218.05
  4472.1  216.57  4527.0  218.46  4757.4  217.59  4957.0  216.98  4977.4  215.28
  4990.4  212.91  5034.3  213.72  5036.3  212.88  5036.8  212.38  5042.6  212.88
  5059.3  214.28  5090.0  213.14  5100.3  213.91  5110.5  216.55  5216.3  216.87
  5517.5  220.96  5716.4  227.20  5915.3  236.65  5931.5  236.57  6224.1  250.43
#Mann=8,-1,0
  3353.2    0.05       0  3383.8    0.07       0  3665.0    0.05       0
  4757.4     0.1       0  5036.3    0.05       0  5042.6     0.1       0
  5216.3    0.05       0  5931.5    0.07       0
Bank Sta=5036.3,5042.6
Exp/Cntr=0.3,0.1

Type RM Length L Ch R = 1,5302,437,437,437
BEGIN DESCRIPTION:
Stream0762 8.0
END DESCRIPTION:
XS GIS Cut Line= 3
      2469875.03     13627924.97      2468325.00     13629375.00
      2468425.00     13630175.04
#Sta/Elev= 30
  2881.8  251.48  3031.6  243.19  3035.7  242.96  3341.8  224.97  3511.7  219.49
  3575.3  218.53  3667.1  219.63  3957.3  219.62  4127.2  216.21  4183.4  217.35
  4480.4  215.27  4516.4  215.10  4678.8  214.68  4692.9  212.82  4714.0  214.56
  4912.3  213.50  4962.1  210.52  4973.0  208.18  4973.5  207.68  4979.4  208.18
  4990.4  208.60  4997.3  211.40  5006.9  211.27  5014.4  212.79  5020.6  212.81
  5135.3  215.57  5175.7  214.49  5256.3  215.94  5296.6  215.48  5810.6  224.03
#Mann=9,-1,0
  2881.8    0.05       0  3031.6    0.07       0  3035.7    0.05       0
  4480.4    0.07       0  4516.4    0.12       0  4714.0     0.1       0
  4973.0    0.05       0  4979.4     0.1       0  5020.6    0.05       0
Bank Sta=4973,4979.4
Exp/Cntr=0.3,0.1

Type RM Length L Ch R = 1,4865,450,450,450
BEGIN DESCRIPTION:
Stream0762 7.0
END DESCRIPTION:
XS GIS Cut Line= 3
      2469574.98     13628075.01      2468025.00     13629075.00
      2468075.00     13630625.03
#Sta/Elev= 30
  3150.8  231.19  3424.5  218.42  4218.4  216.69  4337.7  216.88  4437.4  211.88
  4546.3  214.00  4795.6  211.77  4857.8  211.78  4909.2  209.32  4981.8  210.30
  4997.9  209.19  5002.1  206.21  5002.6  205.71  5008.6  206.21  5045.4  209.18
  5116.9  210.36  5146.9  211.46  5225.5  210.40  5245.5  212.30  5445.6  211.85
  5654.6  215.70  5755.8  214.24  5829.4  215.17  5995.6  218.43  6075.9  216.45
  6206.0  221.12  6336.1  221.82  6366.1  219.78  6436.1  223.38  6546.2  223.99
#Mann=11,-1,0
  3150.8    0.05       0  4218.4    0.07       0  4795.6    0.12       0
  5002.1    0.05       0  5008.6    0.12       0  5116.9     0.1       0
  5146.9    0.07       0  5245.5    0.05       0  5654.6     0.1       0
  5829.4    0.07       0  5995.6    0.05       0
Bank Sta=5002.1,5008.6
Exp/Cntr=0.3,0.1

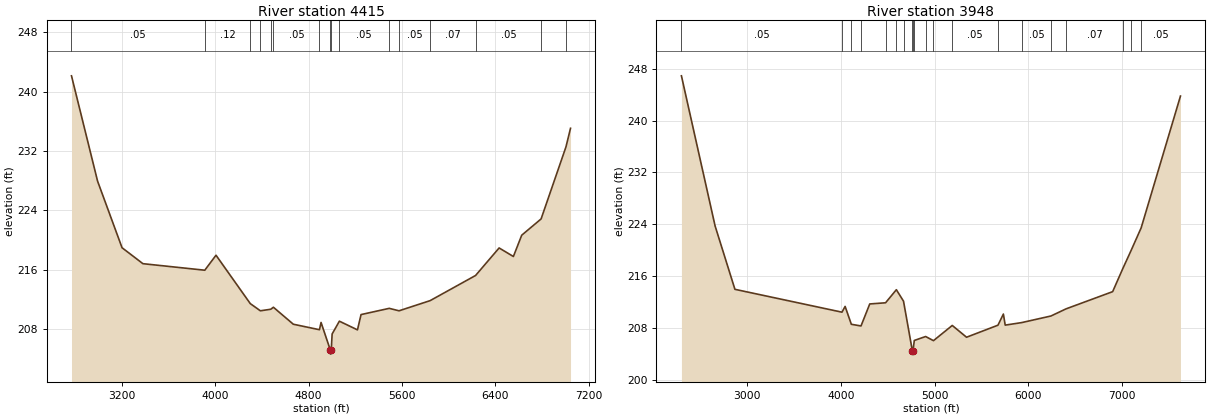
Type RM Length L Ch R = 1,4415,467,467,467
BEGIN DESCRIPTION:
Stream0762 6.0
END DESCRIPTION:
XS GIS Cut Line= 3
      2469674.97     13627875.01      2467675.00     13628875.00
      2468074.99     13630874.96
#Sta/Elev= 30
  2768.5  242.15  2992.1  227.95  3201.7  218.98  3380.6  216.83  3910.5  215.95
  4006.7  217.97  4300.3  211.45  4386.7  210.48  4476.2  210.69  4498.3  210.96
  4669.1  208.67  4893.0  207.93  4906.7  208.91  4987.3  205.14  4987.8  204.64
  4993.8  205.14  5001.7  207.36  5063.7  209.08  5218.7  207.91  5249.3  209.97
  5490.5  210.81  5574.8  210.48  5841.3  211.85  6230.6  215.24  6432.3  218.95
  6554.6  217.80  6626.0  220.67  6791.9  222.86  7005.0  232.57  7044.1  235.08
#Mann=16,-1,0
  2768.5    0.05       0  3910.5    0.12       0  4300.3    0.07       0
  4386.7    0.05       0  4476.2    0.07       0  4498.3    0.05       0
  4893.0    0.12       0  4987.3    0.05       0  4993.8    0.12       0
  5063.7    0.05       0  5490.5   0.035       0  5574.8    0.05       0
  5841.3    0.07       0  6230.6    0.05       0  6791.9    0.12       0
  7005.0    0.05       0
Bank Sta=4987.3,4993.8
Exp/Cntr=0.3,0.1

Type RM Length L Ch R = 1,3948,0,0,0
BEGIN DESCRIPTION:
XS7680
END DESCRIPTION:
XS GIS Cut Line= 4
      2469593.75     13627489.02      2467543.93     13628085.14
      2467261.56     13628984.54      2468014.55     13631107.54
#Sta/Elev= 30
  2295.7  246.93  2655.5  223.73  2867.1  213.95  4010.4  210.42  4044.0  211.31
  4110.4  208.55  4213.7  208.29  4307.1  211.69  4475.9  211.87  4591.4  213.89
  4667.8  212.12  4762.4  204.44  4762.9  203.94  4769.0  204.44  4782.9  206.05
  4904.0  206.66  4987.6  206.02  5188.3  208.37  5340.9  206.55  5676.5  208.41
  5734.4  210.13  5753.8  208.42  5930.0  208.81  6242.5  209.83  6403.3  210.93
  6901.5  213.59  7008.2  217.10  7092.9  219.77  7205.8  223.44  7625.7  243.80
#Mann=20,-1,0
  2295.7    0.05       0  4010.4   0.035       0  4110.4    0.05       0
  4213.7    0.07       0  4475.9    0.05       0  4591.4    0.12       0
  4667.8    0.05       0  4762.4    0.05       0  4769.0    0.05       0
  4782.9    0.12       0  4904.0     0.1       0  4987.6    0.12       0
  5188.3    0.05       0  5676.5    0.07       0  5930.0    0.05       0
  6242.5   0.035       0  6403.3    0.07       0  7008.2    0.05       0
  7092.9    0.12       0  7205.8    0.05       0
Bank Sta=4762.4,4769
Exp/Cntr=0.3,0.1

Chan Stop Cuts=-1