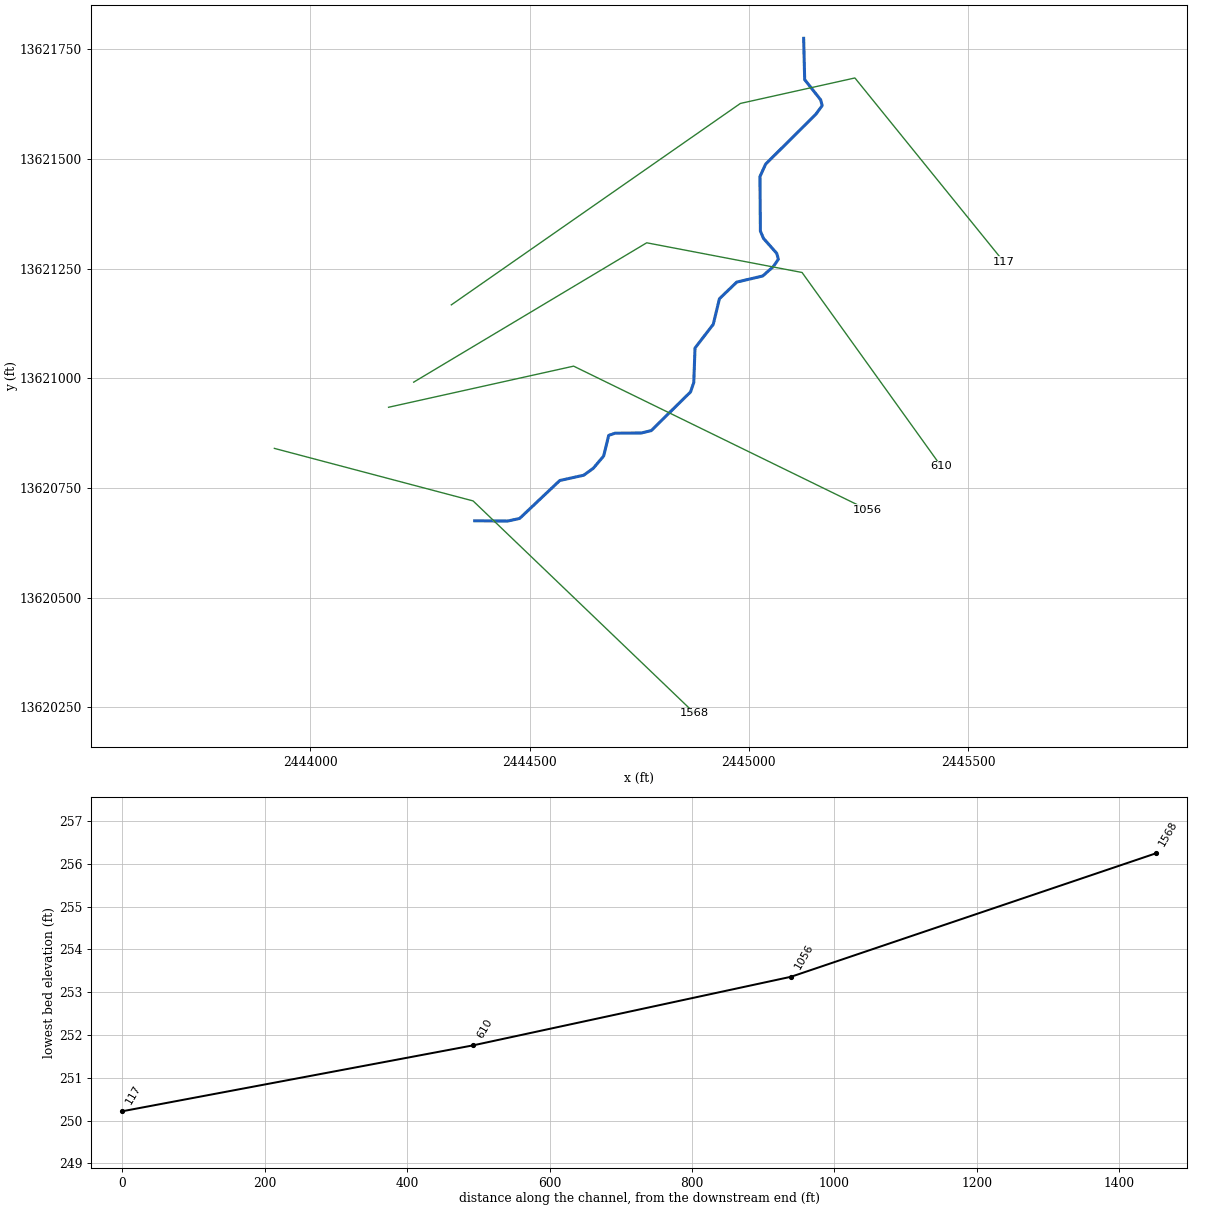
--- Stream0764.prj (project) ---

Proj Title=Stream0764 Base Level Engineering
Current Plan=p01
Default Exp/Contr=0.3,0.1
English Units
Geom File=g01
Flow File=f01
Plan File=p01
BEGIN DESCRIPTION:
Stream0764
END DESCRIPTION:

--- Stream0764.p01 (plan) ---

Plan Title=Multiple Run
Short Identifier=Multiple
Geom File=g01
Flow File=f01
Subcritical Flow
K Sum by GR= 0
Std Step Tol= 0.01
Critical Tol= 0.01
Num of Std Step Trials= 20
Max Error Tol= 0.3
Flow Tol Ratio= 0.001
Split Flow NTrial= 30
Split Flow Tol= 0.02
Split Flow Ratio= 0.02
Log Output Level= 0
Friction Slope Method= 1
Unsteady Friction Slope Method= 2
Unsteady Bridges Friction Slope Method= 1
Parabolic Critical Depth
Global Vel Dist=  1 , 1 , 1
Global Log Level= 0
CheckData=True
Encroach Param= -1, 0, 0, 0
BEGIN DESCRIPTION:
Multiple Run
END DESCRIPTION:

--- Stream0764.f01 (steady flow) ---

Flow Title=Multiple
Number of Profiles=7
Profile Names=10-year,25-year,50-year,1pct_min,100-year,1pct_plu,500-year
River Rch & RM= Stream0764,Reach-1,1568
     721    1172    1584    1037    2068    4127    3492
Boundary for River Rch & Prof#=Stream0764,Reach-1,1
Up Type=0
Dn Type=3
Dn Slope=0.005
Boundary for River Rch & Prof#=Stream0764,Reach-1,2
Up Type=0
Dn Type=3
Dn Slope=0.005
Boundary for River Rch & Prof#=Stream0764,Reach-1,3
Up Type=0
Dn Type=3
Dn Slope=0.005
Boundary for River Rch & Prof#=Stream0764,Reach-1,4
Up Type=0
Dn Type=3
Dn Slope=0.005
Boundary for River Rch & Prof#=Stream0764,Reach-1,5
Up Type=0
Dn Type=3
Dn Slope=0.005
Boundary for River Rch & Prof#=Stream0764,Reach-1,6
Up Type=0
Dn Type=3
Dn Slope=0.005
Boundary for River Rch & Prof#=Stream0764,Reach-1,7
Up Type=0
Dn Type=3
Dn Slope=0.005

--- Stream0764.g01 (geometry) ---

Geom Title=Existing Conditions

River Reach=Stream0764,Reach-1
Reach XY= 30
      2444375.00     13620675.00      2444450.24     13620674.41
      2444477.49     13620680.36      2444568.98     13620766.82
      2444623.55     13620778.92      2444645.43     13620794.74
      2444669.09     13620822.85      2444680.48     13620869.71
      2444695.27     13620874.77      2444754.79     13620875.19
      2444777.38     13620880.54      2444867.15     13620968.81
      2444874.48     13620990.21      2444877.33     13621069.03
      2444918.85     13621122.85      2444933.03     13621181.34
      2444972.51     13621219.25      2445031.67     13621233.16
      2445055.87     13621254.58      2445067.31     13621271.33
      2445063.72     13621284.71      2445033.48     13621318.79
      2445026.38     13621335.43      2445025.37     13621459.84
      2445038.37     13621488.32      2445152.55     13621601.64
      2445167.24     13621621.59      2445163.76     13621634.85
      2445127.35     13621680.77      2445125.00     13621775.00

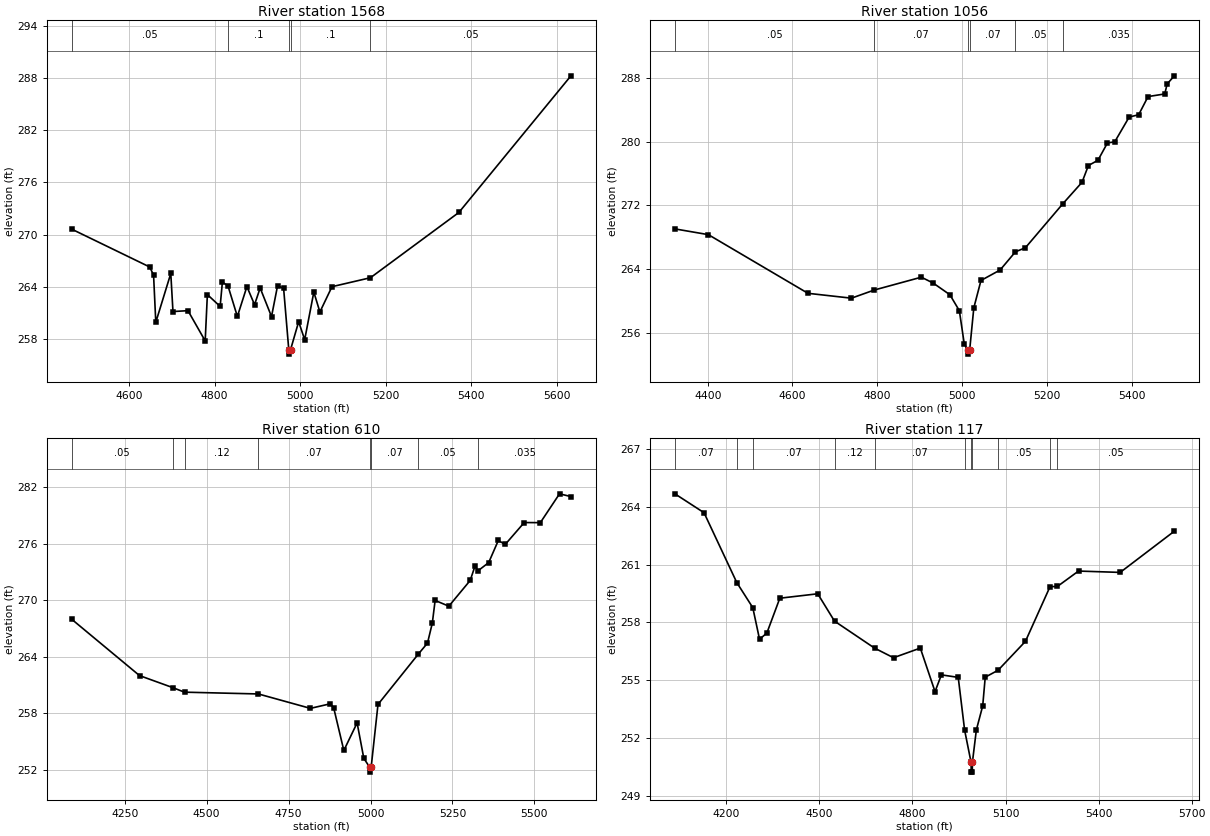
Type RM Length L Ch R = 1,1568,512,512,512
BEGIN DESCRIPTION:
XS7686
END DESCRIPTION:
XS GIS Cut Line= 3
      2443918.25     13620840.10      2444371.35     13620720.31
      2444876.58     13620235.92
#Sta/Elev= 30
  4465.0  270.63  4647.8  266.27  4657.0  265.35  4662.2  259.90  4697.3  265.52
  4702.4  261.14  4737.5  261.24  4777.8  257.76  4782.9  263.09  4812.8  261.73
  4818.0  264.52  4831.0  264.11  4853.1  260.57  4875.4  264.01  4893.3  261.93
  4906.4  263.85  4933.0  260.56  4947.1  264.10  4961.3  263.81  4973.4  256.74
  4973.7  256.24  4977.5  256.74  4996.5  259.97  5010.6  257.90  5032.0  263.38
  5046.2  261.09  5074.5  264.00  5164.5  265.03  5371.4  272.54  5633.6  288.26
#Mann=5,-1,0
  4465.0    0.05       0  4831.0     0.1       0  4973.4    0.05       0
  4977.5     0.1       0  5164.5    0.05       0
Bank Sta=4973.4,4977.5
Exp/Cntr=0.3,0.1

Type RM Length L Ch R = 1,1056,446,446,446
BEGIN DESCRIPTION:
XS7685
END DESCRIPTION:
XS GIS Cut Line= 3
      2444178.64     13620933.85      2444600.52     13621027.60
      2445270.70     13620700.31
#Sta/Elev= 30
  4322.7  269.05  4401.6  268.33  4636.5  260.98  4739.0  260.37  4792.8  261.39
  4903.9  263.00  4932.0  262.26  4971.3  260.80  4993.6  258.80  5005.2  254.63
  5013.8  253.86  5014.0  253.36  5017.9  253.86  5027.7  259.16  5044.6  262.59
  5089.7  263.90  5125.9  266.18  5149.4  266.69  5237.0  272.16  5282.9  274.89
  5298.0  276.99  5320.5  277.65  5343.0  279.83  5360.0  279.95  5394.2  283.07
  5416.5  283.35  5438.7  285.63  5478.1  285.96  5483.7  287.21  5500.7  288.23
#Mann=6,-1,0
  4322.7    0.05       0  4792.8    0.07       0  5013.8    0.05       0
  5017.9    0.07       0  5125.9    0.05       0  5237.0   0.035       0
Bank Sta=5013.8,5017.9
Exp/Cntr=0.3,0.1

Type RM Length L Ch R = 1,610,493,493,493
BEGIN DESCRIPTION:
XS7684
END DESCRIPTION:
XS GIS Cut Line= 4
      2444235.90     13620991.12      2444767.19     13621308.85
      2445121.35     13621241.15      2445438.51     13620799.20
#Sta/Elev= 30
  4087.8  268.01  4295.3  262.01  4396.2  260.74  4432.5  260.25  4657.9  260.06
  4816.6  258.53  4877.7  259.02  4887.9  258.55  4918.6  254.06  4959.1  256.99
  4979.5  253.23  4997.8  252.26  4998.1  251.76  5001.9  252.26  5022.8  258.95
  5146.0  264.30  5173.8  265.46  5188.5  267.58  5197.1  269.99  5238.9  269.38
  5304.0  272.11  5318.7  273.63  5328.1  273.14  5360.5  274.01  5389.9  276.36
  5410.8  275.93  5468.9  278.26  5518.1  278.25  5576.6  281.31  5611.4  281.02
#Mann=8,-1,0
  4087.8    0.05       0  4396.2    0.07       0  4432.5    0.12       0
  4657.9    0.07       0  4997.8    0.05       0  5001.9    0.07       0
  5146.0    0.05       0  5328.1   0.035       0
Bank Sta=4997.8,5001.9
Exp/Cntr=0.3,0.1

Type RM Length L Ch R = 1,117,0,0,0
BEGIN DESCRIPTION:
XS7683
END DESCRIPTION:
XS GIS Cut Line= 4
      2444321.68     13621167.29      2444980.73     13621626.56
      2445241.85     13621684.67      2445581.09     13621265.82
#Sta/Elev= 30
  4034.4  264.67  4128.2  263.69  4233.9  260.06  4285.4  258.76  4307.1  257.12
  4330.7  257.44  4372.5  259.25  4494.7  259.48  4548.8  258.06  4677.8  256.66
  4739.0  256.16  4825.4  256.66  4872.8  254.40  4893.3  255.27  4947.6  255.14
  4968.2  252.40  4989.1  250.72  4989.3  250.22  4992.9  250.22  4993.2  250.72
  5006.0  252.41  5026.5  253.66  5034.6  255.15  5076.1  255.51  5164.2  257.01
  5243.5  259.85  5267.2  259.86  5335.3  260.66  5469.6  260.59  5644.2  262.73
#Mann=11,-1,0
  4034.4    0.07       0  4233.9    0.12       0  4285.4    0.07       0
  4548.8    0.12       0  4677.8    0.07       0  4968.2    0.12       0
  4989.1    0.05       0  4993.2    0.12       0  5076.1    0.05       0
  5243.5    0.12       0  5267.2    0.05       0
Bank Sta=4989.1,4993.2
Exp/Cntr=0.3,0.1

Chan Stop Cuts=-1