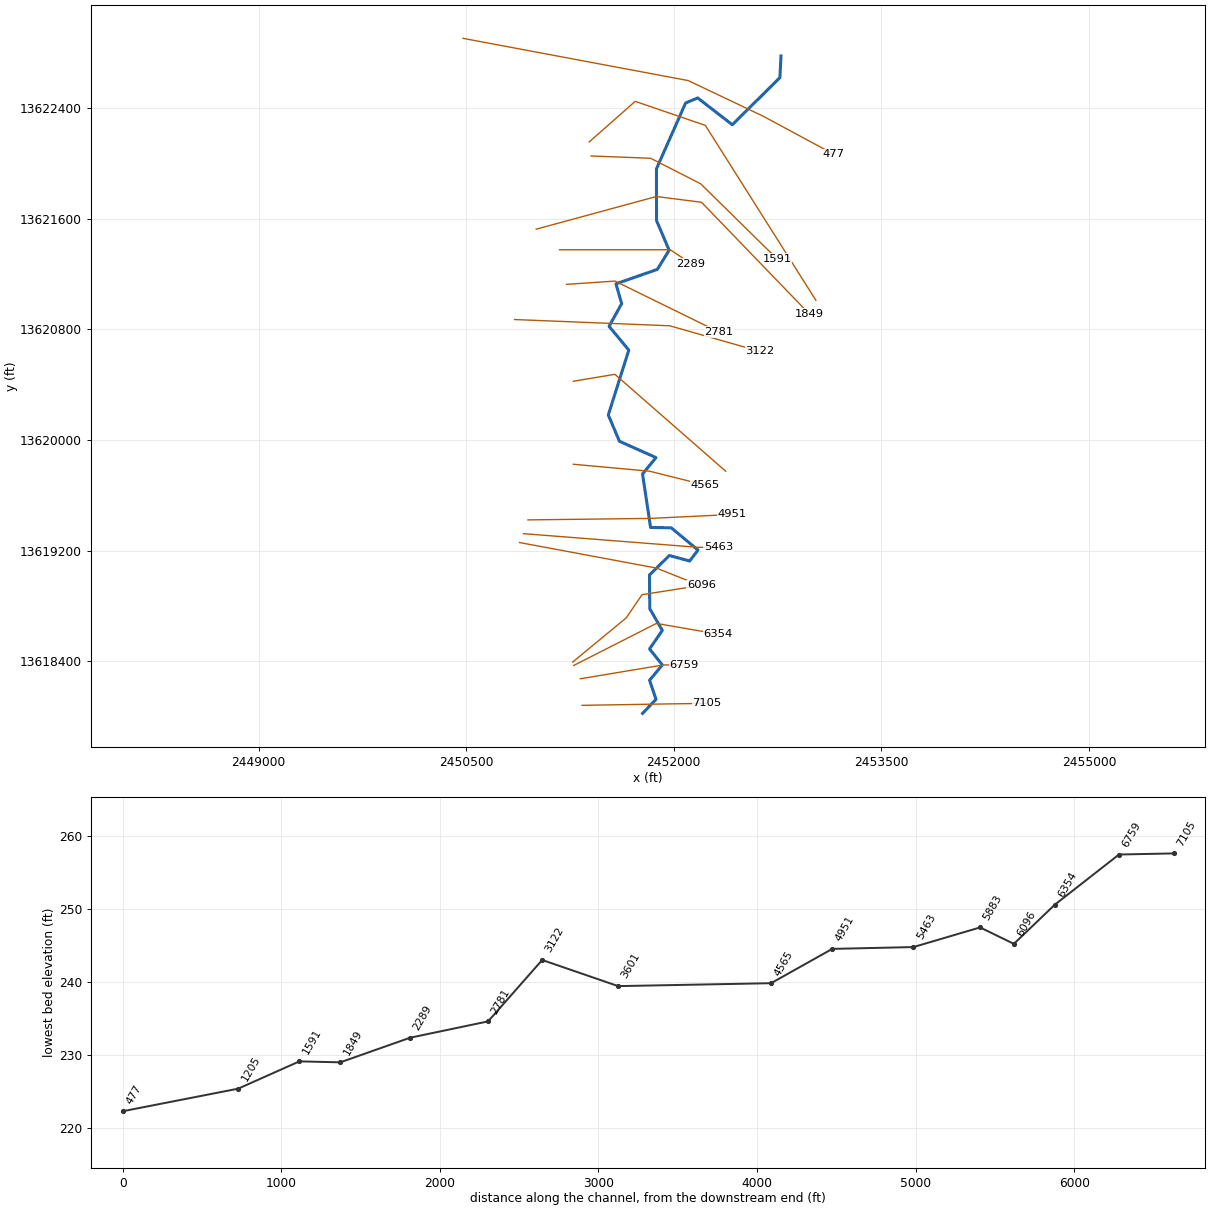
--- Stream0765.prj (project) ---

Proj Title=Stream0765 Base Level Engineering
Current Plan=p01
Default Exp/Contr=0.3,0.1
English Units
Geom File=g01
Flow File=f01
Plan File=p01
BEGIN DESCRIPTION:
Stream0765
END DESCRIPTION:

--- Stream0765.p01 (plan) ---

Plan Title=Multiple Run
Short Identifier=Multiple
Geom File=g01
Flow File=f01
Subcritical Flow
K Sum by GR= 0
Std Step Tol= 0.01
Critical Tol= 0.01
Num of Std Step Trials= 20
Max Error Tol= 0.3
Flow Tol Ratio= 0.001
Split Flow NTrial= 30
Split Flow Tol= 0.02
Split Flow Ratio= 0.02
Log Output Level= 0
Friction Slope Method= 1
Unsteady Friction Slope Method= 2
Unsteady Bridges Friction Slope Method= 1
Parabolic Critical Depth
Global Vel Dist=  1 , 1 , 1
Global Log Level= 0
CheckData=True
Encroach Param= -1, 0, 0, 0
BEGIN DESCRIPTION:
Multiple Run
END DESCRIPTION:

--- Stream0765.f01 (steady flow) ---

Flow Title=Multiple
Number of Profiles=7
Profile Names=10-year,25-year,50-year,1pct_min,100-year,1pct_plu,500-year
River Rch & RM= Stream0765,Reach-1,7105
     608     986    1329     869    1735    3461    2924
River Rch & RM= Stream0765,Reach-1,5883
     809    1327    1803    1186    2366    4722    4038
River Rch & RM= Stream0765,Reach-1,1849
    1241    2074    2854    1898    3786    7554    6606
Boundary for River Rch & Prof#=Stream0765,Reach-1,1
Up Type=0
Dn Type=3
Dn Slope=0.005
Boundary for River Rch & Prof#=Stream0765,Reach-1,2
Up Type=0
Dn Type=3
Dn Slope=0.005
Boundary for River Rch & Prof#=Stream0765,Reach-1,3
Up Type=0
Dn Type=3
Dn Slope=0.005
Boundary for River Rch & Prof#=Stream0765,Reach-1,4
Up Type=0
Dn Type=3
Dn Slope=0.005
Boundary for River Rch & Prof#=Stream0765,Reach-1,5
Up Type=0
Dn Type=3
Dn Slope=0.005
Boundary for River Rch & Prof#=Stream0765,Reach-1,6
Up Type=0
Dn Type=3
Dn Slope=0.005
Boundary for River Rch & Prof#=Stream0765,Reach-1,7
Up Type=0
Dn Type=3
Dn Slope=0.005

--- Stream0765.g01 (geometry) ---

Geom Title=Existing Conditions

River Reach=Stream0765,Reach-1
Reach XY= 30
      2451775.00     13618025.00      2451871.94     13618126.62
      2451825.62     13618264.38      2451917.90     13618375.00
      2451825.20     13618490.35      2451917.77     13618624.71
      2451826.80     13618781.11      2451825.00     13619025.00
      2451968.26     13619165.88      2452114.71     13619125.88
      2452175.55     13619204.88      2451981.99     13619365.92
      2451832.69     13619368.43      2451774.70     13619754.66
      2451871.92     13619873.34      2451607.78     13619991.24
      2451527.17     13620180.97      2451675.42     13620650.00
      2451532.77     13620821.59      2451623.91     13620985.55
      2451582.68     13621128.70      2451881.34     13621233.02
      2451966.96     13621371.68      2451875.77     13621585.69
      2451875.29     13621959.88      2452085.63     13622435.12
      2452173.32     13622471.92      2452423.26     13622278.31
      2452767.21     13622618.80      2452775.00     13622775.00

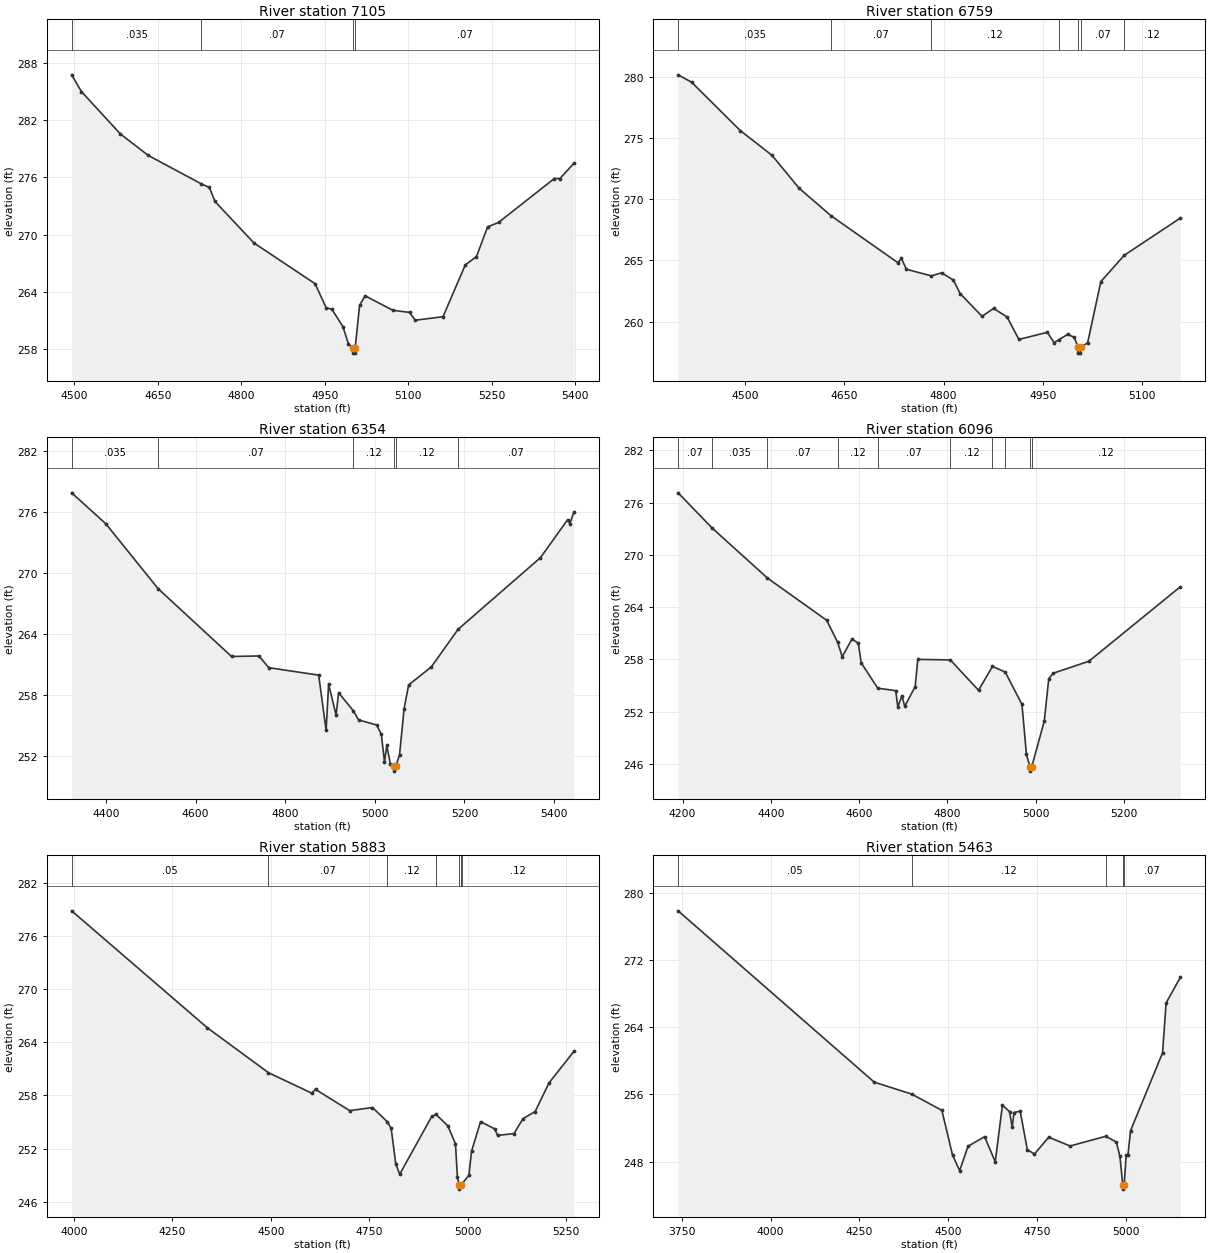
Type RM Length L Ch R = 1,7105,346,346,346
BEGIN DESCRIPTION:
XS7689
END DESCRIPTION:
XS GIS Cut Line= 3
      2451337.44     13618083.09      2451984.30     13618093.75
      2452240.13     13618097.31
#Sta/Elev= 30
  4495.1  286.76  4512.7  285.00  4582.7  280.56  4632.7  278.31  4728.3  275.32
  4742.7  274.95  4752.7  273.48  4822.7  269.13  4932.7  264.85  4952.7  262.32
  4962.7  262.19  4982.7  260.36  4992.7  258.53  5000.7  258.07  5001.0  257.57
  5004.5  257.57  5004.7  258.07  5012.7  262.58  5022.7  263.58  5072.7  262.06
  5102.7  261.84  5112.7  261.02  5162.7  261.39  5202.8  266.83  5222.8  267.69
  5242.8  270.80  5262.8  271.29  5362.8  275.88  5372.8  275.88  5397.9  277.47
#Mann=4,-1,0
  4495.1   0.035       0  4728.3    0.07       0  5000.7    0.05       0
  5004.7    0.07       0
Bank Sta=5000.7,5004.7
Exp/Cntr=0.3,0.1

Type RM Length L Ch R = 1,6759,405,405,405
BEGIN DESCRIPTION:
Stream0765 11.0
END DESCRIPTION:
XS GIS Cut Line= 3
      2451324.99     13618275.00      2451925.00     13618375.00
      2452075.01     13618375.00
#Sta/Elev= 30
  4399.1  280.15  4419.4  279.55  4492.9  275.60  4541.0  273.57  4581.6  270.90
  4630.0  268.64  4731.1  264.80  4736.2  265.16  4743.8  264.27  4781.4  263.73
  4797.0  263.98  4814.8  263.39  4824.9  262.29  4857.9  260.43  4875.6  261.07
  4895.9  260.37  4913.6  258.54  4956.7  259.12  4966.8  258.27  4974.0  258.51
  4987.1  258.95  4997.2  258.72  5002.9  257.92  5003.1  257.42  5006.6  257.42
  5006.9  257.92  5017.4  258.25  5037.4  263.26  5072.7  265.41  5157.4  268.45
#Mann=7,-1,0
  4399.1   0.035       0  4630.0    0.07       0  4781.4    0.12       0
  4974.0    0.07       0  5002.9    0.05       0  5006.9    0.07       0
  5072.7    0.12       0
Bank Sta=5002.9,5006.9
Exp/Cntr=0.3,0.1

Type RM Length L Ch R = 1,6354,258,258,258
BEGIN DESCRIPTION:
Stream0765 10.0
END DESCRIPTION:
XS GIS Cut Line= 3
      2451276.98     13618370.96      2451875.00     13618675.00
      2452318.37     13618598.45
#Sta/Elev= 30
  4323.3  277.85  4399.6  274.81  4516.4  268.44  4680.1  261.79  4741.1  261.84
  4763.3  260.69  4874.6  259.96  4891.2  254.54  4896.8  259.06  4913.5  256.03
  4919.1  258.24  4952.1  256.45  4963.6  255.57  5004.3  255.06  5014.5  254.14
  5021.5  251.44  5026.6  253.06  5034.8  251.22  5042.9  251.04  5043.2  250.54
  5046.9  251.04  5055.1  252.14  5065.2  256.64  5075.4  259.00  5126.1  260.77
  5185.4  264.44  5369.6  271.49  5430.2  275.21  5435.3  274.83  5444.1  275.95
#Mann=6,-1,0
  4323.3   0.035       0  4516.4    0.07       0  4952.1    0.12       0
  5042.9    0.05       0  5046.9    0.12       0  5185.4    0.07       0
Bank Sta=5042.9,5046.9
Exp/Cntr=0.3,0.1

Type RM Length L Ch R = 1,6096,213,213,213
BEGIN DESCRIPTION:
XS7690
END DESCRIPTION:
XS GIS Cut Line= 4
      2451269.88     13618395.83      2451657.31     13618715.73
      2451771.04     13618882.78      2452199.57     13618950.07
#Sta/Elev= 30
  4189.8  277.11  4266.7  273.08  4392.3  267.33  4526.7  262.48  4551.5  259.94
  4561.8  258.31  4584.0  260.35  4598.3  259.84  4604.8  257.61  4642.2  254.70
  4683.0  254.41  4687.7  252.54  4697.2  253.84  4703.4  252.61  4727.1  254.88
  4733.1  258.00  4806.8  257.94  4870.7  254.46  4902.4  257.19  4931.2  256.55
  4969.2  252.84  4979.3  247.10  4987.4  245.68  4987.7  245.18  4991.4  245.68
  5019.8  250.93  5029.9  255.78  5040.0  256.41  5121.0  257.79  5328.1  266.33
#Mann=10,-1,0
  4189.8    0.07       0  4266.7   0.035       0  4392.3    0.07       0
  4551.5    0.12       0  4642.2    0.07       0  4806.8    0.12       0
  4902.4    0.07       0  4931.2    0.12       0  4987.4    0.05       0
  4991.4    0.12       0
Bank Sta=4987.4,4991.4
Exp/Cntr=0.3,0.1

Type RM Length L Ch R = 1,5883,420,420,420
BEGIN DESCRIPTION:
Stream0765 9.0
END DESCRIPTION:
XS GIS Cut Line= 3
      2450886.08     13619259.52      2451875.00     13619075.00
      2452124.96     13618975.02
#Sta/Elev= 30
  3994.1  278.84  4338.9  265.63  4493.9  260.57  4603.4  258.27  4613.5  258.68
  4700.1  256.29  4757.9  256.64  4795.7  255.03  4805.5  254.28  4817.0  250.31
  4827.1  249.11  4908.5  255.63  4919.4  255.86  4949.2  254.58  4968.7  252.56
  4973.7  248.77  4977.7  247.93  4978.0  247.43  4981.7  247.93  4985.9  248.06
  5002.8  248.99  5009.5  251.70  5032.4  255.04  5068.7  254.22  5075.5  253.50
  5117.2  253.69  5140.1  255.38  5171.1  256.19  5206.1  259.41  5269.3  262.97
#Mann=7,-1,0
  3994.1    0.05       0  4493.9    0.07       0  4795.7    0.12       0
  4919.4    0.07       0  4977.7    0.05       0  4981.7    0.07       0
  4985.9    0.12       0
Bank Sta=4977.7,4981.7
Exp/Cntr=0.3,0.1

Type RM Length L Ch R = 1,5463,512,512,512
BEGIN DESCRIPTION:
Stream0765 8.0
END DESCRIPTION:
XS GIS Cut Line= 3
      2450914.49     13619323.50      2452175.00     13619225.00
      2452324.95     13619225.00
#Sta/Elev= 30
  3739.5  277.85  4291.7  257.47  4398.2  256.03  4482.3  254.11  4512.4  248.78
  4532.4  246.95  4556.0  249.84  4602.6  250.98  4632.7  247.99  4652.8  254.72
  4672.8  253.97  4680.4  252.09  4685.4  253.85  4702.9  254.02  4723.0  249.43
  4743.1  248.92  4783.2  250.92  4843.4  249.87  4943.9  251.03  4973.8  250.33
  4983.8  248.63  4991.8  245.24  4992.1  244.74  4995.8  245.24  5001.3  248.78
  5006.3  248.78  5013.8  251.71  5103.8  260.95  5113.8  266.89  5153.8  269.93
#Mann=5,-1,0
  3739.5    0.05       0  4398.2    0.12       0  4943.9    0.07       0
  4991.8    0.05       0  4995.8    0.07       0
Bank Sta=4991.8,4995.8
Exp/Cntr=0.3,0.1

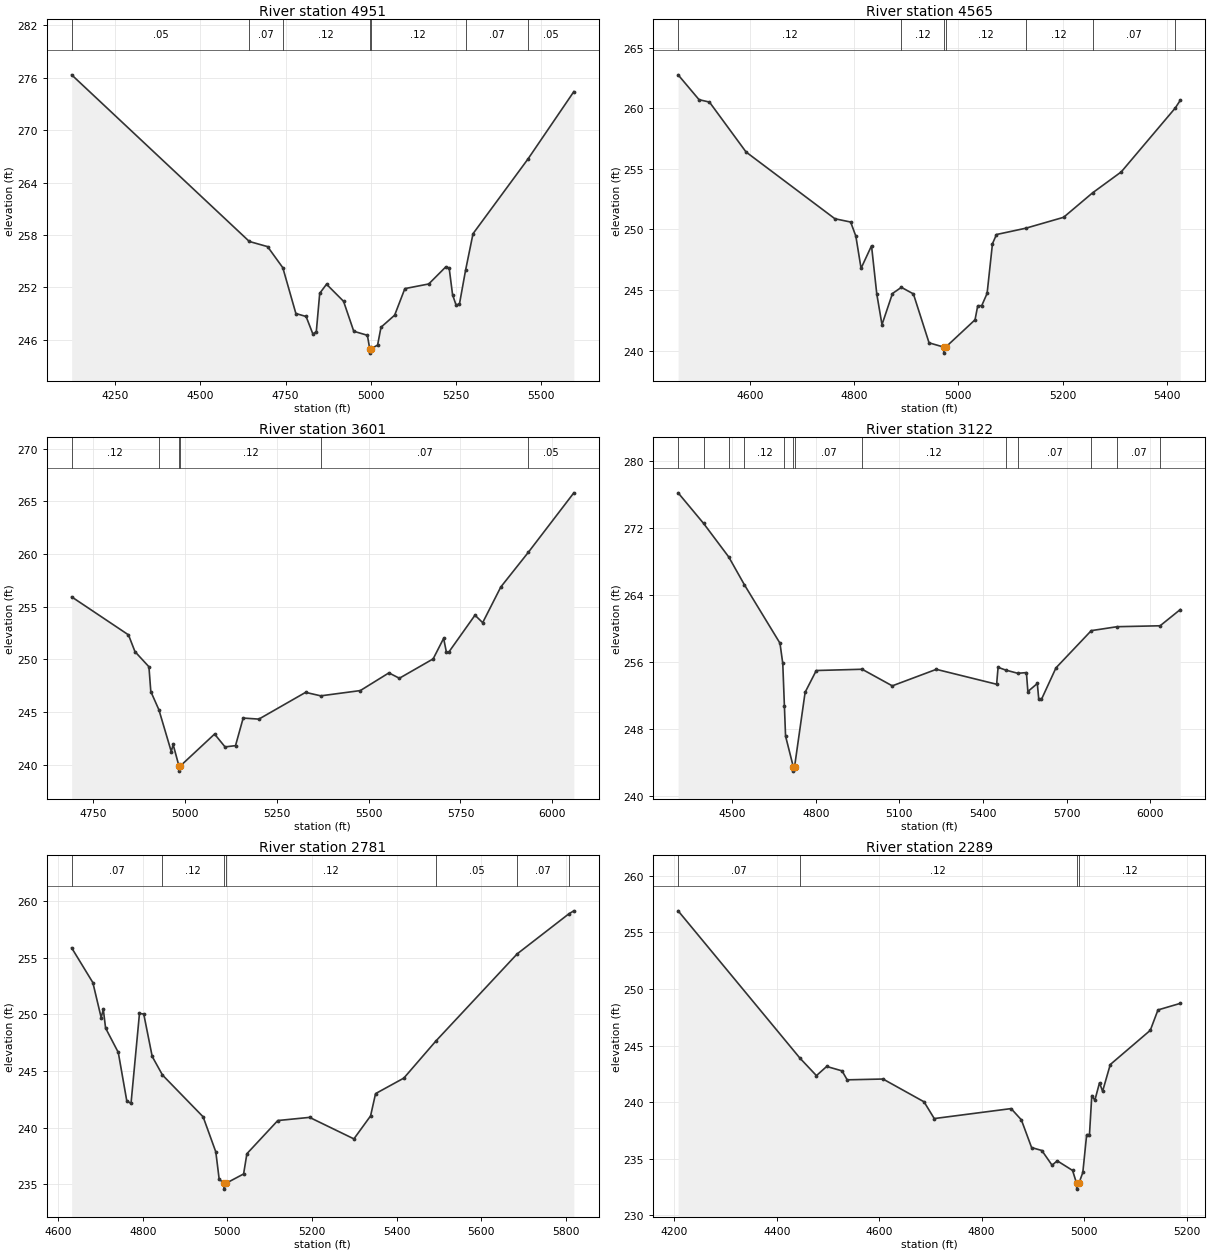
Type RM Length L Ch R = 1,4951,386,386,386
BEGIN DESCRIPTION:
Stream0765 7.0
END DESCRIPTION:
XS GIS Cut Line= 3
      2450946.49     13619423.02      2451827.91     13619433.68
      2452420.75     13619462.08
#Sta/Elev= 30
  4121.8  276.32  4643.7  257.26  4697.3  256.67  4742.0  254.26  4780.4  249.02
  4810.4  248.68  4830.4  246.67  4840.4  246.95  4850.4  251.33  4870.4  252.37
  4920.4  250.42  4950.4  246.99  4990.4  246.53  4997.3  244.99  4997.6  244.49
  5001.3  244.99  5020.4  245.41  5030.4  247.45  5070.5  248.83  5100.5  251.87
  5170.6  252.40  5220.6  254.35  5230.6  254.23  5240.6  251.17  5250.7  250.01
  5260.7  250.08  5278.7  253.95  5300.7  258.15  5462.2  266.70  5596.8  274.40
#Mann=7,-1,0
  4121.8    0.05       0  4643.7    0.07       0  4742.0    0.12       0
  4997.3    0.05       0  5001.3    0.12       0  5278.7    0.07       0
  5462.2    0.05       0
Bank Sta=4997.3,5001.3
Exp/Cntr=0.3,0.1

Type RM Length L Ch R = 1,4565,964,964,964
BEGIN DESCRIPTION:
Stream0765 6.0
END DESCRIPTION:
XS GIS Cut Line= 3
      2451275.00     13619825.00      2451825.00     13619775.00
      2452225.03     13619674.99
#Sta/Elev= 30
  4461.6  262.76  4501.8  260.71  4521.8  260.51  4592.1  256.39  4762.8  250.88
  4793.0  250.61  4803.0  249.44  4813.0  246.79  4833.1  248.65  4843.2  244.67
  4853.2  242.14  4873.3  244.71  4890.4  245.22  4913.5  244.68  4943.6  240.64
  4971.7  240.29  4971.9  239.79  4975.7  240.29  5031.9  242.54  5037.1  243.70
  5044.8  243.71  5055.1  244.72  5065.4  248.82  5073.1  249.58  5129.4  250.10
  5202.0  251.00  5257.7  253.02  5312.8  254.75  5416.3  260.01  5426.2  260.66
#Mann=7,-1,0
  4461.6    0.12       0  4890.4    0.12       0  4971.7    0.05       0
  4975.7    0.12       0  5129.4    0.12       0  5257.7    0.07       0
  5416.3    0.05       0
Bank Sta=4971.7,4975.7
Exp/Cntr=0.3,0.1

Type RM Length L Ch R = 1,3601,479,479,479
BEGIN DESCRIPTION:
Stream0765 5.0
END DESCRIPTION:
XS GIS Cut Line= 3
      2451274.95     13620424.99      2451575.00     13620475.00
      2452375.00     13619775.00
#Sta/Elev= 30
  4691.4  255.94  4846.1  252.33  4863.8  250.74  4901.8  249.30  4906.9  246.95
  4928.9  245.22  4962.6  241.25  4967.7  241.92  4983.4  239.89  4983.7  239.39
  4987.6  239.89  5080.5  242.91  5109.0  241.69  5137.5  241.81  5158.4  244.43
  5201.1  244.33  5328.3  246.87  5369.6  246.54  5477.3  247.04  5555.1  248.72
  5583.6  248.21  5675.6  250.05  5704.1  252.00  5711.7  250.68  5718.3  250.70
  5789.5  254.20  5810.4  253.49  5859.8  256.88  5934.9  260.18  6058.6  265.82
#Mann=6,-1,0
  4691.4    0.12       0  4928.9    0.12       0  4983.4    0.05       0
  4987.6    0.12       0  5369.6    0.07       0  5934.9    0.05       0
Bank Sta=4983.4,4987.6
Exp/Cntr=0.3,0.1

Type RM Length L Ch R = 1,3122,341,341,341
BEGIN DESCRIPTION:
Stream0765 4.0
END DESCRIPTION:
XS GIS Cut Line= 3
      2450850.08     13620870.73      2451970.65     13620825.69
      2452623.67     13620639.91
#Sta/Elev= 30
  4306.7  276.19  4398.0  272.54  4488.3  268.53  4544.4  265.21  4671.9  258.24
  4681.9  255.82  4687.7  250.79  4691.9  247.15  4719.8  243.47  4720.1  242.97
  4724.1  243.47  4762.0  252.38  4802.0  254.98  4966.4  255.13  5074.5  253.15
  5232.4  255.12  5448.6  253.34  5453.8  255.36  5481.4  255.03  5524.3  254.65
  5555.4  254.73  5560.6  252.47  5594.5  253.43  5599.7  251.53  5609.4  251.54
  5661.4  255.30  5787.9  259.74  5880.7  260.21  6034.7  260.32  6107.1  262.26
#Mann=13,-1,0
  4306.7    0.05       0  4398.0    0.07       0  4488.3    0.05       0
  4544.4    0.12       0  4687.7    0.07       0  4719.8    0.05       0
  4724.1    0.07       0  4966.4    0.12       0  5481.4    0.05       0
  5524.3    0.07       0  5787.9    0.05       0  5880.7    0.07       0
  6034.7    0.05       0
Bank Sta=4719.8,4724.1
Exp/Cntr=0.3,0.1

Type RM Length L Ch R = 1,2781,492,492,492
BEGIN DESCRIPTION:
Stream0765 3.0
END DESCRIPTION:
XS GIS Cut Line= 3
      2451225.02     13621125.00      2451575.69     13621148.61
      2452325.69     13620780.56
#Sta/Elev= 30
  4632.1  255.88  4682.2  252.81  4701.9  249.71  4706.9  250.45  4712.3  248.79
  4742.3  246.64  4762.4  242.36  4772.4  242.13  4792.4  250.08  4802.5  250.03
  4822.5  246.28  4846.8  244.64  4942.8  240.95  4972.8  237.85  4980.7  235.46
  4991.8  235.06  4992.1  234.56  4996.1  235.06  5038.5  235.90  5046.3  237.69
  5119.3  240.62  5194.4  240.90  5299.2  239.00  5338.6  241.03  5350.4  243.00
  5417.2  244.37  5492.8  247.64  5685.2  255.35  5807.1  258.88  5819.0  259.15
#Mann=7,-1,0
  4632.1    0.07       0  4846.8    0.12       0  4991.8    0.05       0
  4996.1    0.12       0  5492.8    0.05       0  5685.2    0.07       0
  5807.1    0.05       0
Bank Sta=4991.8,4996.1
Exp/Cntr=0.3,0.1

Type RM Length L Ch R = 1,2289,440,440,440
BEGIN DESCRIPTION:
Stream0765 2.0
END DESCRIPTION:
XS GIS Cut Line= 3
      2451174.97     13621375.00      2451975.00     13621375.00
      2452124.99     13621275.00
#Sta/Elev= 30
  4207.5  256.89  4445.2  243.89  4477.5  242.34  4497.5  243.15  4527.5  242.76
  4537.5  241.97  4607.5  242.04  4687.5  240.03  4707.5  238.55  4857.5  239.43
  4877.5  238.44  4897.5  235.99  4917.5  235.73  4937.5  234.43  4947.5  234.82
  4977.5  233.97  4985.4  232.82  4985.6  232.32  4989.7  232.82  4997.5  233.79
  5005.0  237.13  5010.5  237.13  5015.0  240.58  5021.0  240.17  5030.1  241.71
  5036.1  240.96  5051.1  243.32  5129.2  246.34  5144.2  248.14  5187.8  248.72
#Mann=4,-1,0
  4207.5    0.07       0  4445.2    0.12       0  4985.4    0.05       0
  4989.7    0.12       0
Bank Sta=4985.4,4989.7
Exp/Cntr=0.3,0.1

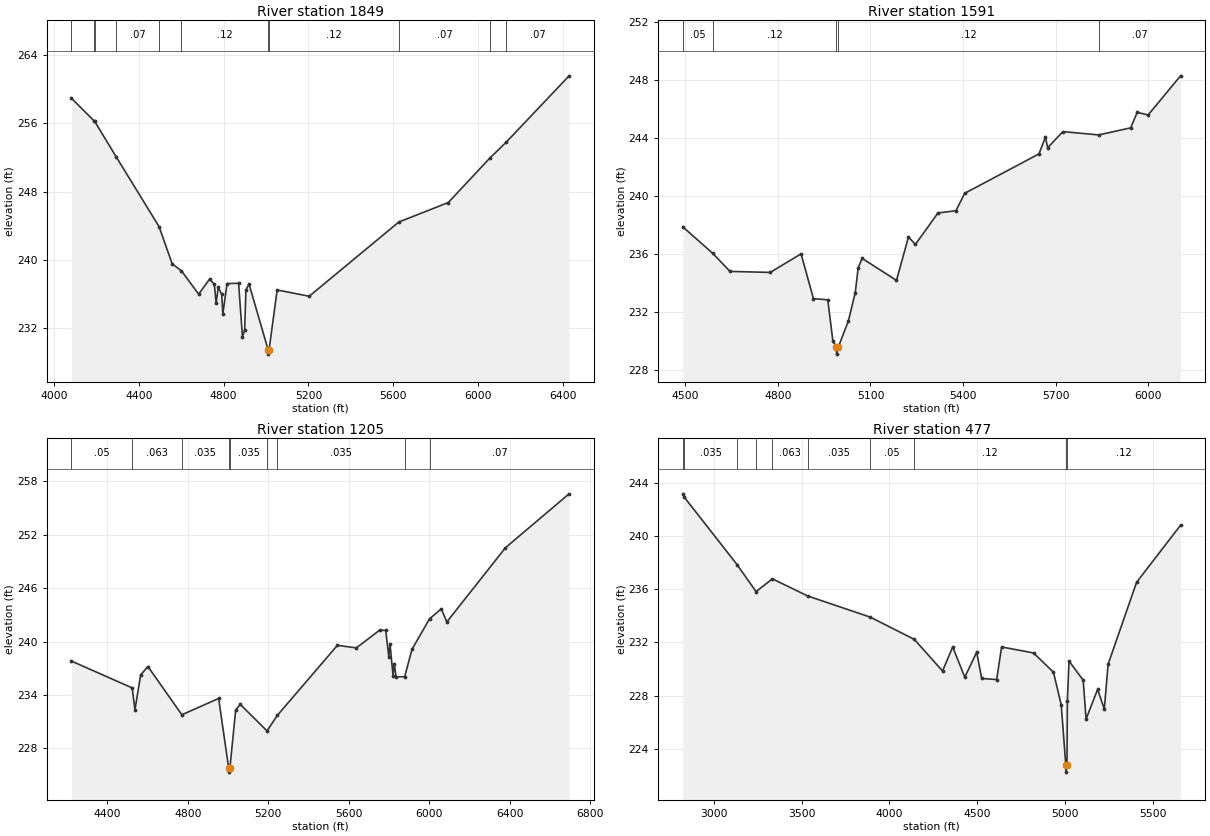
Type RM Length L Ch R = 1,1849,258,258,258
BEGIN DESCRIPTION:
XS7687
END DESCRIPTION:
XS GIS Cut Line= 4
      2451006.28     13621523.62      2451874.31     13621759.72
      2452200.69     13621718.06      2452978.50     13620912.47
#Sta/Elev= 30
  4081.5  258.94  4190.0  256.24  4191.6  256.21  4292.7  252.07  4495.1  243.89
  4556.9  239.53  4600.7  238.71  4681.9  235.98  4733.1  237.73  4756.2  237.13
  4764.2  234.91  4774.5  236.78  4790.8  235.96  4796.0  233.67  4816.0  237.22
  4870.4  237.25  4888.5  231.00  4898.9  231.74  4905.0  236.48  4919.6  237.16
  5009.8  229.45  5010.1  228.95  5014.2  229.45  5052.3  236.47  5203.6  235.73
  5626.5  244.43  5859.8  246.71  6055.9  251.92  6131.9  253.75  6429.9  261.56
#Mann=11,-1,0
  4081.5    0.05       0  4190.0    0.07       0  4191.6    0.05       0
  4292.7    0.07       0  4495.1    0.05       0  4600.7    0.12       0
  5009.8    0.05       0  5014.2    0.12       0  5626.5    0.07       0
  6055.9    0.05       0  6131.9    0.07       0
Bank Sta=5009.8,5014.2
Exp/Cntr=0.3,0.1

Type RM Length L Ch R = 1,1591,386,386,386
BEGIN DESCRIPTION:
E21335
END DESCRIPTION:
XS GIS Cut Line= 4
      2451402.65     13622052.57      2451832.61     13622036.16
      2452193.63     13621852.37      2452747.03     13621308.80
#Sta/Elev= 30
  4492.7  237.86  4589.8  236.03  4645.2  234.79  4775.3  234.72  4875.3  236.00
  4915.4  232.91  4961.8  232.83  4978.4  229.97  4989.8  229.58  4990.3  229.08
  4996.2  229.58  5028.5  231.37  5050.7  233.32  5060.3  235.04  5073.0  235.69
  5184.2  234.17  5223.1  237.17  5245.3  236.65  5318.4  238.82  5376.7  238.98
  5405.0  240.18  5645.4  242.90  5666.6  244.06  5673.7  243.33  5723.1  244.44
  5839.0  244.21  5942.4  244.70  5963.6  245.77  5999.0  245.59  6103.8  248.29
#Mann=5,-1,0
  4492.7    0.05       0  4589.8    0.12       0  4989.8    0.05       0
  4996.2    0.12       0  5839.0    0.07       0
Bank Sta=4989.8,4996.2
Exp/Cntr=0.3,0.1

Type RM Length L Ch R = 1,1205,728,728,728
BEGIN DESCRIPTION:
Stream0765 1.0
END DESCRIPTION:
XS GIS Cut Line= 4
      2451389.58     13622154.34      2451721.53     13622447.22
      2452228.47     13622273.61      2453026.98     13621009.88
#Sta/Elev= 30
  4221.7  237.81  4523.6  234.80  4537.4  232.35  4565.9  236.26  4601.9  237.20
  4770.6  231.78  4953.4  233.61  5003.0  225.84  5003.5  225.34  5009.5  225.84
  5038.0  232.31  5060.7  232.95  5193.9  229.97  5244.9  231.71  5543.8  239.58
  5637.9  239.29  5754.6  241.30  5783.8  241.25  5799.1  238.30  5805.0  239.76
  5820.2  236.17  5826.2  237.52  5835.5  236.05  5878.0  236.05  5914.4  239.13
  6002.1  242.57  6060.2  243.68  6087.3  242.20  6379.0  250.54  6695.1  256.59
#Mann=9,-1,0
  4221.7    0.05       0  4523.6   0.063       0  4770.6   0.035       0
  5003.0   0.035       0  5009.5   0.035       0  5193.9     0.1       0
  5244.9   0.035       0  5878.0   0.063       0  6002.1    0.07       0
Bank Sta=5003,5009.5
Exp/Cntr=0.3,0.1

Type RM Length L Ch R = 1,477,0,0,0
BEGIN DESCRIPTION:
E21334
END DESCRIPTION:
XS GIS Cut Line= 4
      2450477.20     13622902.60      2452105.02     13622597.38
      2452649.83     13622338.11      2453155.25     13622065.70
#Sta/Elev= 30
  2823.8  243.17  2830.4  242.94  3132.3  237.85  3240.4  235.82  3333.5  236.78
  3534.8  235.49  3891.0  233.90  4141.5  232.23  4302.5  229.85  4360.1  231.66
  4429.1  229.39  4496.9  231.27  4525.1  229.29  4610.4  229.21  4638.7  231.66
  4820.3  231.21  4933.9  229.76  4978.3  227.30  5004.3  222.75  5004.8  222.25
  5010.9  222.75  5013.1  227.59  5022.6  230.60  5103.3  229.16  5119.6  226.24
  5185.3  228.47  5223.4  227.00  5245.3  230.37  5407.3  236.52  5657.5  240.81
#Mann=10,-1,0
  2823.8    0.05       0  2830.4   0.035       0  3132.3   0.063       0
  3240.4   0.035       0  3333.5   0.063       0  3534.8   0.035       0
  3891.0    0.05       0  4141.5    0.12       0  5004.3    0.05       0
  5010.9    0.12       0
Bank Sta=5004.3,5010.9
Exp/Cntr=0.3,0.1

Chan Stop Cuts=-1