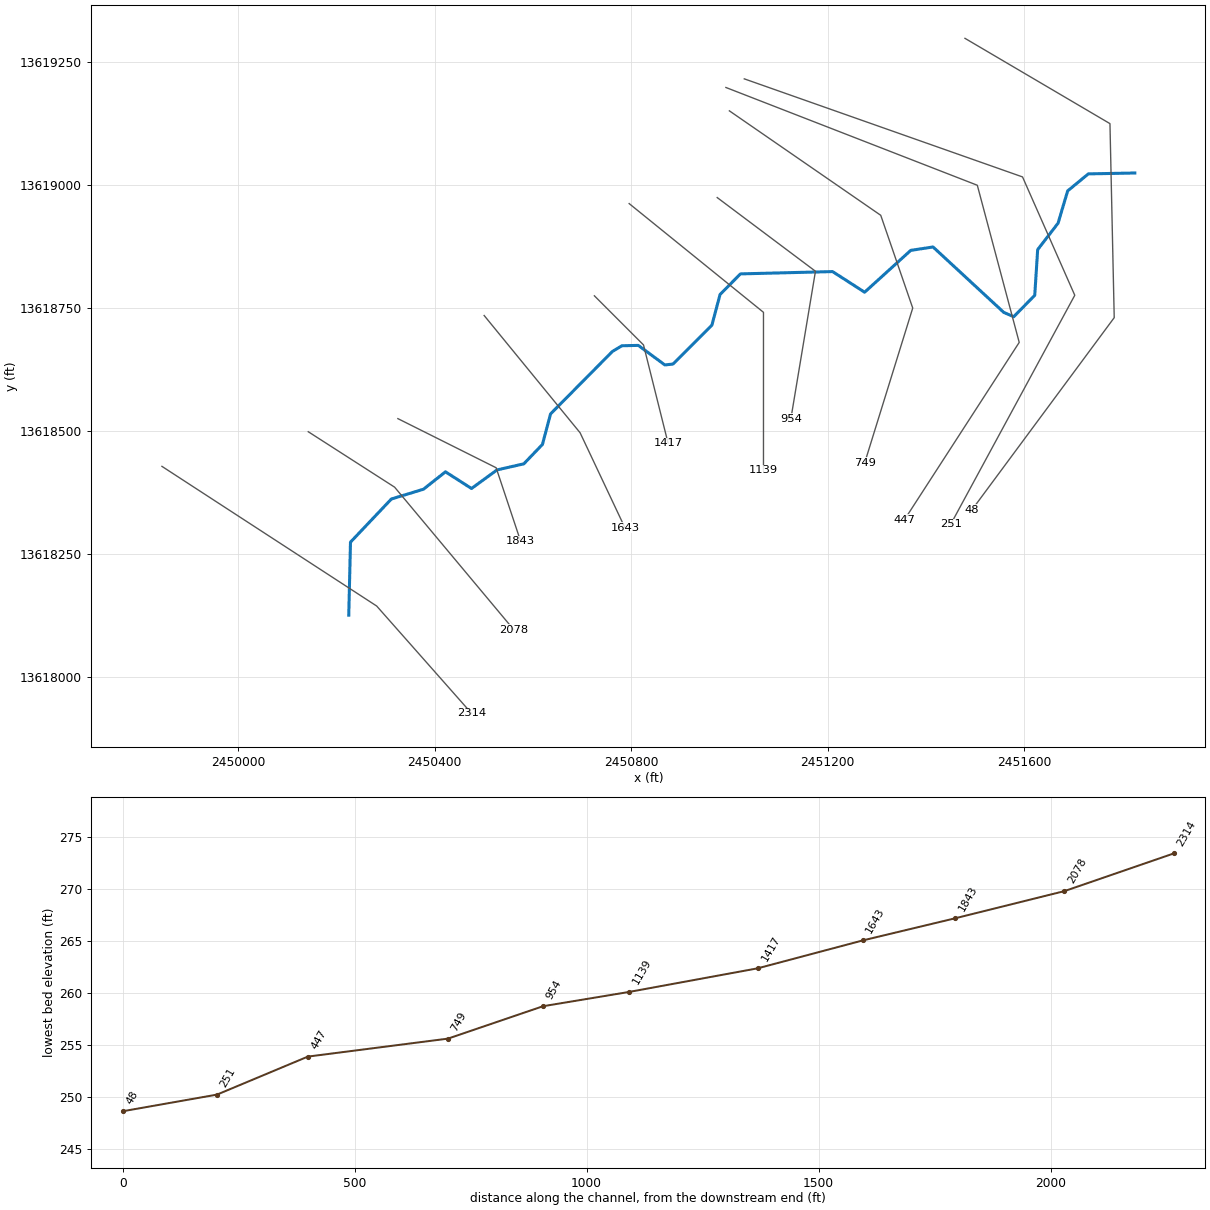
--- Stream0766.prj (project) ---

Proj Title=Stream0766 Base Level Engineering
Current Plan=p01
Default Exp/Contr=0.3,0.1
English Units
Geom File=g01
Flow File=f01
Plan File=p01
BEGIN DESCRIPTION:
Stream0766
END DESCRIPTION:

--- Stream0766.p01 (plan) ---

Plan Title=Multiple Run
Short Identifier=Multiple
Geom File=g01
Flow File=f01
Subcritical Flow
K Sum by GR= 0
Std Step Tol= 0.01
Critical Tol= 0.01
Num of Std Step Trials= 20
Max Error Tol= 0.3
Flow Tol Ratio= 0.001
Split Flow NTrial= 30
Split Flow Tol= 0.02
Split Flow Ratio= 0.02
Log Output Level= 0
Friction Slope Method= 1
Unsteady Friction Slope Method= 2
Unsteady Bridges Friction Slope Method= 1
Parabolic Critical Depth
Global Vel Dist=  1 , 1 , 1
Global Log Level= 0
CheckData=True
Encroach Param= -1, 0, 0, 0
BEGIN DESCRIPTION:
Multiple Run
END DESCRIPTION:

--- Stream0766.f01 (steady flow) ---

Flow Title=Multiple
Number of Profiles=7
Profile Names=10-year,25-year,50-year,1pct_min,100-year,1pct_plu,500-year
River Rch & RM= Stream0766,Reach-1,2314
     276     425     553     351     700    1397    1106
River Rch & RM= Stream0766,Reach-1,48
     809    1327    1803    1186    2366    4722    4038
Boundary for River Rch & Prof#=Stream0766,Reach-1,1
Up Type=0
Dn Type=3
Dn Slope=0.005
Boundary for River Rch & Prof#=Stream0766,Reach-1,2
Up Type=0
Dn Type=3
Dn Slope=0.005
Boundary for River Rch & Prof#=Stream0766,Reach-1,3
Up Type=0
Dn Type=3
Dn Slope=0.005
Boundary for River Rch & Prof#=Stream0766,Reach-1,4
Up Type=0
Dn Type=3
Dn Slope=0.005
Boundary for River Rch & Prof#=Stream0766,Reach-1,5
Up Type=0
Dn Type=3
Dn Slope=0.005
Boundary for River Rch & Prof#=Stream0766,Reach-1,6
Up Type=0
Dn Type=3
Dn Slope=0.005
Boundary for River Rch & Prof#=Stream0766,Reach-1,7
Up Type=0
Dn Type=3
Dn Slope=0.005

--- Stream0766.g01 (geometry) ---

Geom Title=Existing Conditions

River Reach=Stream0766,Reach-1
Reach XY= 30
      2450225.00     13618125.00      2450228.49     13618273.56
      2450311.76     13618361.41      2450377.29     13618381.40
      2450421.77     13618416.76      2450474.92     13618382.76
      2450526.68     13618420.55      2450581.33     13618433.00
      2450619.25     13618472.46      2450635.79     13618534.66
      2450761.79     13618661.86      2450781.05     13618673.34
      2450814.36     13618674.11      2450868.46     13618634.33
      2450885.08     13618636.11      2450964.21     13618715.29
      2450980.74     13618777.57      2451022.30     13618819.64
      2451209.84     13618824.34      2451275.10     13618782.33
      2451368.95     13618867.50      2451414.36     13618874.45
      2451558.43     13618741.15      2451578.62     13618732.47
      2451621.39     13618776.01      2451627.33     13618869.03
      2451668.85     13618922.85      2451688.42     13618988.63
      2451730.55     13619023.23      2451825.00     13619025.00

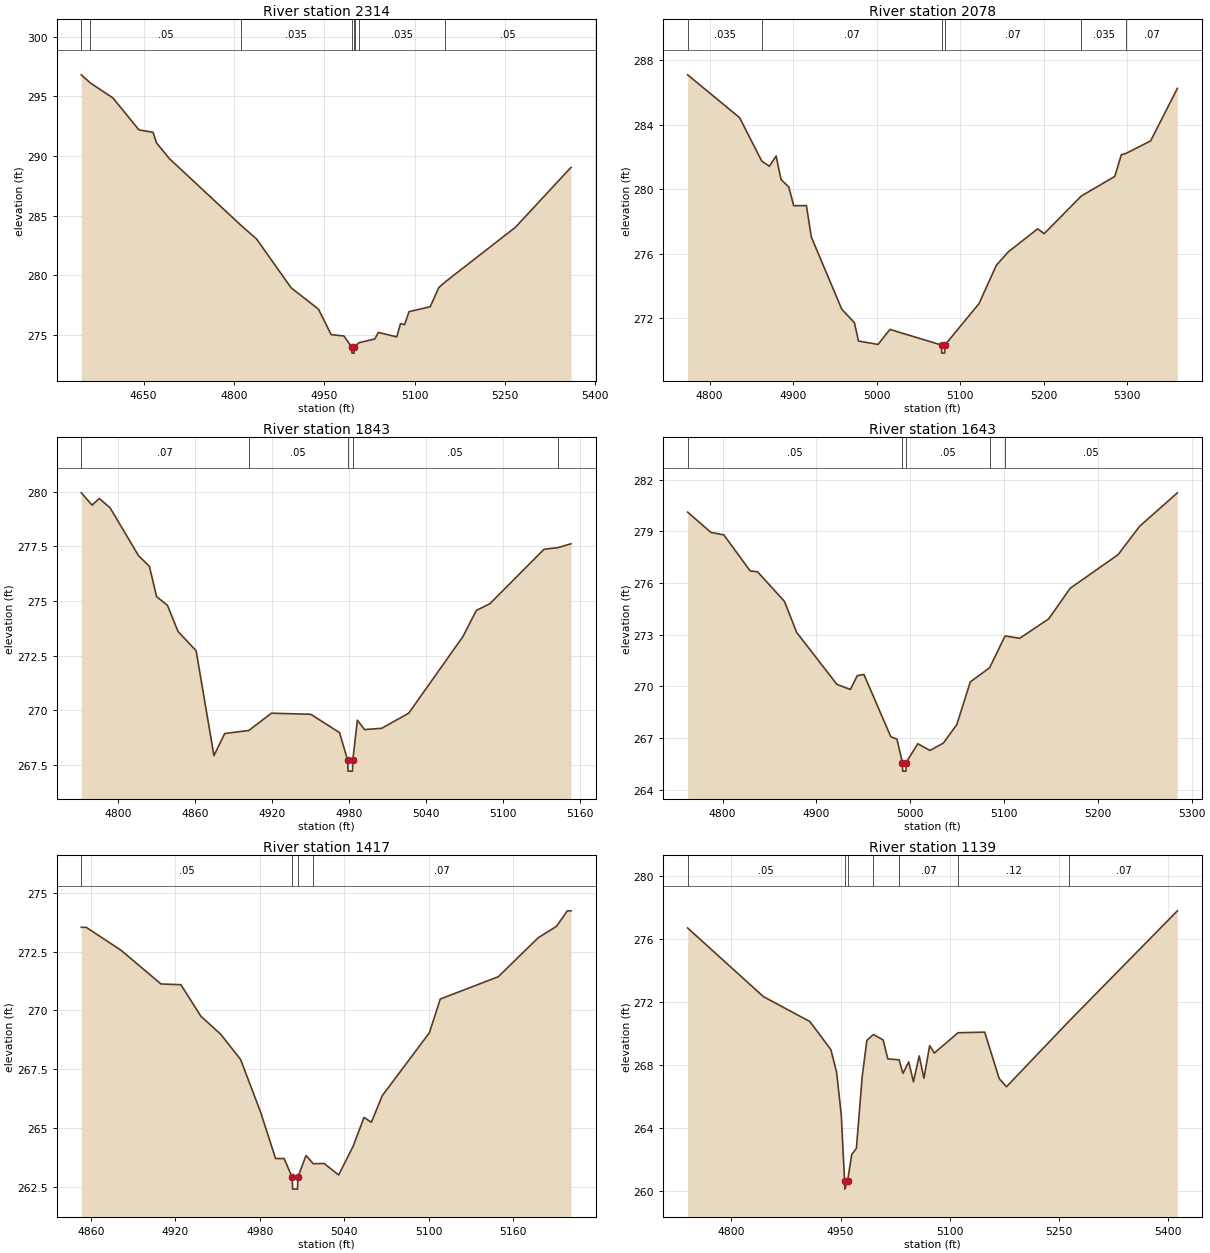
Type RM Length L Ch R = 1,2314,236,236,236
BEGIN DESCRIPTION:
Stream0766 4.0
END DESCRIPTION:
XS GIS Cut Line= 3
      2449844.69     13618427.84      2450281.85     13618143.51
      2450474.98     13617925.02
#Sta/Elev= 30
  4546.5  296.80  4561.6  296.12  4599.1  294.86  4642.3  292.18  4665.6  291.98
  4671.5  291.09  4692.6  289.78  4811.4  284.19  4837.6  283.03  4894.9  278.94
  4940.3  277.15  4961.4  275.01  4982.5  274.90  4995.6  273.96  4995.9  273.46
  4999.4  273.46  4999.6  273.96  5000.2  274.00  5007.3  274.33  5033.9  274.65
  5039.8  275.20  5070.3  274.82  5076.5  275.94  5083.2  275.84  5090.7  276.94
  5125.8  277.35  5140.1  278.96  5151.2  279.45  5267.2  284.01  5359.6  289.04
#Mann=8,-1,0
  4546.5    0.07       0  4561.6    0.05       0  4811.4   0.035       0
  4995.6   0.035       0  4999.6   0.035       0  5000.2    0.07       0
  5007.3   0.035       0  5151.2    0.05       0
Bank Sta=4995.6,4999.6
Exp/Cntr=0.3,0.1

Type RM Length L Ch R = 1,2078,235,235,235
BEGIN DESCRIPTION:
E21341
END DESCRIPTION:
XS GIS Cut Line= 3
      2450142.55     13618498.35      2450318.33     13618385.50
      2450560.69     13618095.53
#Sta/Elev= 30
  4773.6  287.09  4835.9  284.43  4862.4  281.74  4871.6  281.42  4879.6  282.06
  4885.5  280.60  4894.8  280.13  4900.7  278.97  4915.9  278.98  4921.8  277.03
  4958.2  272.56  4973.4  271.72  4978.3  270.58  5001.7  270.37  5016.0  271.30
  5077.8  270.33  5078.0  269.83  5081.5  269.83  5081.8  270.33  5122.7  272.90
  5143.5  275.28  5157.8  276.11  5193.0  277.54  5200.8  277.24  5245.2  279.57
  5285.4  280.79  5293.2  282.13  5298.9  282.22  5328.3  282.99  5360.4  286.25
#Mann=6,-1,0
  4773.6   0.035       0  4862.4    0.07       0  5077.8    0.05       0
  5081.8    0.07       0  5245.2   0.035       0  5298.9    0.07       0
Bank Sta=5077.8,5081.8
Exp/Cntr=0.3,0.1

Type RM Length L Ch R = 1,1843,200,200,200
BEGIN DESCRIPTION:
Stream0766 3.0
END DESCRIPTION:
XS GIS Cut Line= 3
      2450324.99     13618525.01      2450525.00     13618425.00
      2450574.99     13618275.03
#Sta/Elev= 30
  4771.6  279.95  4780.0  279.39  4785.6  279.69  4794.0  279.27  4816.3  277.07
  4824.7  276.59  4830.3  275.20  4838.7  274.81  4847.1  273.60  4861.1  272.73
  4875.0  267.93  4883.4  268.94  4902.2  269.08  4919.8  269.87  4950.5  269.82
  4972.9  268.98  4979.2  267.72  4979.5  267.22  4983.0  267.22  4983.2  267.72
  4986.8  269.55  4992.4  269.12  5005.8  269.18  5026.8  269.87  5069.0  273.37
  5079.5  274.57  5090.1  274.88  5132.3  277.37  5142.9  277.44  5153.3  277.62
#Mann=5,-1,0
  4771.6    0.07       0  4902.2    0.05       0  4979.2    0.05       0
  4983.2    0.05       0  5142.9   0.035       0
Bank Sta=4979.2,4983.2
Exp/Cntr=0.3,0.1

Type RM Length L Ch R = 1,1643,226,226,226
BEGIN DESCRIPTION:
E21340
END DESCRIPTION:
XS GIS Cut Line= 3
      2450500.61     13618734.90      2450695.93     13618496.18
      2450787.07     13618303.05
#Sta/Elev= 30
  4762.8  280.11  4787.7  278.93  4801.4  278.79  4829.4  276.70  4837.3  276.65
  4866.0  274.93  4879.0  273.13  4922.0  270.11  4936.3  269.82  4943.6  270.62
  4950.7  270.69  4979.4  267.07  4985.9  266.94  4991.7  265.58  4992.0  265.08
  4995.5  265.08  4995.7  265.58  5008.1  266.67  5021.1  266.28  5035.4  266.71
  5049.7  267.78  5064.1  270.26  5084.7  271.08  5101.1  272.92  5116.8  272.79
  5147.7  273.92  5170.5  275.69  5221.6  277.64  5244.4  279.28  5284.8  281.23
#Mann=5,-1,0
  4762.8    0.05       0  4991.7    0.05       0  4995.7    0.05       0
  5084.7    0.07       0  5101.1    0.05       0
Bank Sta=4991.7,4995.7
Exp/Cntr=0.3,0.1

Type RM Length L Ch R = 1,1417,278,278,278
BEGIN DESCRIPTION:
Stream0766 2.0
END DESCRIPTION:
XS GIS Cut Line= 3
      2450724.99     13618775.01      2450825.00     13618675.00
      2450875.00     13618474.99
#Sta/Elev= 30
  4853.3  273.53  4856.8  273.53  4881.6  272.55  4909.9  271.12  4924.0  271.09
  4938.2  269.75  4952.3  268.98  4966.4  267.91  4980.6  265.67  4991.2  263.70
  4997.3  263.70  5003.0  262.90  5003.3  262.40  5006.8  262.40  5007.0  262.90
  5012.8  263.83  5018.0  263.48  5025.7  263.49  5036.0  263.00  5046.3  264.23
  5054.0  265.45  5059.2  265.24  5066.9  266.37  5100.4  269.05  5108.1  270.48
  5149.3  271.43  5177.7  273.09  5190.6  273.57  5198.3  274.23  5200.9  274.23
#Mann=4,-1,0
  4853.3    0.05       0  5003.0    0.05       0  5007.0    0.05       0
  5018.0    0.07       0
Bank Sta=5003,5007
Exp/Cntr=0.3,0.1

Type RM Length L Ch R = 1,1139,185,185,185
BEGIN DESCRIPTION:
E21339
END DESCRIPTION:
XS GIS Cut Line= 3
      2450795.77     13618962.75      2451069.19     13618741.41
      2451069.19     13618420.19
#Sta/Elev= 30
  4739.9  276.72  4843.9  272.36  4907.9  270.77  4936.7  268.99  4944.6  267.55
  4951.0  264.84  4955.6  260.62  4955.9  260.12  4959.6  260.62  4965.4  262.33
  4971.8  262.71  4979.8  267.28  4986.2  269.58  4995.3  269.95  5008.6  269.60
  5015.0  268.40  5030.4  268.34  5035.8  267.48  5043.7  268.21  5050.2  266.94
  5058.1  268.59  5064.6  267.17  5072.5  269.24  5078.9  268.77  5111.5  270.06
  5148.1  270.10  5168.1  267.14  5178.1  266.63  5264.5  270.82  5412.9  277.81
#Mann=7,-1,0
  4739.9    0.05       0  4955.6    0.05       0  4959.6    0.05       0
  4995.3    0.12       0  5030.4    0.07       0  5111.5    0.12       0
  5264.5    0.07       0
Bank Sta=4955.6,4959.6
Exp/Cntr=0.3,0.1

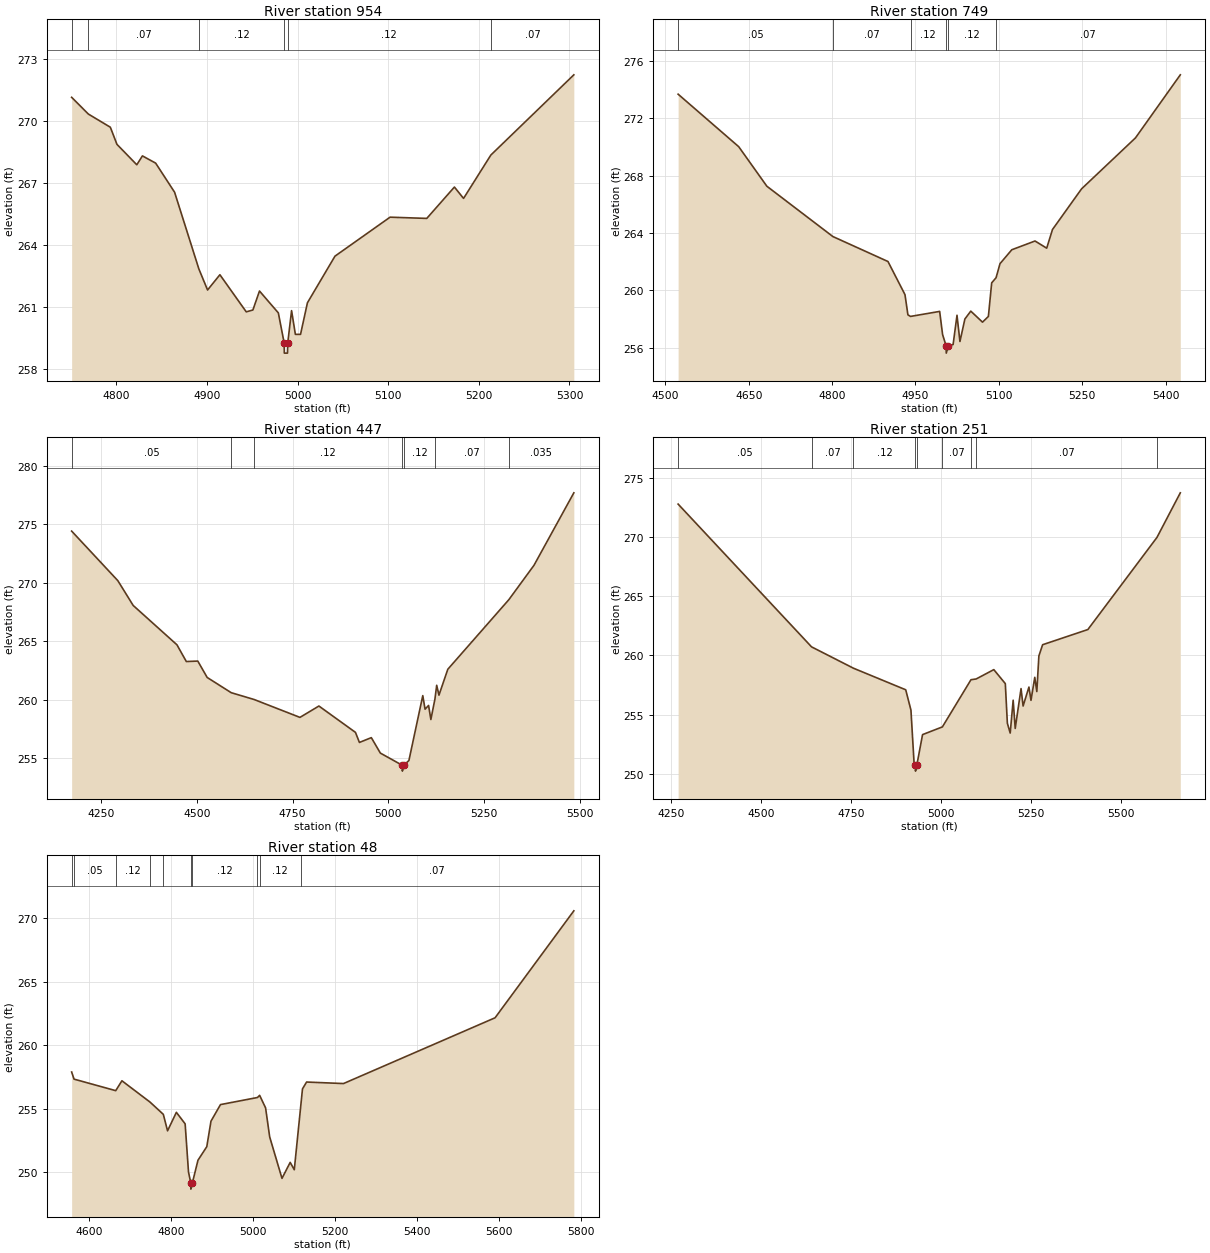
Type RM Length L Ch R = 1,954,205,205,205
BEGIN DESCRIPTION:
Stream0766 1.0
END DESCRIPTION:
XS GIS Cut Line= 3
      2450974.99     13618975.01      2451175.00     13618825.00
      2451124.99     13618524.96
#Sta/Elev= 30
  4750.6  271.15  4769.0  270.34  4793.3  269.70  4800.6  268.87  4822.5  267.88
  4828.7  268.31  4843.3  267.96  4864.2  266.55  4891.0  262.83  4900.6  261.81
  4914.2  262.55  4943.3  260.75  4950.6  260.84  4957.9  261.76  4978.7  260.70
  4985.1  259.25  4985.3  258.75  4988.8  258.75  4989.1  259.25  4993.3  260.81
  4997.5  259.66  5003.2  259.66  5010.8  261.19  5041.2  263.45  5102.0  265.34
  5142.5  265.28  5173.0  266.80  5183.1  266.25  5213.2  268.35  5304.8  272.24
#Mann=6,-1,0
  4750.6    0.05       0  4769.0    0.07       0  4891.0    0.12       0
  4985.1    0.05       0  4989.1    0.12       0  5213.2    0.07       0
Bank Sta=4985.1,4989.1
Exp/Cntr=0.3,0.1

Type RM Length L Ch R = 1,749,302,302,302
BEGIN DESCRIPTION:
E21338
END DESCRIPTION:
XS GIS Cut Line= 4
      2450999.79     13619151.53      2451307.91     13618938.89
      2451373.01     13618750.09      2451275.34     13618435.38
#Sta/Elev= 30
  4523.0  273.69  4632.0  270.03  4682.7  267.27  4801.5  263.76  4900.6  262.02
  4931.2  259.71  4936.5  258.30  4941.2  258.19  4993.6  258.54  4998.9  256.92
  5005.3  256.13  5005.5  255.63  5009.3  256.13  5017.8  256.23  5024.8  258.27
  5030.1  256.44  5039.0  258.01  5049.6  258.56  5070.7  257.79  5081.3  258.19
  5087.2  260.53  5095.1  260.89  5102.2  261.87  5123.4  262.84  5165.2  263.45
  5186.2  262.95  5196.6  264.25  5249.0  267.09  5345.9  270.64  5426.6  275.04
#Mann=6,-1,0
  4523.0    0.05       0  4801.5    0.07       0  4941.2    0.12       0
  5005.3    0.05       0  5009.3    0.12       0  5095.1    0.07       0
Bank Sta=5005.3,5009.3
Exp/Cntr=0.3,0.1

Type RM Length L Ch R = 1,447,196,196,196
BEGIN DESCRIPTION:
XS7688
END DESCRIPTION:
XS GIS Cut Line= 4
      2450992.68     13619199.10      2451504.48     13619000.07
      2451589.78     13618680.19      2451355.96     13618318.84
#Sta/Elev= 30
  4173.5  274.40  4294.0  270.17  4334.1  268.05  4448.3  264.69  4472.8  263.26
  4502.7  263.30  4527.2  261.90  4589.9  260.60  4649.5  260.02  4769.3  258.49
  4818.8  259.46  4914.2  257.21  4924.5  256.35  4955.6  256.76  4979.2  255.44
  5036.4  254.40  5036.6  253.90  5040.4  254.40  5053.7  254.81  5089.9  260.35
  5095.8  259.19  5105.0  259.51  5111.0  258.31  5121.6  260.06  5126.2  261.23
  5132.1  260.39  5155.2  262.60  5314.4  268.54  5380.1  271.48  5484.1  277.67
#Mann=7,-1,0
  4173.5    0.05       0  4589.9    0.07       0  4649.5    0.12       0
  5036.4    0.05       0  5040.4    0.12       0  5121.6    0.07       0
  5314.4   0.035       0
Bank Sta=5036.4,5040.4
Exp/Cntr=0.3,0.1

Type RM Length L Ch R = 1,251,203,203,203
BEGIN DESCRIPTION:
E21337
END DESCRIPTION:
XS GIS Cut Line= 4
      2451030.10     13619216.68      2451596.54     13619017.01
      2451702.87     13618776.13      2451450.21     13618309.67
#Sta/Elev= 30
  4270.2  272.76  4640.7  260.72  4757.0  258.92  4902.2  257.10  4916.7  255.38
  4925.5  250.86  4929.0  250.74  4929.3  250.24  4933.0  250.74  4948.9  253.32
  5004.0  253.97  5083.4  257.95  5097.7  258.01  5146.8  258.80  5178.7  257.62
  5184.4  254.28  5192.3  253.45  5200.5  256.22  5206.2  253.84  5222.4  257.20
  5228.1  255.73  5244.3  257.33  5250.0  256.21  5260.5  258.15  5266.2  256.95
  5271.9  259.95  5282.3  260.90  5407.9  262.18  5599.8  269.95  5664.6  273.71
#Mann=9,-1,0
  4270.2    0.05       0  4640.7    0.07       0  4757.0    0.12       0
  4929.0    0.05       0  4933.0    0.12       0  5004.0    0.07       0
  5083.4    0.12       0  5097.7    0.07       0  5599.8   0.035       0
Bank Sta=4929,4933
Exp/Cntr=0.3,0.1

Type RM Length L Ch R = 1,48,0,0,0
BEGIN DESCRIPTION:
E21336
END DESCRIPTION:
XS GIS Cut Line= 4
      2451479.34     13619299.14      2451774.49     13619125.52
      2451783.17     13618730.55      2451493.21     13618338.89
#Sta/Elev= 30
  4557.7  257.88  4563.5  257.32  4665.2  256.41  4680.3  257.19  4748.8  255.51
  4781.3  254.54  4791.6  253.24  4813.1  254.70  4834.5  253.79  4842.7  249.99
  4848.2  249.14  4848.4  248.64  4852.2  249.14  4865.8  250.92  4887.3  251.99
  4897.5  254.00  4920.7  255.31  5010.9  255.87  5016.2  256.04  5030.7  255.05
  5040.7  252.76  5070.7  249.49  5090.7  250.75  5100.7  250.17  5115.9  255.02
  5120.7  256.55  5130.7  257.09  5220.7  256.97  5590.4  262.16  5782.5  270.60
#Mann=10,-1,0
  4557.7    0.07       0  4563.5    0.05       0  4665.2    0.12       0
  4748.8    0.07       0  4781.3    0.12       0  4848.2    0.05       0
  4852.2    0.12       0  5010.9    0.07       0  5016.2    0.12       0
  5115.9    0.07       0
Bank Sta=4848.2,4852.2
Exp/Cntr=0.3,0.1

Chan Stop Cuts=-1