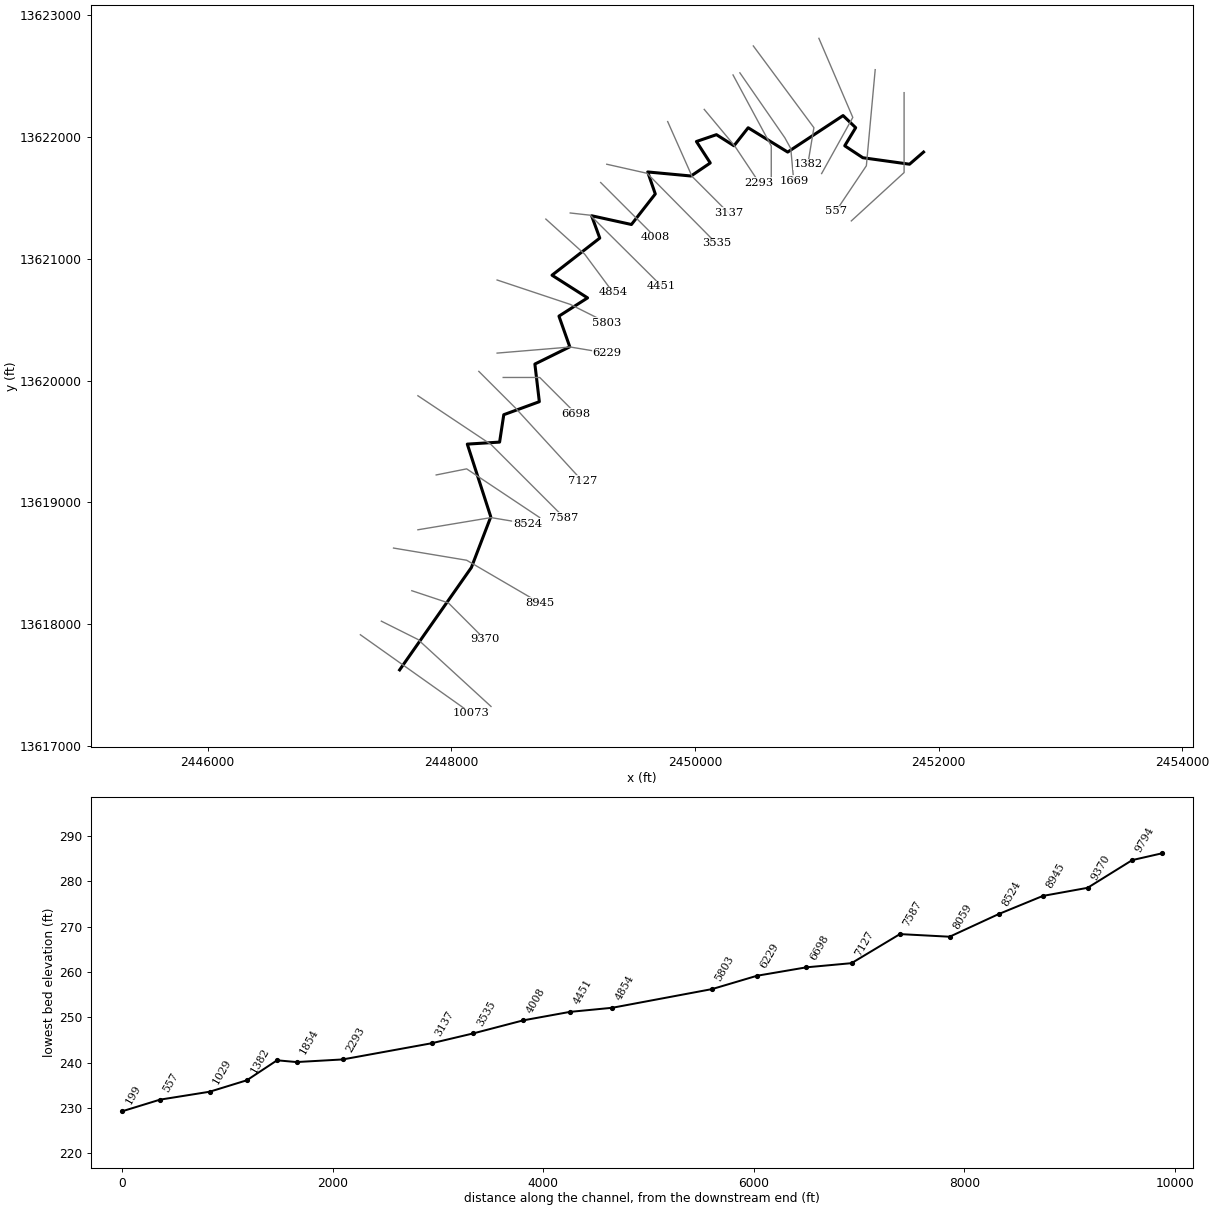
--- Stream0767.prj (project) ---

Proj Title=Stream0767 Base Level Engineering
Current Plan=p01
Default Exp/Contr=0.3,0.1
English Units
Geom File=g01
Flow File=f01
Plan File=p01
BEGIN DESCRIPTION:
Stream0767
END DESCRIPTION:

--- Stream0767.p01 (plan) ---

Plan Title=Multiple Run
Short Identifier=Multiple
Geom File=g01
Flow File=f01
Subcritical Flow
K Sum by GR= 0
Std Step Tol= 0.01
Critical Tol= 0.01
Num of Std Step Trials= 20
Max Error Tol= 0.3
Flow Tol Ratio= 0.001
Split Flow NTrial= 30
Split Flow Tol= 0.02
Split Flow Ratio= 0.02
Log Output Level= 0
Friction Slope Method= 1
Unsteady Friction Slope Method= 2
Unsteady Bridges Friction Slope Method= 1
Parabolic Critical Depth
Global Vel Dist=  1 , 1 , 1
Global Log Level= 0
CheckData=True
Encroach Param= -1, 0, 0, 0
BEGIN DESCRIPTION:
Multiple Run
END DESCRIPTION:

--- Stream0767.f01 (steady flow) ---

Flow Title=Multiple
Number of Profiles=7
Profile Names=10-year,25-year,50-year,1pct_min,100-year,1pct_plu,500-year
River Rch & RM= Stream0767,Reach-1,10073
     629    1013    1359     883    1763    3517    2937
Boundary for River Rch & Prof#=Stream0767,Reach-1,1
Up Type=0
Dn Type=3
Dn Slope=0.005
Boundary for River Rch & Prof#=Stream0767,Reach-1,2
Up Type=0
Dn Type=3
Dn Slope=0.005
Boundary for River Rch & Prof#=Stream0767,Reach-1,3
Up Type=0
Dn Type=3
Dn Slope=0.005
Boundary for River Rch & Prof#=Stream0767,Reach-1,4
Up Type=0
Dn Type=3
Dn Slope=0.005
Boundary for River Rch & Prof#=Stream0767,Reach-1,5
Up Type=0
Dn Type=3
Dn Slope=0.005
Boundary for River Rch & Prof#=Stream0767,Reach-1,6
Up Type=0
Dn Type=3
Dn Slope=0.005
Boundary for River Rch & Prof#=Stream0767,Reach-1,7
Up Type=0
Dn Type=3
Dn Slope=0.005

--- Stream0767.g01 (geometry) ---

Geom Title=Existing Conditions

River Reach=Stream0767,Reach-1
Reach XY= 30
      2447575.00     13617625.00      2448163.74     13618465.01
      2448323.21     13618881.11      2448130.46     13619478.02
      2448395.48     13619494.61      2448429.80     13619719.44
      2448721.55     13619826.25      2448685.03     13620135.06
      2448971.48     13620276.46      2448882.59     13620528.35
      2449117.50     13620678.14      2448825.68     13620864.25
      2449217.54     13621168.95      2449150.53     13621352.30
      2449477.45     13621280.45      2449673.24     13621531.12
      2449610.85     13621711.66      2449966.54     13621678.46
      2450124.54     13621785.52      2450010.84     13621961.57
      2450175.10     13622017.67      2450319.13     13621926.51
      2450435.49     13622074.51      2450759.79     13621874.89
      2451214.39     13622174.40      2451317.92     13622075.02
      2451228.01     13621926.43      2451376.72     13621828.34
      2451759.79     13621775.22      2451875.00     13621875.00

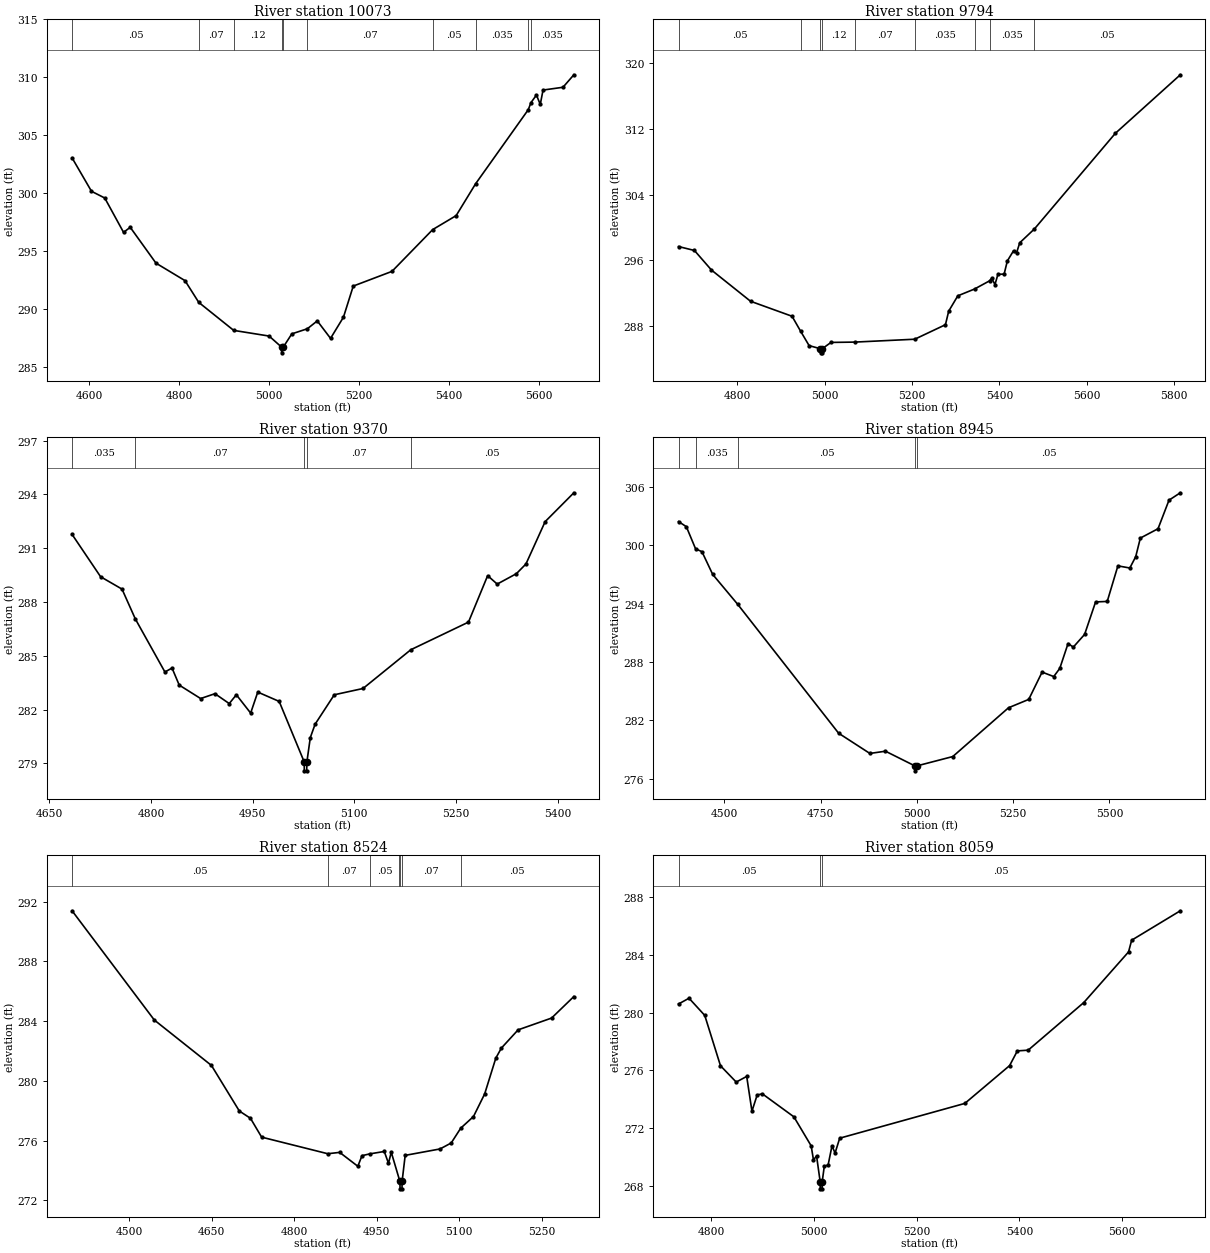
Type RM Length L Ch R = 1,10073,279,279,279
BEGIN DESCRIPTION:
XS7691
END DESCRIPTION:
XS GIS Cut Line= 2
      2447252.78     13617913.57      2448162.89     13617268.22
#Sta/Elev= 30
  4561.7  303.04  4604.9  300.15  4634.4  299.57  4676.2  296.60  4691.0  297.04
  4748.3  293.94  4812.8  292.43  4843.4  290.55  4921.1  288.13  4999.8  287.64
  5027.4  286.69  5027.6  286.19  5031.4  286.69  5050.3  287.83  5084.8  288.27
  5106.9  288.95  5136.4  287.44  5165.1  289.27  5186.9  291.96  5273.0  293.23
  5363.5  296.84  5415.7  298.05  5458.9  300.80  5576.0  307.20  5582.0  307.81
  5594.2  308.47  5602.7  307.66  5608.9  308.90  5653.2  309.14  5677.4  310.22
#Mann=10,-1,0
  4561.7    0.05       0  4843.4    0.07       0  4921.1    0.12       0
  5027.4    0.05       0  5031.4    0.12       0  5084.8    0.07       0
  5363.5    0.05       0  5458.9   0.035       0  5576.0    0.05       0
  5582.0   0.035       0
Bank Sta=5027.4,5031.4
Exp/Cntr=0.3,0.1

Type RM Length L Ch R = 1,9794,424,424,424
BEGIN DESCRIPTION:
Stream0767 19.0
END DESCRIPTION:
XS GIS Cut Line= 3
      2447424.98     13618025.01      2447725.00     13617875.00
      2448325.02     13617324.98
#Sta/Elev= 30
  4665.1  297.67  4701.5  297.19  4740.6  294.80  4830.0  291.00  4925.1  289.17
  4944.7  287.35  4964.2  285.59  4990.1  285.21  4990.4  284.71  4993.9  284.71
  4994.1  285.21  5014.4  285.98  5069.0  286.02  5206.1  286.37  5276.5  288.14
  5283.9  289.79  5304.8  291.66  5343.1  292.49  5377.6  293.49  5382.5  293.81
  5389.9  293.03  5396.7  294.28  5410.9  294.31  5418.3  295.92  5432.5  297.16
  5439.3  296.89  5446.7  298.13  5480.2  299.81  5665.6  311.47  5814.5  318.61
#Mann=9,-1,0
  4665.1    0.05       0  4944.7    0.12       0  4990.1    0.05       0
  4994.1    0.12       0  5069.0    0.07       0  5206.1   0.035       0
  5343.1    0.07       0  5377.6   0.035       0  5480.2    0.05       0
Bank Sta=4990.1,4994.1
Exp/Cntr=0.3,0.1

Type RM Length L Ch R = 1,9370,425,425,425
BEGIN DESCRIPTION:
Stream0767 18.0
END DESCRIPTION:
XS GIS Cut Line= 3
      2447675.04     13618274.99      2447975.00     13618175.00
      2448274.97     13617875.03
#Sta/Elev= 30
  4683.6  291.77  4725.7  289.41  4757.3  288.72  4776.9  287.06  4820.6  284.10
  4831.1  284.32  4841.7  283.37  4873.3  282.62  4894.4  282.89  4915.5  282.34
  4926.0  282.83  4947.1  281.81  4957.6  282.98  4989.2  282.46  5026.1  279.09
  5026.3  278.59  5029.8  278.59  5030.1  279.09  5035.1  280.44  5042.2  281.19
  5070.5  282.83  5112.9  283.18  5183.4  285.34  5268.5  286.88  5296.8  289.47
  5310.9  289.00  5339.2  289.58  5353.3  290.12  5381.6  292.48  5424.0  294.09
#Mann=5,-1,0
  4683.6   0.035       0  4776.9    0.07       0  5026.1    0.05       0
  5030.1    0.07       0  5183.4    0.05       0
Bank Sta=5026.1,5030.1
Exp/Cntr=0.3,0.1

Type RM Length L Ch R = 1,8945,421,421,421
BEGIN DESCRIPTION:
Stream0767 17.0
END DESCRIPTION:
XS GIS Cut Line= 3
      2447525.00     13618625.00      2448125.00     13618525.00
      2448725.00     13618175.00
#Sta/Elev= 30
  4381.3  302.45  4401.6  301.92  4425.6  299.64  4442.1  299.35  4470.0  297.01
  4535.2  293.92  4797.0  280.67  4878.1  278.59  4918.6  278.82  4995.4  277.30
  4995.7  276.80  4999.4  277.30  5093.4  278.27  5238.1  283.29  5290.6  284.15
  5325.3  286.96  5355.5  286.50  5371.2  287.34  5392.7  289.90  5406.3  289.53
  5435.7  290.84  5464.2  294.18  5494.4  294.23  5522.1  297.89  5553.1  297.67
  5568.4  298.84  5580.4  300.75  5626.3  301.71  5654.8  304.65  5684.2  305.41
#Mann=5,-1,0
  4381.3    0.05       0  4425.6   0.035       0  4535.2    0.05       0
  4995.4    0.05       0  4999.4    0.05       0
Bank Sta=4995.4,4999.4
Exp/Cntr=0.3,0.1

Type RM Length L Ch R = 1,8524,465,465,465
BEGIN DESCRIPTION:
Stream0767 16.0
END DESCRIPTION:
XS GIS Cut Line= 3
      2447725.00     13618775.00      2448325.00     13618875.00
      2448624.99     13618825.00
#Sta/Elev= 30
  4396.4  291.39  4545.9  284.08  4649.8  281.04  4700.5  277.99  4720.8  277.50
  4741.1  276.24  4861.3  275.13  4883.0  275.22  4916.0  274.29  4923.6  275.00
  4937.7  275.12  4964.1  275.28  4971.7  274.49  4976.8  275.23  4991.5  273.40
  4992.5  273.28  4992.8  272.78  4996.3  272.78  4996.5  273.28  5002.1  275.02
  5065.5  275.45  5085.8  275.85  5103.1  276.84  5126.3  277.62  5146.6  279.13
  5166.9  281.53  5177.0  282.20  5207.4  283.42  5268.3  284.21  5308.8  285.65
#Mann=7,-1,0
  4396.4    0.05       0  4861.3    0.07       0  4937.7    0.05       0
  4991.5    0.07       0  4992.5    0.05       0  4996.5    0.07       0
  5103.1    0.05       0
Bank Sta=4992.5,4996.5
Exp/Cntr=0.3,0.1

Type RM Length L Ch R = 1,8059,472,472,472
BEGIN DESCRIPTION:
Stream0767 15.0
END DESCRIPTION:
XS GIS Cut Line= 3
      2447875.00     13619225.00      2448125.00     13619275.00
      2448725.03     13618874.98
#Sta/Elev= 30
  4736.9  280.60  4757.3  281.00  4787.9  279.81  4818.5  276.32  4849.1  275.19
  4869.5  275.58  4879.7  273.17  4889.9  274.30  4900.1  274.37  4961.3  272.78
  4994.9  270.77  4999.4  269.79  5005.4  270.07  5012.4  268.29  5012.6  267.79
  5016.1  267.79  5016.4  268.29  5020.4  269.35  5027.9  269.45  5035.4  270.77
  5041.4  270.27  5050.4  271.30  5293.8  273.71  5380.9  276.33  5396.0  277.35
  5417.0  277.40  5525.2  280.70  5612.3  284.21  5618.3  285.02  5713.0  287.06
#Mann=3,-1,0
  4736.9    0.05       0  5012.4    0.05       0  5016.4    0.05       0
Bank Sta=5012.4,5016.4
Exp/Cntr=0.3,0.1

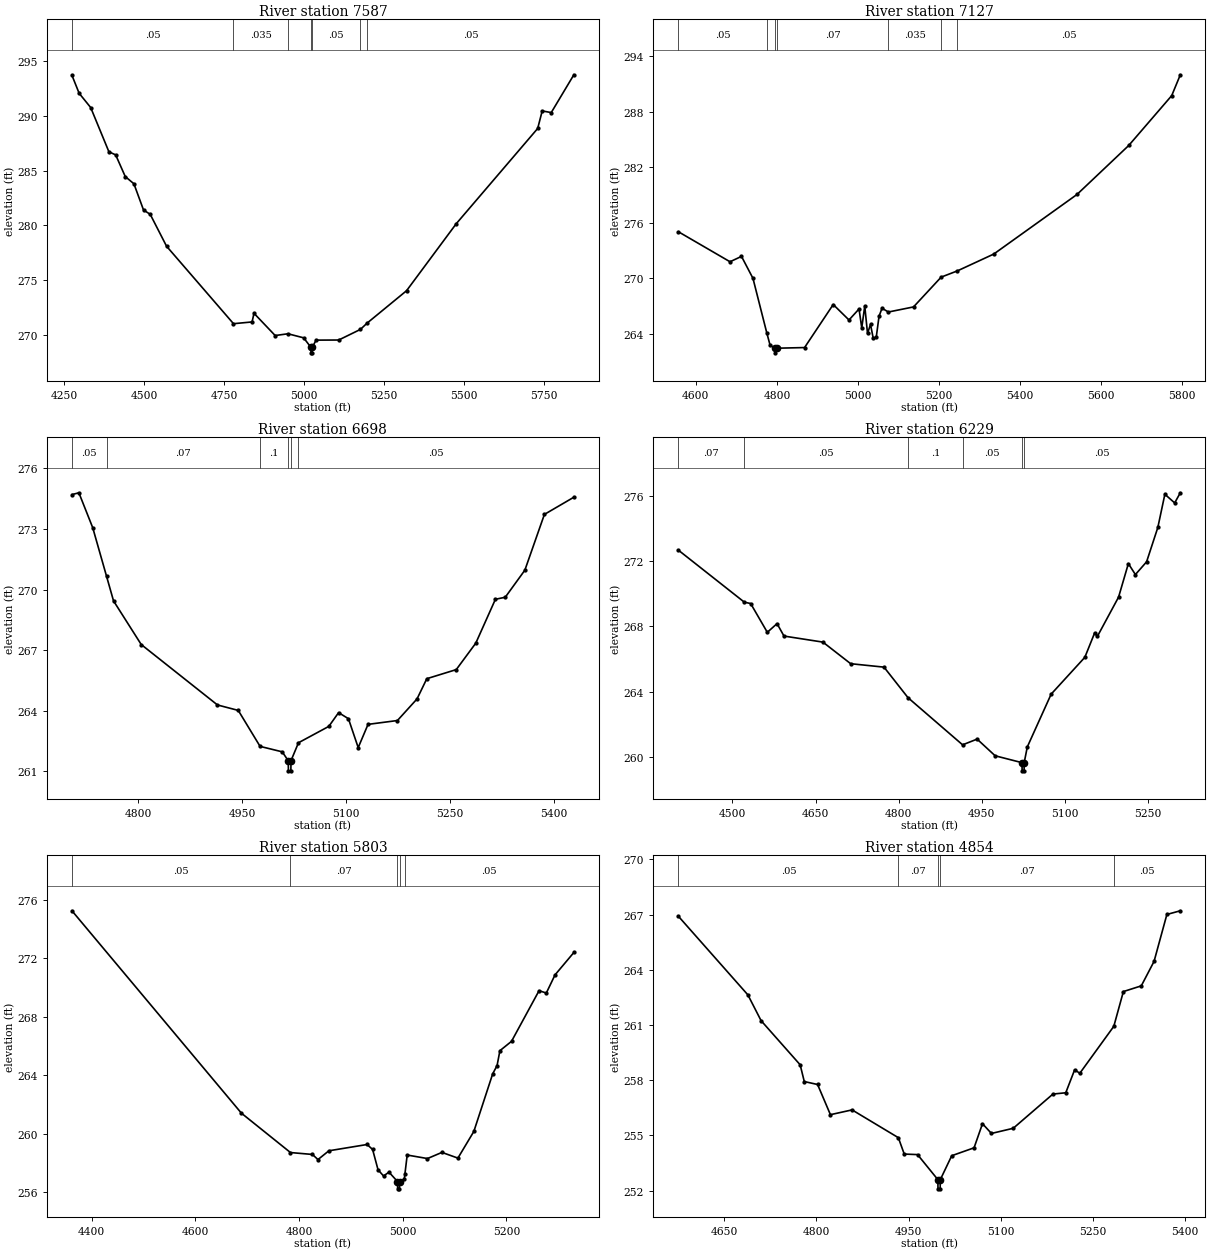
Type RM Length L Ch R = 1,7587,460,460,460
BEGIN DESCRIPTION:
Stream0767 14.0
END DESCRIPTION:
XS GIS Cut Line= 3
      2447725.02     13619874.98      2448325.00     13619475.00
      2448924.99     13618875.01
#Sta/Elev= 30
  4273.6  293.70  4296.1  292.06  4332.2  290.76  4389.2  286.72  4410.3  286.44
  4440.3  284.46  4467.4  283.80  4497.4  281.41  4518.4  281.01  4569.5  278.10
  4778.8  271.03  4836.9  271.19  4842.9  271.98  4909.1  269.95  4949.1  270.11
  4998.2  269.74  5021.0  268.87  5021.2  268.37  5024.7  268.37  5025.0  268.87
  5037.1  269.53  5107.8  269.54  5175.8  270.51  5196.5  271.08  5320.0  274.04
  5475.5  280.16  5730.1  288.85  5744.2  290.45  5772.5  290.30  5843.2  293.75
#Mann=7,-1,0
  4273.6    0.05       0  4778.8   0.035       0  4949.1    0.05       0
  5021.0    0.05       0  5025.0    0.05       0  5175.8    0.07       0
  5196.5    0.05       0
Bank Sta=5021,5025
Exp/Cntr=0.3,0.1

Type RM Length L Ch R = 1,7127,429,429,429
BEGIN DESCRIPTION:
Stream0767 13.0
END DESCRIPTION:
XS GIS Cut Line= 3
      2448224.98     13620075.02      2448525.00     13619775.00
      2449074.98     13619175.02
#Sta/Elev= 30
  4557.0  275.03  4684.3  271.79  4712.6  272.37  4740.9  270.00  4775.1  264.09
  4783.3  262.75  4795.4  262.45  4795.7  261.95  4799.4  262.45  4868.2  262.52
  4938.9  267.17  4977.8  265.50  5002.6  266.69  5009.3  264.64  5016.7  267.01
  5023.5  264.05  5030.9  265.02  5037.7  263.50  5045.1  263.65  5051.9  265.89
  5059.3  266.77  5075.0  266.36  5137.0  266.91  5205.2  270.13  5245.0  270.80
  5334.9  272.62  5540.3  279.06  5667.9  284.35  5774.0  289.74  5795.2  291.99
#Mann=7,-1,0
  4557.0    0.05       0  4775.1    0.07       0  4795.4    0.05       0
  4799.4    0.07       0  5075.0   0.035       0  5205.2    0.07       0
  5245.0    0.05       0
Bank Sta=4795.4,4799.4
Exp/Cntr=0.3,0.1

Type RM Length L Ch R = 1,6698,469,469,469
BEGIN DESCRIPTION:
Stream0767 12.0
END DESCRIPTION:
XS GIS Cut Line= 3
      2448425.00     13620025.00      2448725.00     13620025.00
      2449025.03     13619724.97
#Sta/Elev= 30
  4704.6  274.70  4714.6  274.79  4734.6  273.06  4754.6  270.65  4764.6  269.44
  4804.6  267.28  4914.6  264.29  4944.6  264.02  4976.1  262.24  5008.1  261.97
  5016.7  261.53  5017.0  261.03  5020.5  261.03  5020.7  261.53  5031.5  262.42
  5075.3  263.23  5089.4  263.91  5103.6  263.61  5117.7  262.18  5131.9  263.33
  5174.3  263.52  5202.6  264.59  5216.7  265.59  5259.2  266.04  5287.4  267.35
  5315.7  269.52  5329.9  269.62  5358.2  270.96  5386.4  273.72  5428.9  274.57
#Mann=6,-1,0
  4704.6    0.05       0  4754.6    0.07       0  4976.1     0.1       0
  5016.7    0.05       0  5020.7     0.1       0  5031.5    0.05       0
Bank Sta=5016.7,5020.7
Exp/Cntr=0.3,0.1

Type RM Length L Ch R = 1,6229,426,426,426
BEGIN DESCRIPTION:
Stream0767 11.0
END DESCRIPTION:
XS GIS Cut Line= 3
      2448375.05     13620225.00      2448975.00     13620275.00
      2449275.03     13620225.00
#Sta/Elev= 30
  4402.4  272.66  4521.5  269.48  4532.8  269.40  4562.9  267.64  4580.5  268.17
  4593.0  267.41  4663.3  267.04  4713.4  265.72  4773.6  265.51  4817.0  263.64
  4915.5  260.76  4941.7  261.11  4974.3  260.09  5022.7  259.67  5023.0  259.17
  5026.5  259.17  5026.7  259.67  5032.3  260.63  5075.4  263.86  5136.2  266.11
  5154.0  267.61  5159.0  267.40  5197.1  269.79  5214.8  271.84  5227.5  271.17
  5247.7  271.95  5268.0  274.05  5280.7  276.08  5298.4  275.55  5308.6  276.17
#Mann=6,-1,0
  4402.4    0.07       0  4521.5    0.05       0  4817.0     0.1       0
  4915.5    0.05       0  5022.7    0.05       0  5026.7    0.05       0
Bank Sta=5022.7,5026.7
Exp/Cntr=0.3,0.1

Type RM Length L Ch R = 1,5803,949,949,949
BEGIN DESCRIPTION:
Stream0767 10.0
END DESCRIPTION:
XS GIS Cut Line= 3
      2448374.97     13620825.01      2448975.00     13620625.00
      2449275.01     13620475.00
#Sta/Elev= 30
  4362.0  275.23  4688.8  261.40  4783.4  258.71  4825.8  258.58  4836.4  258.23
  4857.5  258.83  4931.2  259.26  4941.8  258.92  4952.3  257.53  4962.9  257.11
  4973.4  257.37  4989.8  256.73  4990.1  256.23  4993.6  256.23  4993.8  256.73
  5002.9  256.89  5004.0  257.21  5008.5  258.54  5047.6  258.30  5075.5  258.72
  5106.3  258.33  5137.0  260.15  5173.4  264.09  5181.8  264.65  5187.3  265.67
  5209.7  266.31  5262.8  269.77  5276.8  269.61  5293.6  270.85  5329.9  272.38
#Mann=5,-1,0
  4362.0    0.05       0  4783.4    0.07       0  4989.8    0.05       0
  4993.8    0.07       0  5004.0    0.05       0
Bank Sta=4989.8,4993.8
Exp/Cntr=0.3,0.1

Type RM Length L Ch R = 1,4854,403,403,403
BEGIN DESCRIPTION:
Stream0767 9.0
END DESCRIPTION:
XS GIS Cut Line= 3
      2448775.02     13621324.98      2449093.45     13621037.34
      2449324.99     13620725.01
#Sta/Elev= 30
  4575.0  266.91  4688.2  262.64  4709.7  261.24  4773.4  258.84  4780.1  257.93
  4801.8  257.77  4822.7  256.13  4858.0  256.39  4933.4  254.88  4943.0  253.99
  4964.7  253.96  4997.8  252.60  4998.0  252.10  5001.5  252.10  5001.8  252.60
  5020.4  253.90  5056.8  254.33  5070.5  255.64  5085.1  255.11  5120.6  255.39
  5185.3  257.25  5206.2  257.32  5220.7  258.57  5229.1  258.38  5284.5  260.93
  5300.1  262.82  5329.3  263.13  5350.1  264.46  5371.0  267.01  5392.9  267.21
#Mann=5,-1,0
  4575.0    0.05       0  4933.4    0.07       0  4997.8    0.05       0
  5001.8    0.07       0  5284.5    0.05       0
Bank Sta=4997.8,5001.8
Exp/Cntr=0.3,0.1

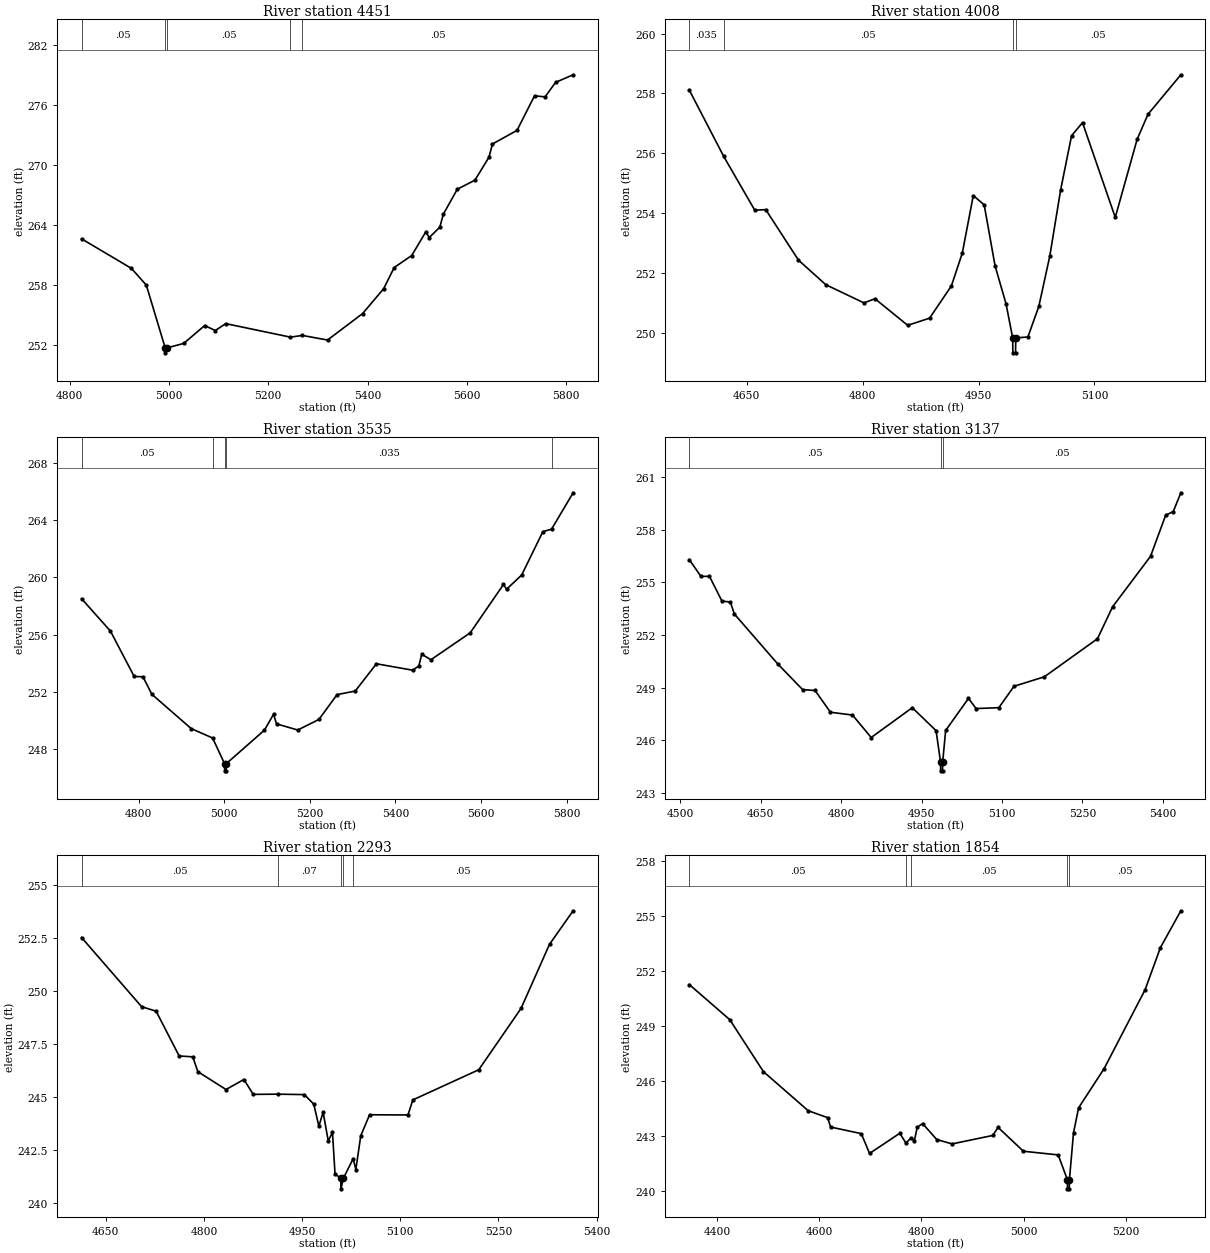
Type RM Length L Ch R = 1,4451,443,443,443
BEGIN DESCRIPTION:
Stream0767 8.0
END DESCRIPTION:
XS GIS Cut Line= 3
      2448975.04     13621375.00      2449139.08     13621356.70
      2449725.00     13620775.00
#Sta/Elev= 30
  4823.7  262.59  4924.3  259.63  4954.2  257.96  4992.2  251.69  4992.4  251.19
  4996.2  251.69  5029.5  252.13  5071.9  253.92  5093.2  253.42  5114.3  254.11
  5244.7  252.76  5268.7  252.93  5319.4  252.47  5390.2  255.12  5432.6  257.61
  5453.8  259.72  5489.1  260.92  5517.4  263.28  5524.5  262.72  5545.7  263.75
  5552.8  265.05  5581.0  267.55  5616.4  268.45  5644.7  270.74  5651.8  272.07
  5701.3  273.43  5736.6  276.89  5757.9  276.78  5779.0  278.23  5814.4  278.99
#Mann=5,-1,0
  4823.7    0.05       0  4992.2    0.05       0  4996.2    0.05       0
  5244.7    0.07       0  5268.7    0.05       0
Bank Sta=4992.2,4996.2
Exp/Cntr=0.3,0.1

Type RM Length L Ch R = 1,4008,473,473,473
BEGIN DESCRIPTION:
Stream0767 7.0
END DESCRIPTION:
XS GIS Cut Line= 3
      2449225.02     13621624.98      2449525.00     13621325.00
      2449675.02     13621174.98
#Sta/Elev= 30
  4575.5  258.11  4620.1  255.89  4660.3  254.09  4674.5  254.11  4716.9  252.42
  4752.2  251.60  4801.7  250.99  4815.9  251.13  4858.3  250.24  4886.6  250.48
  4914.9  251.56  4929.0  252.66  4943.2  254.58  4957.3  254.27  4971.4  252.23
  4985.6  250.96  4994.2  249.82  4994.4  249.32  4997.9  249.32  4998.2  249.82
  5013.9  249.85  5028.0  250.87  5042.2  252.55  5056.3  254.77  5070.4  256.58
  5084.6  257.02  5127.0  253.85  5155.3  256.46  5169.4  257.30  5211.9  258.62
#Mann=4,-1,0
  4575.5   0.035       0  4620.1    0.05       0  4994.2    0.05       0
  4998.2    0.05       0
Bank Sta=4994.2,4998.2
Exp/Cntr=0.3,0.1

Type RM Length L Ch R = 1,3535,398,398,398
BEGIN DESCRIPTION:
Stream0767 6.0
END DESCRIPTION:
XS GIS Cut Line= 3
      2449275.03     13621774.99      2449605.83     13621700.63
      2450175.02     13621124.98
#Sta/Elev= 30
  4666.7  258.51  4734.2  256.24  4789.7  253.06  4810.2  253.04  4831.0  251.81
  4922.9  249.41  4972.9  248.75  5000.8  246.95  5001.0  246.45  5004.5  246.45
  5004.8  246.95  5094.0  249.30  5115.2  250.41  5122.3  249.74  5171.8  249.31
  5221.3  250.05  5263.7  251.79  5306.2  252.04  5355.6  253.95  5440.5  253.50
  5454.6  253.79  5461.7  254.62  5482.9  254.23  5574.9  256.12  5652.6  259.51
  5659.7  259.17  5695.1  260.17  5744.6  263.21  5764.9  263.38  5815.3  265.93
#Mann=5,-1,0
  4666.7    0.05       0  4972.9   0.035       0  5000.8   0.035       0
  5004.8   0.035       0  5764.9    0.07       0
Bank Sta=5000.8,5004.8
Exp/Cntr=0.3,0.1

Type RM Length L Ch R = 1,3137,844,844,844
BEGIN DESCRIPTION:
Stream0767 5.0
END DESCRIPTION:
XS GIS Cut Line= 3
      2449774.99     13622125.02      2449975.00     13621675.00
      2450274.98     13621375.02
#Sta/Elev= 30
  4516.7  256.30  4538.6  255.34  4554.3  255.35  4577.6  253.94  4593.3  253.88
  4600.8  253.20  4681.5  250.36  4728.1  248.89  4751.3  248.84  4780.0  247.60
  4821.1  247.44  4856.0  246.16  4932.6  247.86  4977.0  246.55  4985.3  244.76
  4985.5  244.26  4989.0  244.26  4989.3  244.76  4994.8  246.56  5037.4  248.39
  5051.6  247.81  5094.0  247.86  5122.3  249.08  5178.9  249.62  5277.9  251.79
  5306.1  253.61  5376.9  256.49  5405.1  258.83  5419.3  259.04  5433.4  260.11
#Mann=3,-1,0
  4516.7    0.05       0  4985.3    0.05       0  4989.3    0.05       0
Bank Sta=4985.3,4989.3
Exp/Cntr=0.3,0.1

Type RM Length L Ch R = 1,2293,439,439,439
BEGIN DESCRIPTION:
Stream0767 4.0
END DESCRIPTION:
XS GIS Cut Line= 3
      2450074.98     13622225.03      2450325.00     13621925.00
      2450525.00     13621625.00
#Sta/Elev= 30
  4613.0  252.53  4704.8  249.27  4726.9  249.06  4762.1  246.95  4782.9  246.91
  4790.7  246.21  4833.7  245.37  4861.0  245.84  4875.3  245.14  4913.1  245.15
  4953.4  245.13  4967.8  244.68  4975.6  243.64  4982.1  244.30  4989.9  242.95
  4996.4  243.35  5000.3  241.39  5009.1  241.19  5009.3  240.69  5013.1  241.19
  5028.0  242.11  5032.1  241.60  5039.6  243.19  5053.1  244.18  5111.7  244.17
  5119.2  244.88  5219.9  246.30  5284.5  249.19  5328.0  252.21  5364.1  253.79
#Mann=5,-1,0
  4613.0    0.05       0  4913.1    0.07       0  5009.1    0.05       0
  5013.1    0.07       0  5028.0    0.05       0
Bank Sta=5009.1,5013.1
Exp/Cntr=0.3,0.1

Type RM Length L Ch R = 1,1854,185,185,185
BEGIN DESCRIPTION:
Stream0767 3.0
END DESCRIPTION:
XS GIS Cut Line= 3
      2450311.23     13622507.80      2450625.00     13621925.00
      2450625.00     13621625.00
#Sta/Elev= 30
  4345.6  251.25  4425.0  249.33  4490.7  246.50  4578.3  244.37  4616.5  243.99
  4622.1  243.48  4682.2  243.12  4698.4  242.04  4757.6  243.14  4769.4  242.61
  4779.7  242.88  4786.0  242.72  4791.7  243.47  4802.2  243.67  4829.8  242.80
  4859.9  242.56  4939.4  243.02  4949.9  243.46  4999.4  242.16  5067.5  241.96
  5085.5  240.61  5085.7  240.11  5089.2  240.11  5089.5  240.61  5097.5  243.17
  5107.5  244.53  5157.5  246.67  5237.5  250.96  5267.5  253.26  5307.5  255.27
#Mann=5,-1,0
  4345.6    0.05       0  4769.4    0.07       0  4779.7    0.05       0
  5085.5    0.05       0  5089.5    0.05       0
Bank Sta=5085.5,5089.5
Exp/Cntr=0.3,0.1

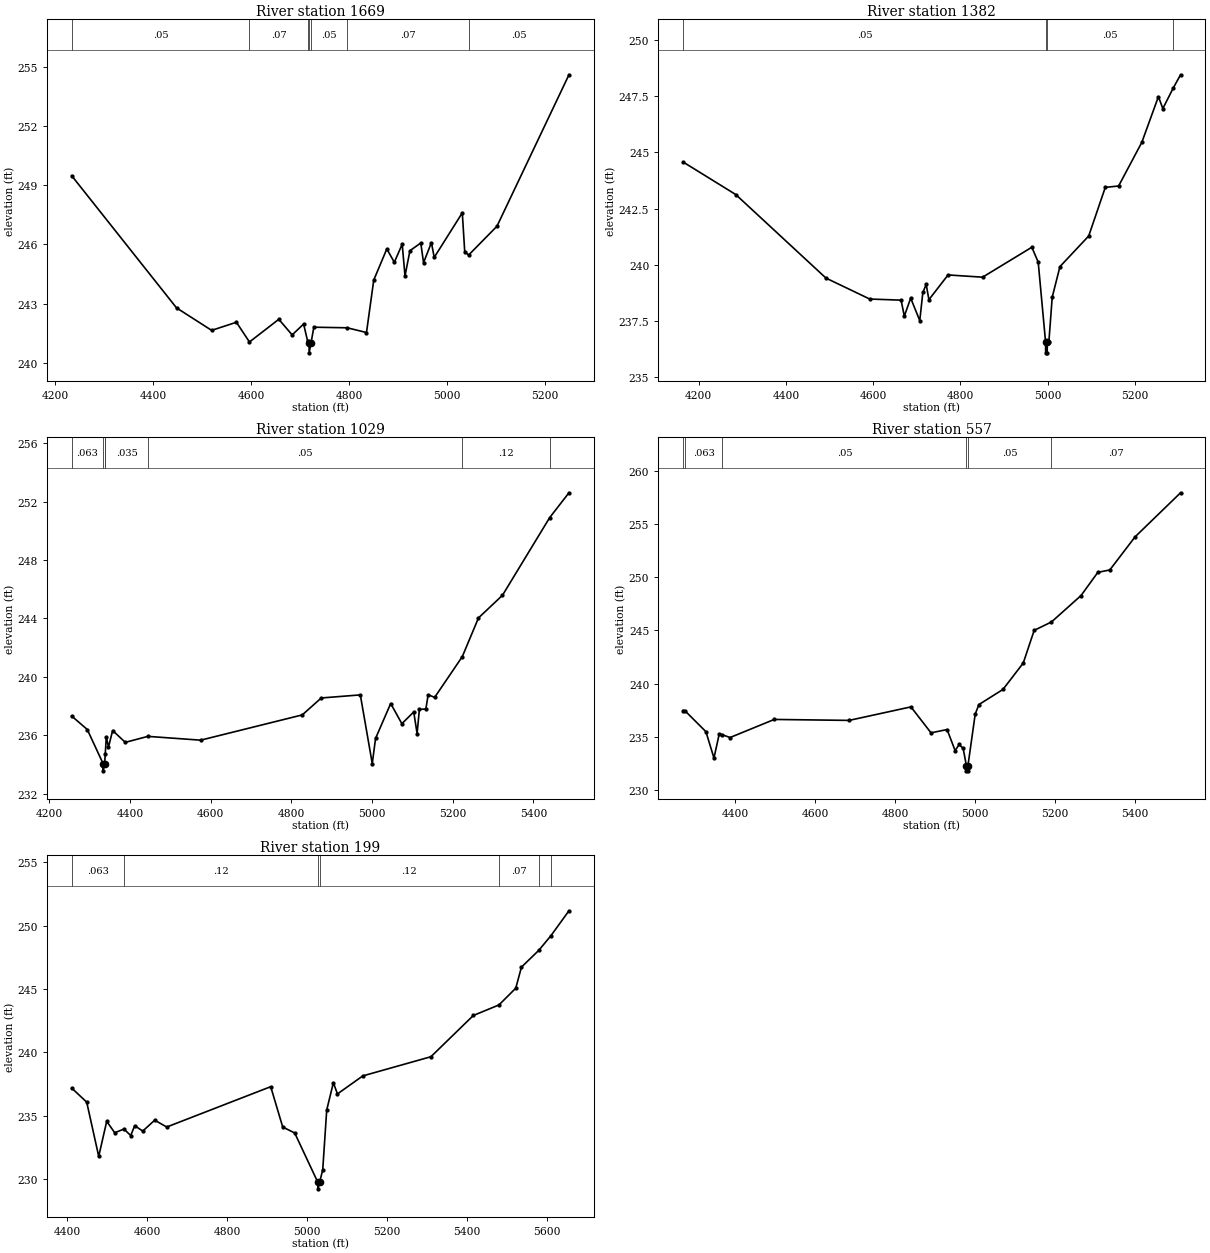
Type RM Length L Ch R = 1,1669,287,287,287
BEGIN DESCRIPTION:
Stream0767 3.0a
END DESCRIPTION:
XS GIS Cut Line= 4
      2450367.54     13622525.05      2450736.51     13621992.10
      2450785.19     13621903.70      2450809.40     13621638.63
#Sta/Elev= 30
  4233.6  249.48  4447.6  242.78  4519.3  241.64  4569.9  242.05  4596.5  241.05
  4656.4  242.20  4683.7  241.41  4707.1  241.96  4715.1  241.11  4718.2  241.00
  4718.4  240.50  4722.2  241.00  4728.0  241.80  4796.1  241.77  4835.5  241.53
  4850.3  244.19  4877.0  245.77  4892.3  245.09  4908.4  246.01  4914.1  244.40
  4924.2  245.68  4946.3  246.07  4952.0  245.07  4968.0  246.09  4973.8  245.34
  5031.1  247.60  5036.1  245.62  5044.1  245.46  5101.9  246.92  5248.9  254.60
#Mann=7,-1,0
  4233.6    0.05       0  4596.5    0.07       0  4715.1    0.05       0
  4718.2    0.05       0  4722.2    0.05       0  4796.1    0.07       0
  5044.1    0.05       0
Bank Sta=4718.2,4722.2
Exp/Cntr=0.3,0.1

Type RM Length L Ch R = 1,1382,353,353,353
BEGIN DESCRIPTION:
Stream0767 2.0
END DESCRIPTION:
XS GIS Cut Line= 3
      2450477.81     13622745.77      2450975.00     13622075.00
      2450925.00     13621774.99
#Sta/Elev= 30
  4165.1  244.56  4285.3  243.12  4491.9  239.41  4592.1  238.48  4664.0  238.43
  4671.4  237.72  4686.0  238.52  4706.8  237.52  4713.8  238.77  4721.5  239.13
  4727.7  238.45  4771.6  239.55  4850.7  239.45  4963.5  240.78  4978.1  240.12
  4994.9  236.59  4995.2  236.09  4998.7  236.09  4998.9  236.59  5002.6  236.59
  5010.2  238.56  5027.9  239.92  5093.8  241.28  5131.8  243.44  5162.3  243.50
  5215.5  245.44  5253.5  247.47  5263.6  246.94  5287.4  247.85  5304.2  248.44
#Mann=4,-1,0
  4165.1    0.05       0  4994.9    0.05       0  4998.9    0.05       0
  5287.4    0.07       0
Bank Sta=4994.9,4998.9
Exp/Cntr=0.3,0.1

Type RM Length L Ch R = 1,1029,472,472,472
BEGIN DESCRIPTION:
Stream0767 1.0
END DESCRIPTION:
XS GIS Cut Line= 3
      2451015.99     13622808.29      2451294.17     13622159.22
      2451038.47     13621698.48
#Sta/Elev= 30
  4255.2  237.31  4293.8  236.39  4332.9  234.06  4333.2  233.56  4336.9  234.06
  4338.3  234.68  4341.0  235.88  4346.4  235.19  4356.7  236.32  4388.1  235.51
  4444.1  235.92  4574.9  235.66  4826.9  237.39  4874.1  238.55  4970.9  238.76
  5000.5  234.06  5008.7  235.78  5046.2  238.17  5073.9  236.79  5103.4  237.59
  5111.7  236.11  5117.4  237.77  5133.4  237.79  5139.1  238.77  5155.2  238.59
  5223.8  241.38  5263.9  244.03  5323.4  245.58  5440.5  250.90  5488.3  252.60
#Mann=7,-1,0
  4255.2   0.063       0  4332.9    0.05       0  4336.9   0.063       0
  4338.3   0.035       0  4444.1    0.05       0  5223.8    0.12       0
  5440.5    0.05       0
Bank Sta=4332.9,4336.9
Exp/Cntr=0.3,0.1

Type RM Length L Ch R = 1,557,358,358,358
BEGIN DESCRIPTION:
E21343
END DESCRIPTION:
XS GIS Cut Line= 3
      2451478.07     13622551.26      2451405.48     13621762.37
      2451154.71     13621388.63
#Sta/Elev= 30
  4271.0  237.48  4275.8  237.43  4327.5  235.49  4347.6  233.01  4360.9  235.30
  4368.7  235.20  4387.8  234.94  4498.2  236.64  4685.2  236.55  4839.7  237.82
  4889.9  235.38  4930.0  235.69  4950.1  233.71  4960.2  234.29  4970.2  233.91
  4978.2  232.31  4978.5  231.81  4982.0  231.81  4982.2  232.31  5000.3  237.15
  5009.6  238.04  5069.6  239.46  5120.3  241.94  5147.6  245.01  5190.8  245.80
  5264.6  248.28  5306.6  250.46  5336.6  250.69  5399.7  253.80  5513.3  257.94
#Mann=6,-1,0
  4271.0   0.094       0  4275.8   0.063       0  4368.7    0.05       0
  4978.2    0.05       0  4982.2    0.05       0  5190.8    0.07       0
Bank Sta=4978.2,4982.2
Exp/Cntr=0.3,0.1

Type RM Length L Ch R = 1,199,0,0,0
BEGIN DESCRIPTION:
E21342
END DESCRIPTION:
XS GIS Cut Line= 3
      2451715.21     13622362.47      2451715.21     13621706.72
      2451282.14     13621309.94
#Sta/Elev= 30
  4411.7  237.19  4449.2  236.08  4479.2  231.81  4499.2  234.57  4519.2  233.67
  4542.2  233.96  4559.2  233.45  4569.2  234.23  4589.2  233.80  4619.2  234.66
  4649.2  234.12  4909.2  237.30  4939.2  234.12  4969.2  233.65  5027.2  229.75
  5027.4  229.25  5031.2  229.75  5039.2  230.74  5049.2  235.46  5065.8  237.61
  5076.0  236.73  5139.5  238.15  5309.7  239.66  5415.7  242.91  5479.8  243.74
  5521.8  245.06  5536.0  246.72  5579.3  248.04  5609.8  249.20  5654.8  251.16
#Mann=7,-1,0
  4411.7   0.063       0  4542.2    0.12       0  5027.2    0.05       0
  5031.2    0.12       0  5479.8    0.07       0  5579.3    0.12       0
  5609.8    0.07       0
Bank Sta=5027.2,5031.2
Exp/Cntr=0.3,0.1

Chan Stop Cuts=-1