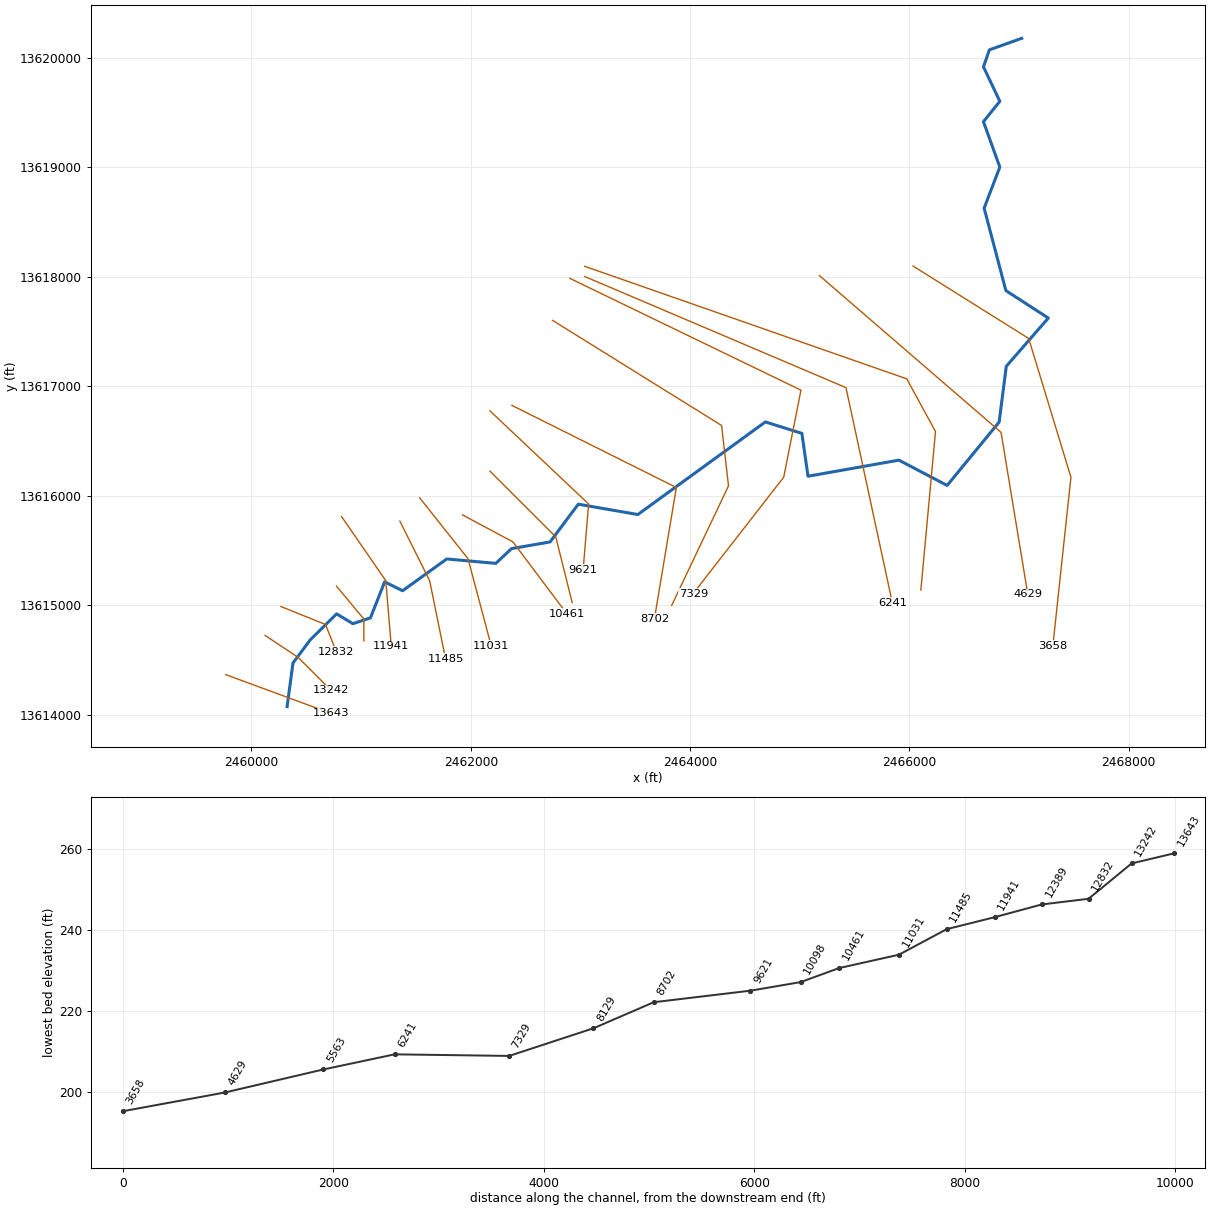
--- Stream0769.prj (project) ---

Proj Title=Stream0769 Base Level Engineering
Current Plan=p01
Default Exp/Contr=0.3,0.1
English Units
Geom File=g01
Flow File=f01
Plan File=p01
BEGIN DESCRIPTION:
Stream0769
END DESCRIPTION:

--- Stream0769.p01 (plan) ---

Plan Title=Multiple Run
Short Identifier=Multiple
Geom File=g01
Flow File=f01
Subcritical Flow
K Sum by GR= 0
Std Step Tol= 0.01
Critical Tol= 0.01
Num of Std Step Trials= 20
Max Error Tol= 0.3
Flow Tol Ratio= 0.001
Split Flow NTrial= 30
Split Flow Tol= 0.02
Split Flow Ratio= 0.02
Log Output Level= 0
Friction Slope Method= 1
Unsteady Friction Slope Method= 2
Unsteady Bridges Friction Slope Method= 1
Parabolic Critical Depth
Global Vel Dist=  1 , 1 , 1
Global Log Level= 0
CheckData=True
Encroach Param= -1, 0, 0, 0
BEGIN DESCRIPTION:
Multiple Run
END DESCRIPTION:

--- Stream0769.f01 (steady flow) ---

Flow Title=Multiple
Number of Profiles=7
Profile Names=10-year,25-year,50-year,1pct_min,100-year,1pct_plu,500-year
River Rch & RM= Stream0769,Reach-1,13643
     377     586     767     487     972    1940    1545
River Rch & RM= Stream0769,Reach-1,11941
     593     948    1264     817    1631    3254    2685
River Rch & RM= Stream0769,Reach-1,6241
    1153    1917    2627    1740    3472    6927    6011
Boundary for River Rch & Prof#=Stream0769,Reach-1,1
Up Type=0
Dn Type=3
Dn Slope=0.005
Boundary for River Rch & Prof#=Stream0769,Reach-1,2
Up Type=0
Dn Type=3
Dn Slope=0.005
Boundary for River Rch & Prof#=Stream0769,Reach-1,3
Up Type=0
Dn Type=3
Dn Slope=0.005
Boundary for River Rch & Prof#=Stream0769,Reach-1,4
Up Type=0
Dn Type=3
Dn Slope=0.005
Boundary for River Rch & Prof#=Stream0769,Reach-1,5
Up Type=0
Dn Type=3
Dn Slope=0.005
Boundary for River Rch & Prof#=Stream0769,Reach-1,6
Up Type=0
Dn Type=3
Dn Slope=0.005
Boundary for River Rch & Prof#=Stream0769,Reach-1,7
Up Type=0
Dn Type=3
Dn Slope=0.005

--- Stream0769.g01 (geometry) ---

Geom Title=Existing Conditions

River Reach=Stream0769,Reach-1
Reach XY= 30
      2460325.00     13614075.00      2460378.54     13614473.54
      2460535.77     13614684.70      2460776.64     13614921.91
      2460924.90     13614832.33      2461085.16     13614885.36
      2461214.63     13615214.05      2461378.31     13615133.02
      2461780.67     13615423.02      2462228.42     13615382.80
      2462371.59     13615517.18      2462723.50     13615578.61
      2462980.84     13615922.95      2463523.50     13615828.46
      2464687.02     13616673.80      2465020.20     13616569.38
      2465075.99     13616178.12      2465904.97     13616324.94
      2466344.93     13616094.18      2466819.17     13616672.70
      2466884.31     13617181.66      2467267.49     13617621.85
      2466880.52     13617872.56      2466682.30     13618625.08
      2466825.32     13618999.96      2466675.93     13619414.52
      2466825.59     13619600.00      2466676.20     13619914.49
      2466730.11     13620069.89      2467025.00     13620175.00

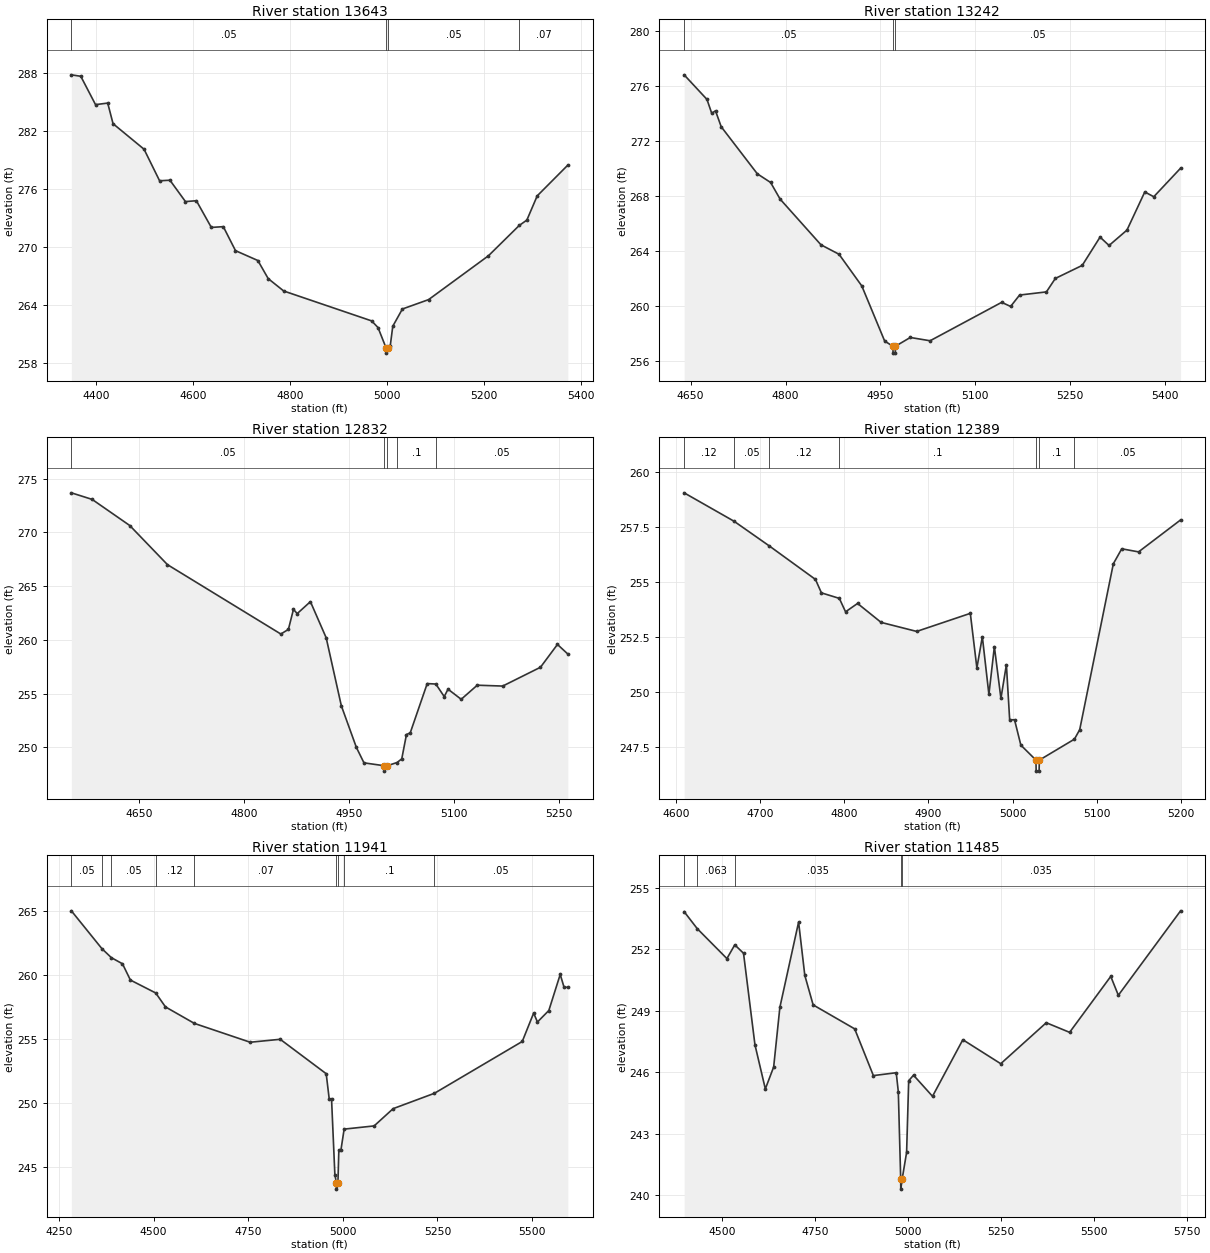
Type RM Length L Ch R = 1,13643,401,401,401
BEGIN DESCRIPTION:
XS7698
END DESCRIPTION:
XS GIS Cut Line= 2
      2459764.43     13614367.68      2460724.22     13614013.66
#Sta/Elev= 30
  4349.4  287.77  4368.8  287.62  4399.2  284.69  4424.3  284.85  4435.3  282.72
  4499.2  280.08  4531.2  276.82  4552.5  276.88  4584.5  274.67  4607.0  274.76
  4637.8  272.00  4662.5  272.08  4687.6  269.60  4733.7  268.58  4755.0  266.71
  4787.0  265.43  4968.2  262.34  4981.3  261.65  4998.2  259.51  4998.4  259.01
  5002.2  259.51  5006.4  259.73  5011.7  261.79  5031.5  263.57  5085.5  264.54
  5208.8  269.07  5272.2  272.20  5288.0  272.76  5309.3  275.26  5372.4  278.44
#Mann=4,-1,0
  4349.4    0.05       0  4998.2    0.05       0  5002.2    0.05       0
  5272.2    0.07       0
Bank Sta=4998.2,5002.2
Exp/Cntr=0.3,0.1

Type RM Length L Ch R = 1,13242,410,410,410
BEGIN DESCRIPTION:
Stream0769 20.0
END DESCRIPTION:
XS GIS Cut Line= 3
      2460125.00     13614725.00      2460425.00     13614525.00
      2460724.99     13614225.01
#Sta/Elev= 30
  4639.7  276.81  4675.8  275.02  4683.3  274.01  4689.3  274.19  4698.3  273.03
  4755.4  269.60  4776.4  268.97  4791.4  267.76  4856.0  264.43  4884.6  263.74
  4920.6  261.43  4956.7  257.42  4969.7  257.04  4970.0  256.54  4973.5  256.54
  4973.7  257.04  4997.2  257.68  5028.5  257.44  5141.7  260.24  5155.8  259.94
  5170.0  260.77  5212.4  261.00  5226.5  261.98  5269.0  262.93  5297.2  264.99
  5311.4  264.38  5339.7  265.50  5367.9  268.28  5382.1  267.93  5424.5  270.01
#Mann=3,-1,0
  4639.7    0.05       0  4969.7    0.05       0  4973.7    0.05       0
Bank Sta=4969.7,4973.7
Exp/Cntr=0.3,0.1

Type RM Length L Ch R = 1,12832,443,443,443
BEGIN DESCRIPTION:
Stream0769 19.0
END DESCRIPTION:
XS GIS Cut Line= 3
      2460267.88     13614989.17      2460675.00     13614825.00
      2460774.99     13614575.03
#Sta/Elev= 30
  4553.9  273.68  4583.5  273.07  4637.2  270.64  4691.0  267.00  4852.7  260.55
  4863.5  260.98  4870.7  262.84  4876.1  262.45  4894.9  263.56  4917.4  260.20
  4939.0  253.88  4960.5  250.00  4971.3  248.57  5000.3  248.30  5000.5  247.80
  5004.3  248.30  5018.5  248.60  5025.2  248.94  5031.9  251.20  5037.3  251.36
  5061.5  255.94  5073.8  255.90  5085.8  254.73  5091.2  255.42  5110.0  254.48
  5132.9  255.79  5169.2  255.71  5223.1  257.46  5247.3  259.58  5262.1  258.69
#Mann=5,-1,0
  4553.9    0.05       0  5000.3    0.05       0  5004.3    0.05       0
  5018.5     0.1       0  5073.8    0.05       0
Bank Sta=5000.3,5004.3
Exp/Cntr=0.3,0.1

Type RM Length L Ch R = 1,12389,448,448,448
BEGIN DESCRIPTION:
Stream0769 18.0
END DESCRIPTION:
XS GIS Cut Line= 3
      2460775.01     13615174.99      2461025.00     13614875.00
      2461025.00     13614675.00
#Sta/Elev= 30
  4609.4  259.04  4668.8  257.75  4710.7  256.63  4765.6  255.11  4772.7  254.50
  4794.0  254.25  4801.4  253.64  4815.7  254.02  4843.7  253.16  4886.0  252.75
  4949.8  253.57  4957.6  251.09  4964.1  252.51  4971.9  249.89  4978.4  252.06
  4986.2  249.71  4992.7  251.24  4996.6  248.74  5002.4  248.74  5009.9  247.59
  5027.9  246.91  5028.1  246.41  5031.6  246.41  5031.9  246.91  5073.6  247.86
  5079.9  248.29  5119.9  255.82  5129.9  256.50  5149.9  256.36  5199.9  257.81
#Mann=7,-1,0
  4609.4    0.12       0  4668.8    0.05       0  4710.7    0.12       0
  4794.0     0.1       0  5027.9    0.05       0  5031.9     0.1       0
  5073.6    0.05       0
Bank Sta=5027.9,5031.9
Exp/Cntr=0.3,0.1

Type RM Length L Ch R = 1,11941,456,456,456
BEGIN DESCRIPTION:
Stream0769 17.0
END DESCRIPTION:
XS GIS Cut Line= 3
      2460822.06     13615809.37      2461225.00     13615225.00
      2461275.00     13614625.00
#Sta/Elev= 30
  4282.8  265.01  4363.6  262.05  4388.5  261.35  4417.9  260.87  4438.8  259.60
  4505.7  258.59  4531.5  257.50  4608.0  256.21  4755.3  254.74  4834.7  254.97
  4956.2  252.28  4964.2  250.30  4970.3  250.33  4979.1  244.40  4983.2  243.76
  4983.4  243.26  4987.2  243.76  4989.6  246.31  4995.1  246.31  5003.6  247.95
  5082.9  248.20  5133.1  249.55  5242.2  250.75  5474.3  254.80  5504.4  257.02
  5514.4  256.32  5544.5  257.22  5574.6  260.04  5584.7  259.04  5594.7  259.03
#Mann=9,-1,0
  4282.8    0.05       0  4363.6    0.07       0  4388.5    0.05       0
  4505.7    0.12       0  4608.0    0.07       0  4983.2    0.05       0
  4987.2    0.07       0  5003.6     0.1       0  5242.2    0.05       0
Bank Sta=4983.2,4987.2
Exp/Cntr=0.3,0.1

Type RM Length L Ch R = 1,11485,454,454,454
BEGIN DESCRIPTION:
Stream0769 16.0
END DESCRIPTION:
XS GIS Cut Line= 3
      2461353.54     13615767.95      2461625.00     13615225.00
      2461770.16     13614510.83
#Sta/Elev= 30
  4396.9  253.84  4432.2  253.01  4512.0  251.55  4533.2  252.22  4556.7  251.81
  4587.5  247.34  4615.4  245.19  4637.8  246.26  4654.5  249.17  4704.9  253.33
  4721.6  250.73  4744.0  249.29  4855.8  248.12  4906.1  245.84  4967.6  245.98
  4973.2  245.05  4979.6  240.80  4979.8  240.30  4983.6  240.80  4995.5  242.09
  5001.1  245.59  5014.1  245.86  5065.2  244.83  5146.8  247.59  5248.8  246.42
  5371.3  248.42  5434.1  247.95  5544.8  250.68  5565.2  249.76  5732.7  253.88
#Mann=5,-1,0
  4396.9   0.035       0  4432.2   0.063       0  4533.2   0.035       0
  4979.6   0.035       0  4983.6   0.035       0
Bank Sta=4979.6,4983.6
Exp/Cntr=0.3,0.1

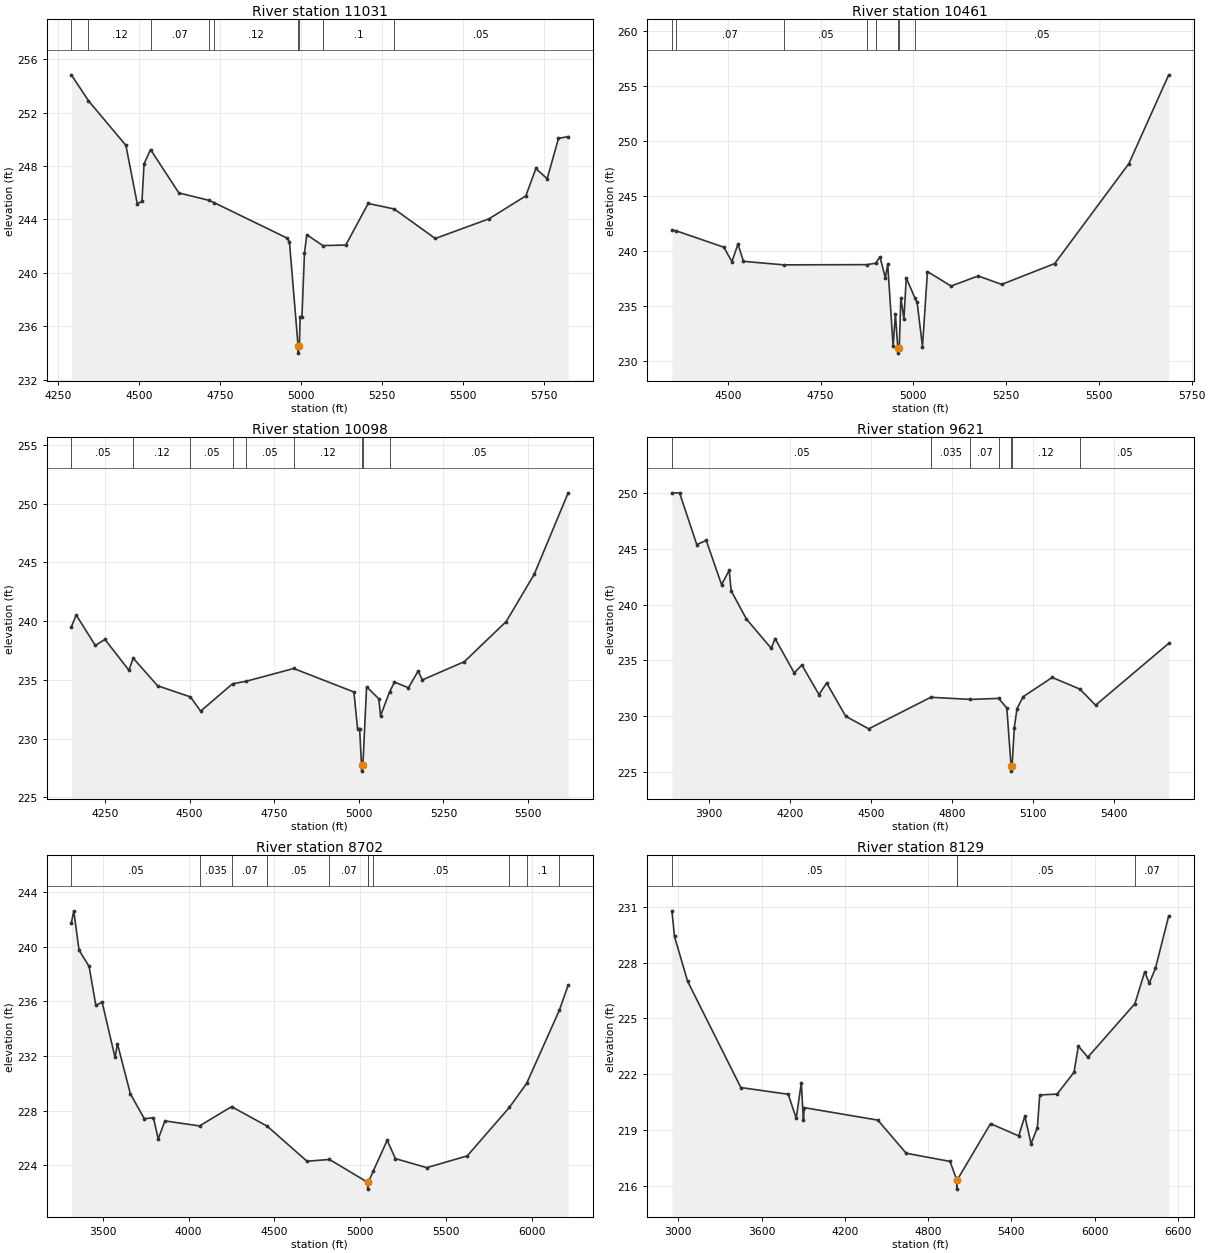
Type RM Length L Ch R = 1,11031,570,570,570
BEGIN DESCRIPTION:
Stream0769 15.0
END DESCRIPTION:
XS GIS Cut Line= 3
      2461534.44     13615980.41      2461975.00     13615425.00
      2462187.05     13614628.67
#Sta/Elev= 30
  4291.1  254.82  4343.8  252.88  4459.3  249.54  4494.5  245.16  4508.9  245.36
  4515.3  248.15  4535.3  249.23  4622.7  245.98  4715.3  245.43  4731.8  245.25
  4957.6  242.59  4964.0  242.31  4990.8  234.49  4991.1  233.99  4994.8  234.49
  4996.8  236.72  5002.6  236.72  5010.4  241.50  5017.5  242.85  5067.2  242.04
  5137.9  242.08  5207.0  245.19  5287.2  244.78  5414.0  242.57  5579.5  244.04
  5693.4  245.76  5724.4  247.81  5759.2  247.04  5794.2  250.06  5824.1  250.20
#Mann=9,-1,0
  4291.1    0.05       0  4343.8    0.12       0  4535.3    0.07       0
  4715.3     0.1       0  4731.8    0.12       0  4990.8    0.05       0
  4994.8    0.12       0  5067.2     0.1       0  5287.2    0.05       0
Bank Sta=4990.8,4994.8
Exp/Cntr=0.3,0.1

Type RM Length L Ch R = 1,10461,363,363,363
BEGIN DESCRIPTION:
Stream0769 14.0
END DESCRIPTION:
XS GIS Cut Line= 3
      2461925.02     13615824.99      2462384.09     13615579.17
      2462874.98     13614925.02
#Sta/Elev= 30
  4349.6  241.89  4361.2  241.82  4489.3  240.33  4511.3  239.01  4527.5  240.61
  4542.4  239.04  4651.2  238.72  4875.4  238.74  4898.3  238.87  4910.2  239.44
  4924.7  237.53  4931.0  238.78  4945.6  231.31  4951.8  234.23  4958.2  231.18
  4958.4  230.68  4962.2  231.18  4966.4  235.72  4974.7  233.82  4981.0  237.53
  5004.2  235.71  5010.2  235.32  5024.7  231.28  5038.1  238.11  5101.8  236.79
  5174.7  237.71  5238.1  236.94  5381.0  238.84  5580.9  247.95  5688.2  256.03
#Mann=8,-1,0
  4349.6    0.12       0  4361.2    0.07       0  4651.2    0.05       0
  4875.4    0.07       0  4898.3    0.12       0  4958.2    0.05       0
  4962.2    0.12       0  5004.2    0.05       0
Bank Sta=4958.2,4962.2
Exp/Cntr=0.3,0.1

Type RM Length L Ch R = 1,10098,477,477,477
BEGIN DESCRIPTION:
Stream0769 13.0
END DESCRIPTION:
XS GIS Cut Line= 3
      2462175.03     13616224.97      2462775.00     13615625.00
      2462925.01     13615024.96
#Sta/Elev= 30
  4151.2  239.52  4165.3  240.53  4221.9  237.93  4250.2  238.45  4320.9  235.83
  4333.9  236.85  4405.7  234.50  4502.7  233.55  4533.0  232.34  4627.1  234.67
  4665.6  234.87  4807.7  235.97  4985.5  233.97  4996.2  230.86  5002.3  230.86
  5008.0  227.73  5008.2  227.23  5012.0  227.73  5022.9  234.41  5059.0  233.39
  5064.1  231.94  5090.7  233.97  5105.3  234.81  5146.6  234.33  5174.9  235.74
  5187.8  235.00  5311.5  236.55  5435.2  239.97  5517.7  243.98  5618.2  250.93
#Mann=9,-1,0
  4151.2    0.05       0  4333.9    0.12       0  4502.7    0.05       0
  4627.1    0.12       0  4665.6    0.05       0  4807.7    0.12       0
  5008.0    0.05       0  5012.0    0.12       0  5090.7    0.05       0
Bank Sta=5008,5012
Exp/Cntr=0.3,0.1

Type RM Length L Ch R = 1,9621,919,919,919
BEGIN DESCRIPTION:
Stream0769 12.0
END DESCRIPTION:
XS GIS Cut Line= 3
      2462175.01     13616774.99      2463075.00     13615925.00
      2463025.00     13615325.01
#Sta/Elev= 30
  3762.2  249.96  3790.3  249.98  3854.2  245.36  3889.4  245.72  3946.1  241.77
  3974.4  243.06  3981.7  241.22  4037.9  238.71  4130.1  236.08  4144.3  236.96
  4215.1  233.89  4243.4  234.60  4306.9  231.95  4335.2  232.99  4406.0  230.01
  4491.0  228.89  4720.9  231.71  4866.8  231.52  4972.4  231.61  5002.6  230.74
  5018.2  225.61  5018.4  225.11  5022.2  225.61  5030.2  228.99  5040.3  230.69
  5062.8  231.76  5170.7  233.48  5273.3  232.44  5331.3  231.00  5602.2  236.53
#Mann=7,-1,0
  3762.2    0.05       0  4720.9   0.035       0  4866.8    0.07       0
  4972.4    0.12       0  5018.2    0.05       0  5022.2    0.12       0
  5273.3    0.05       0
Bank Sta=5018.2,5022.2
Exp/Cntr=0.3,0.1

Type RM Length L Ch R = 1,8702,573,573,573
BEGIN DESCRIPTION:
Stream0769 11.0
END DESCRIPTION:
XS GIS Cut Line= 3
      2462375.01     13616825.00      2463875.00     13616075.00
      2463675.00     13614874.99
#Sta/Elev= 30
  3317.4  241.73  3331.4  242.61  3362.1  239.73  3420.8  238.54  3459.9  235.69
  3496.3  235.94  3571.7  231.89  3585.7  232.89  3661.2  229.22  3742.2  227.41
  3795.4  227.48  3823.3  225.93  3862.4  227.25  4063.8  226.88  4250.1  228.29
  4458.3  226.86  4689.8  224.30  4820.4  224.43  5043.1  222.76  5043.4  222.26
  5047.1  222.76  5075.3  223.57  5156.6  225.83  5204.8  224.49  5387.3  223.83
  5623.0  224.69  5868.7  228.24  5969.0  229.99  6159.2  235.33  6211.0  237.18
#Mann=11,-1,0
  3317.4    0.05       0  4063.8   0.035       0  4250.1    0.07       0
  4458.3    0.05       0  4820.4    0.07       0  5043.1    0.05       0
  5047.1    0.07       0  5075.3    0.05       0  5868.7    0.07       0
  5969.0     0.1       0  6159.2    0.05       0
Bank Sta=5043.1,5047.1
Exp/Cntr=0.3,0.1

Type RM Length L Ch R = 1,8129,800,800,800
BEGIN DESCRIPTION:
XS7697
END DESCRIPTION:
XS GIS Cut Line= 4
      2462745.94     13617600.95      2464287.86     13616641.19
      2464350.80     13616090.51      2463832.30     13614998.54
#Sta/Elev= 30
  2954.2  230.78  2972.8  229.40  3067.3  226.99  3450.9  221.28  3792.0  220.92
  3849.8  219.63  3886.4  221.53  3901.7  219.51  3907.6  220.20  4437.6  219.53
  4641.8  217.75  4957.8  217.31  5006.1  216.32  5006.4  215.82  5010.1  216.32
  5249.7  219.34  5452.6  218.68  5496.8  219.75  5541.5  218.26  5587.0  219.12
  5604.2  220.88  5729.3  220.93  5851.1  222.10  5882.4  223.51  5950.6  222.91
  6290.0  225.79  6360.3  227.50  6393.5  226.89  6437.8  227.69  6533.5  230.51
#Mann=4,-1,0
  2954.2    0.05       0  5006.1    0.05       0  5010.1    0.05       0
  6290.0    0.07       0
Bank Sta=5006.1,5010.1
Exp/Cntr=0.3,0.1

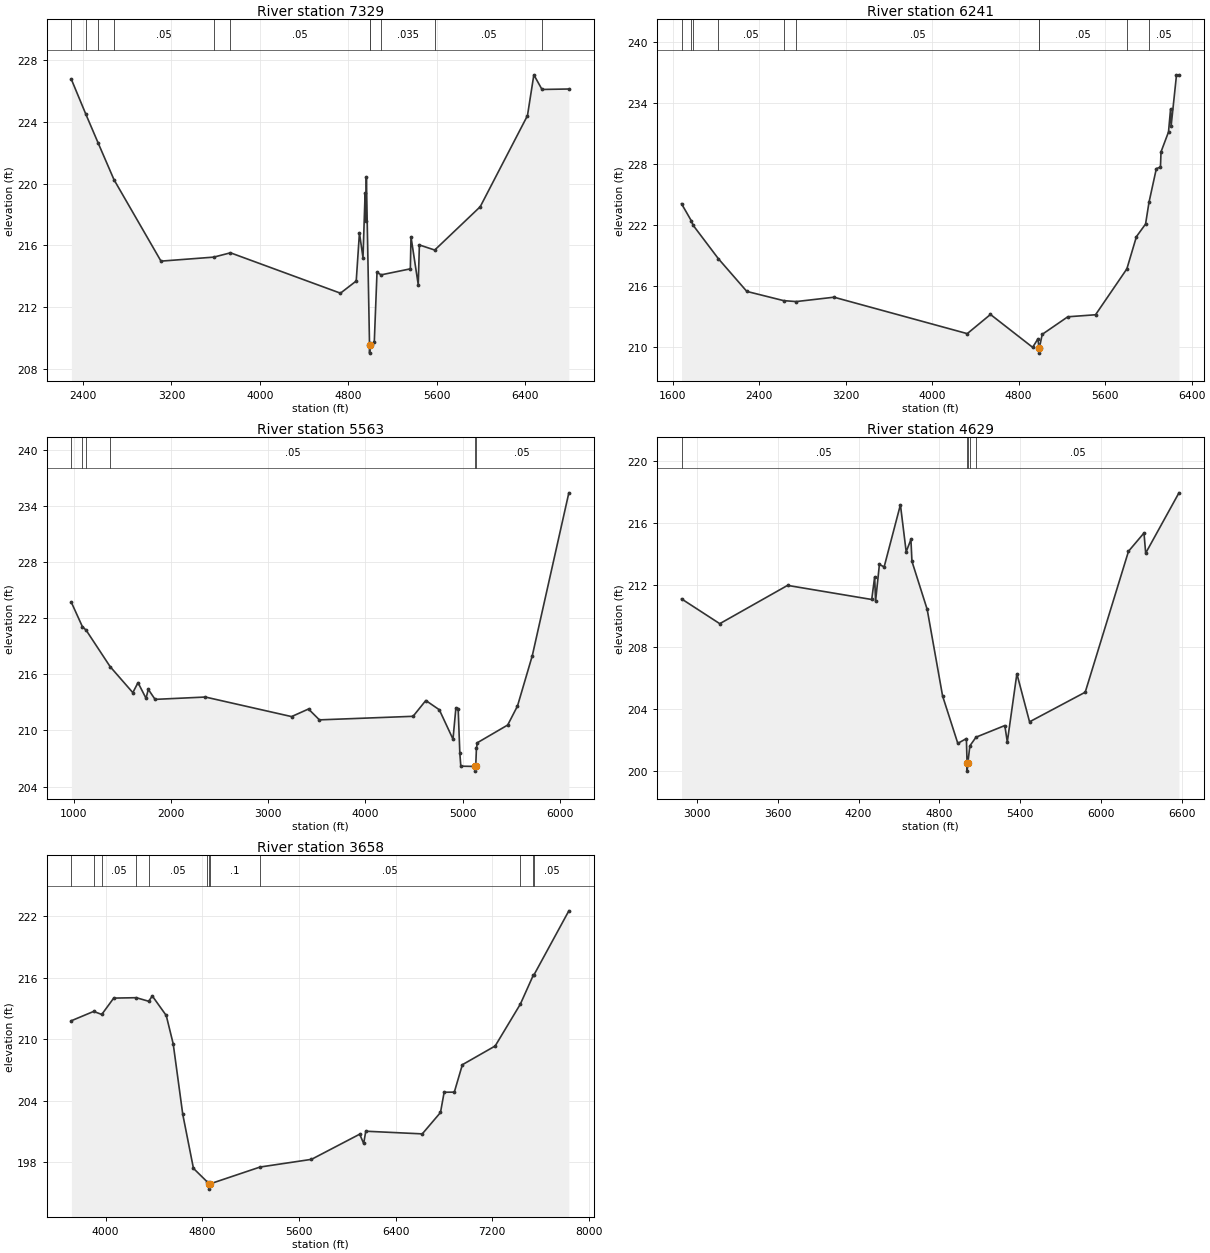
Type RM Length L Ch R = 1,7329,1088,1088,1088
BEGIN DESCRIPTION:
XS7696
END DESCRIPTION:
XS GIS Cut Line= 4
      2462903.78     13617984.10      2465011.61     13616963.73
      2464854.27     13616169.18      2464028.27     13615107.18
#Sta/Elev= 30
  2296.1  226.76  2427.4  224.49  2538.2  222.63  2681.4  220.25  3105.9  214.97
  3582.9  215.23  3734.2  215.51  4728.4  212.89  4871.1  213.68  4900.1  216.80
  4932.3  215.20  4951.3  219.37  4956.4  217.57  4962.8  220.41  4991.4  209.50
  4991.7  209.00  4995.4  209.50  5034.2  209.69  5058.9  214.24  5096.5  214.08
  5360.4  214.47  5366.2  216.55  5431.8  213.44  5442.0  216.02  5580.7  215.69
  5992.0  218.50  6419.1  224.41  6477.0  227.06  6550.6  226.11  6793.3  226.14
#Mann=11,-1,0
  2296.1    0.07       0  2427.4    0.05       0  2538.2    0.07       0
  2681.4    0.05       0  3582.9    0.07       0  3734.2    0.05       0
  4991.4    0.05       0  4995.4    0.05       0  5096.5   0.035       0
  5580.7    0.05       0  6550.6     0.1       0
Bank Sta=4991.4,4995.4
Exp/Cntr=0.3,0.1

Type RM Length L Ch R = 1,6241,678,678,678
BEGIN DESCRIPTION:
XS7695
END DESCRIPTION:
XS GIS Cut Line= 3
      2463039.15     13618001.04      2465422.32     13616986.73
      2465845.50     13615020.60
#Sta/Elev= 30
  1681.6  224.11  1772.2  222.43  1788.1  222.00  2022.7  218.69  2285.7  215.47
  2627.0  214.56  2742.7  214.47  3092.0  214.90  4324.6  211.31  4539.4  213.20
  4929.6  209.96  4979.2  210.81  4987.4  209.89  4987.7  209.39  4991.4  209.89
  5018.0  211.24  5254.5  212.97  5511.1  213.17  5800.9  217.69  5889.6  220.87
  5974.0  222.11  6005.9  224.26  6073.7  227.57  6111.8  227.72  6116.9  229.22
  6186.2  231.18  6205.4  233.45  6210.5  231.78  6259.8  236.76  6282.8  236.81
#Mann=10,-1,0
  1681.6    0.07       0  1772.2    0.05       0  1788.1    0.07       0
  2022.7    0.05       0  2627.0    0.07       0  2742.7    0.05       0
  4987.4    0.05       0  4991.4    0.05       0  5800.9    0.07       0
  6005.9    0.05       0
Bank Sta=4987.4,4991.4
Exp/Cntr=0.3,0.1

Type RM Length L Ch R = 1,5563,934,934,934
BEGIN DESCRIPTION:
XS7694
END DESCRIPTION:
XS GIS Cut Line= 4
      2463039.11     13618094.13      2465976.57     13617066.94
      2466238.83     13616586.12      2466105.17     13615139.36
#Sta/Elev= 30
   977.8  223.68  1090.4  221.10  1129.6  220.71  1375.8  216.82  1609.1  214.04
  1662.1  215.11  1744.6  213.44  1768.0  214.39  1837.7  213.32  2354.8  213.57
  3240.5  211.48  3414.6  212.29  3526.5  211.13  4489.2  211.51  4620.2  213.20
  4759.0  212.21  4899.6  209.07  4929.7  212.43  4952.8  212.32  4969.9  207.58
  4979.9  206.18  5127.9  206.15  5128.3  205.65  5133.2  206.15  5140.6  208.11
  5150.7  208.69  5462.0  210.58  5562.4  212.61  5714.9  218.00  6090.3  235.40
#Mann=6,-1,0
   977.8    0.07       0  1090.4    0.05       0  1129.6    0.07       0
  1375.8    0.05       0  5127.9    0.05       0  5133.2    0.05       0
Bank Sta=5127.9,5133.2
Exp/Cntr=0.3,0.1

Type RM Length L Ch R = 1,4629,971,971,971
BEGIN DESCRIPTION:
XS7693
END DESCRIPTION:
XS GIS Cut Line= 3
      2465180.10     13618009.47      2466836.71     13616578.26
      2467080.59     13615099.26
#Sta/Elev= 30
  2887.4  211.08  3171.0  209.48  3673.6  211.95  4297.6  211.04  4319.5  212.50
  4326.1  210.93  4354.6  213.30  4389.7  213.14  4510.4  217.15  4553.1  214.12
  4588.3  214.91  4595.9  213.50  4708.9  210.40  4823.0  204.82  4936.0  201.76
  4999.6  202.07  5004.6  200.47  5005.0  199.97  5009.9  200.47  5025.4  201.60
  5071.0  202.16  5284.5  202.91  5302.9  201.85  5373.9  206.25  5467.9  203.15
  5880.6  205.06  6201.5  214.15  6316.4  215.33  6328.9  214.03  6575.6  217.92
#Mann=5,-1,0
  2887.4    0.05       0  5004.6    0.05       0  5009.9    0.05       0
  5025.4    0.12       0  5071.0    0.05       0
Bank Sta=5004.6,5009.9
Exp/Cntr=0.3,0.1

Type RM Length L Ch R = 1,3658,0,0,0
BEGIN DESCRIPTION:
XS7692
END DESCRIPTION:
XS GIS Cut Line= 4
      2466034.28     13618096.56      2467088.45     13617435.74
      2467473.93     13616169.18      2467308.87     13614628.69
#Sta/Elev= 30
  3717.2  211.80  3901.7  212.71  3968.2  212.41  4067.3  214.01  4254.1  214.05
  4356.9  213.70  4386.7  214.22  4502.2  212.31  4559.9  209.53  4638.9  202.65
  4727.3  197.37  4838.6  196.08  4855.4  195.84  4855.8  195.34  4860.8  195.84
  5279.0  197.50  5704.3  198.25  6103.4  200.71  6136.3  199.80  6153.8  201.00
  6621.4  200.74  6772.2  202.83  6802.4  204.81  6886.6  204.82  6953.3  207.50
  7224.8  209.33  7433.1  213.42  7540.1  216.24  7546.9  216.30  7834.6  222.54
#Mann=12,-1,0
  3717.2    0.05       0  3901.7    0.07       0  3968.2    0.05       0
  4254.1    0.07       0  4356.9    0.05       0  4838.6     0.1       0
  4855.4    0.05       0  4860.8     0.1       0  5279.0    0.05       0
  7433.1    0.07       0  7540.1   0.035       0  7546.9    0.05       0
Bank Sta=4855.4,4860.8
Exp/Cntr=0.3,0.1

Chan Stop Cuts=-1