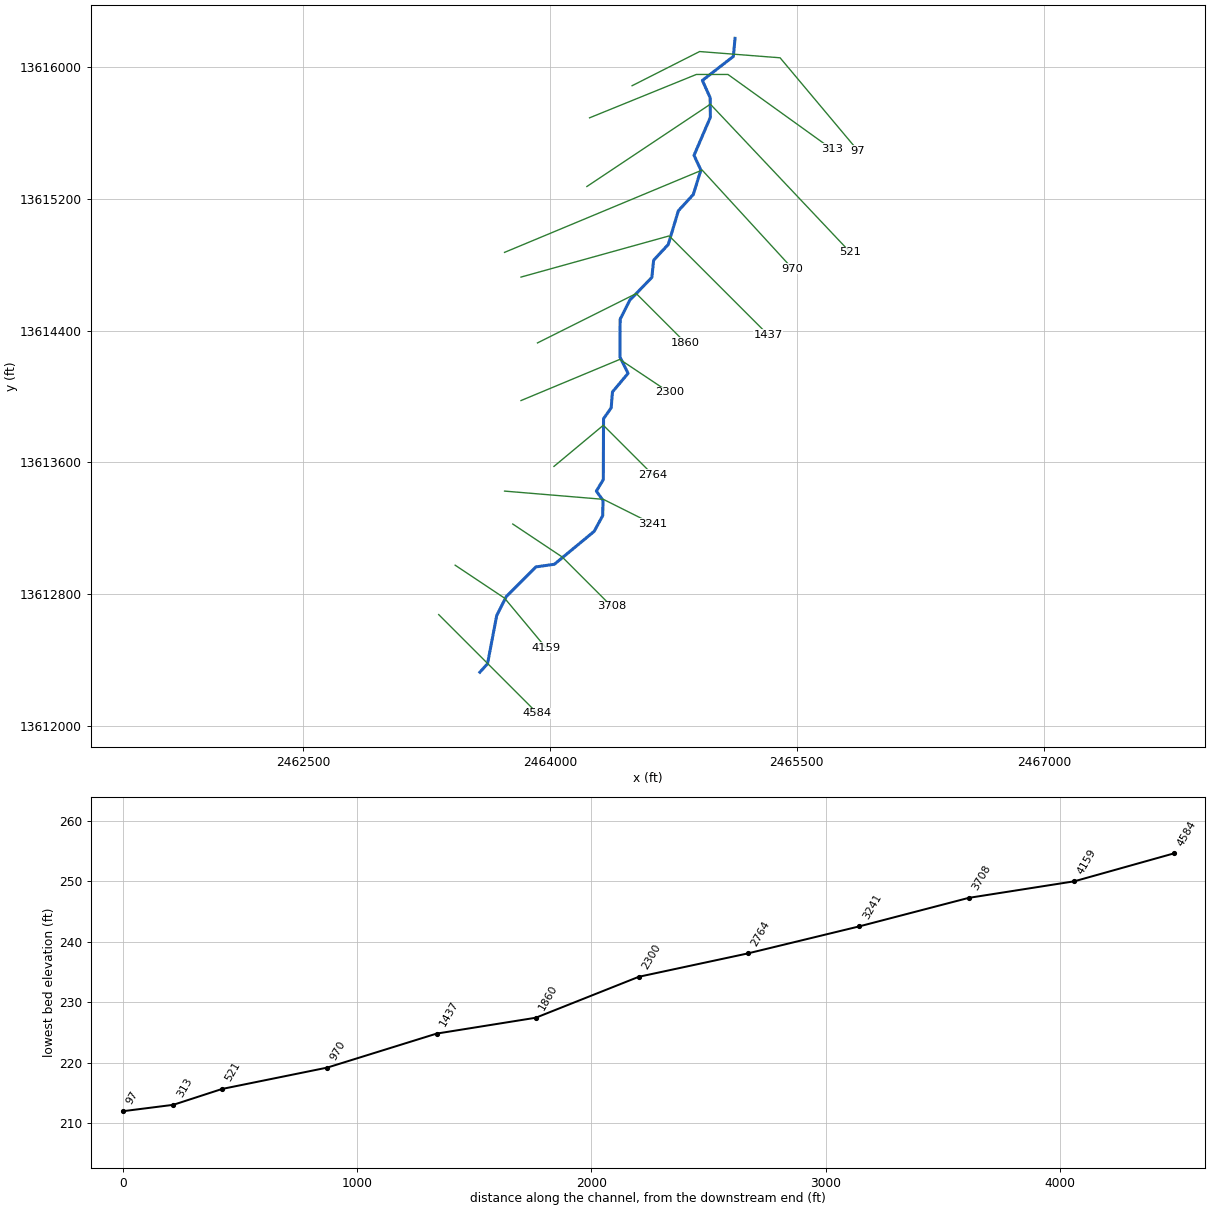
--- Stream0770.prj (project) ---

Proj Title=Stream0770 Base Level Engineering
Current Plan=p01
Default Exp/Contr=0.3,0.1
English Units
Geom File=g01
Flow File=f01
Plan File=p01
BEGIN DESCRIPTION:
Stream0770
END DESCRIPTION:

--- Stream0770.p01 (plan) ---

Plan Title=Multiple Run
Short Identifier=Multiple
Geom File=g01
Flow File=f01
Subcritical Flow
K Sum by GR= 0
Std Step Tol= 0.01
Critical Tol= 0.01
Num of Std Step Trials= 20
Max Error Tol= 0.3
Flow Tol Ratio= 0.001
Split Flow NTrial= 30
Split Flow Tol= 0.02
Split Flow Ratio= 0.02
Log Output Level= 0
Friction Slope Method= 1
Unsteady Friction Slope Method= 2
Unsteady Bridges Friction Slope Method= 1
Parabolic Critical Depth
Global Vel Dist=  1 , 1 , 1
Global Log Level= 0
CheckData=True
Encroach Param= -1, 0, 0, 0
BEGIN DESCRIPTION:
Multiple Run
END DESCRIPTION:

--- Stream0770.f01 (steady flow) ---

Flow Title=Multiple
Number of Profiles=7
Profile Names=10-year,25-year,50-year,1pct_min,100-year,1pct_plu,500-year
River Rch & RM= Stream0770,Reach-1,4584
     493     789    1055     685    1367    2727    2269
River Rch & RM= Stream0770,Reach-1,97
    1153    1917    2627    1740    3472    6927    6011
Boundary for River Rch & Prof#=Stream0770,Reach-1,1
Up Type=0
Dn Type=3
Dn Slope=0.005
Boundary for River Rch & Prof#=Stream0770,Reach-1,2
Up Type=0
Dn Type=3
Dn Slope=0.005
Boundary for River Rch & Prof#=Stream0770,Reach-1,3
Up Type=0
Dn Type=3
Dn Slope=0.005
Boundary for River Rch & Prof#=Stream0770,Reach-1,4
Up Type=0
Dn Type=3
Dn Slope=0.005
Boundary for River Rch & Prof#=Stream0770,Reach-1,5
Up Type=0
Dn Type=3
Dn Slope=0.005
Boundary for River Rch & Prof#=Stream0770,Reach-1,6
Up Type=0
Dn Type=3
Dn Slope=0.005
Boundary for River Rch & Prof#=Stream0770,Reach-1,7
Up Type=0
Dn Type=3
Dn Slope=0.005

--- Stream0770.g01 (geometry) ---

Geom Title=Existing Conditions

River Reach=Stream0770,Reach-1
Reach XY= 30
      2463575.00     13612325.00      2463621.61     13612376.40
      2463677.25     13612669.07      2463735.76     13612784.68
      2463915.21     13612964.48      2464027.43     13612980.52
      2464269.41     13613180.61      2464321.34     13613276.56
      2464322.64     13613369.11      2464282.56     13613425.00
      2464324.82     13613494.98      2464326.22     13613864.50
      2464372.64     13613930.98      2464380.54     13614027.42
      2464475.04     13614140.34      2464425.54     13614240.21
      2464427.24     13614469.07      2464485.76     13614584.68
      2464619.48     13614722.57      2464630.54     13614827.42
      2464719.15     13614922.71      2464780.54     13615127.42
      2464871.38     13615226.50      2464917.41     13615375.01
      2464875.81     13615464.29      2464974.95     13615695.04
      2464973.77     13615814.50      2464926.54     13615919.15
      2465114.58     13616065.16      2465125.00     13616175.00

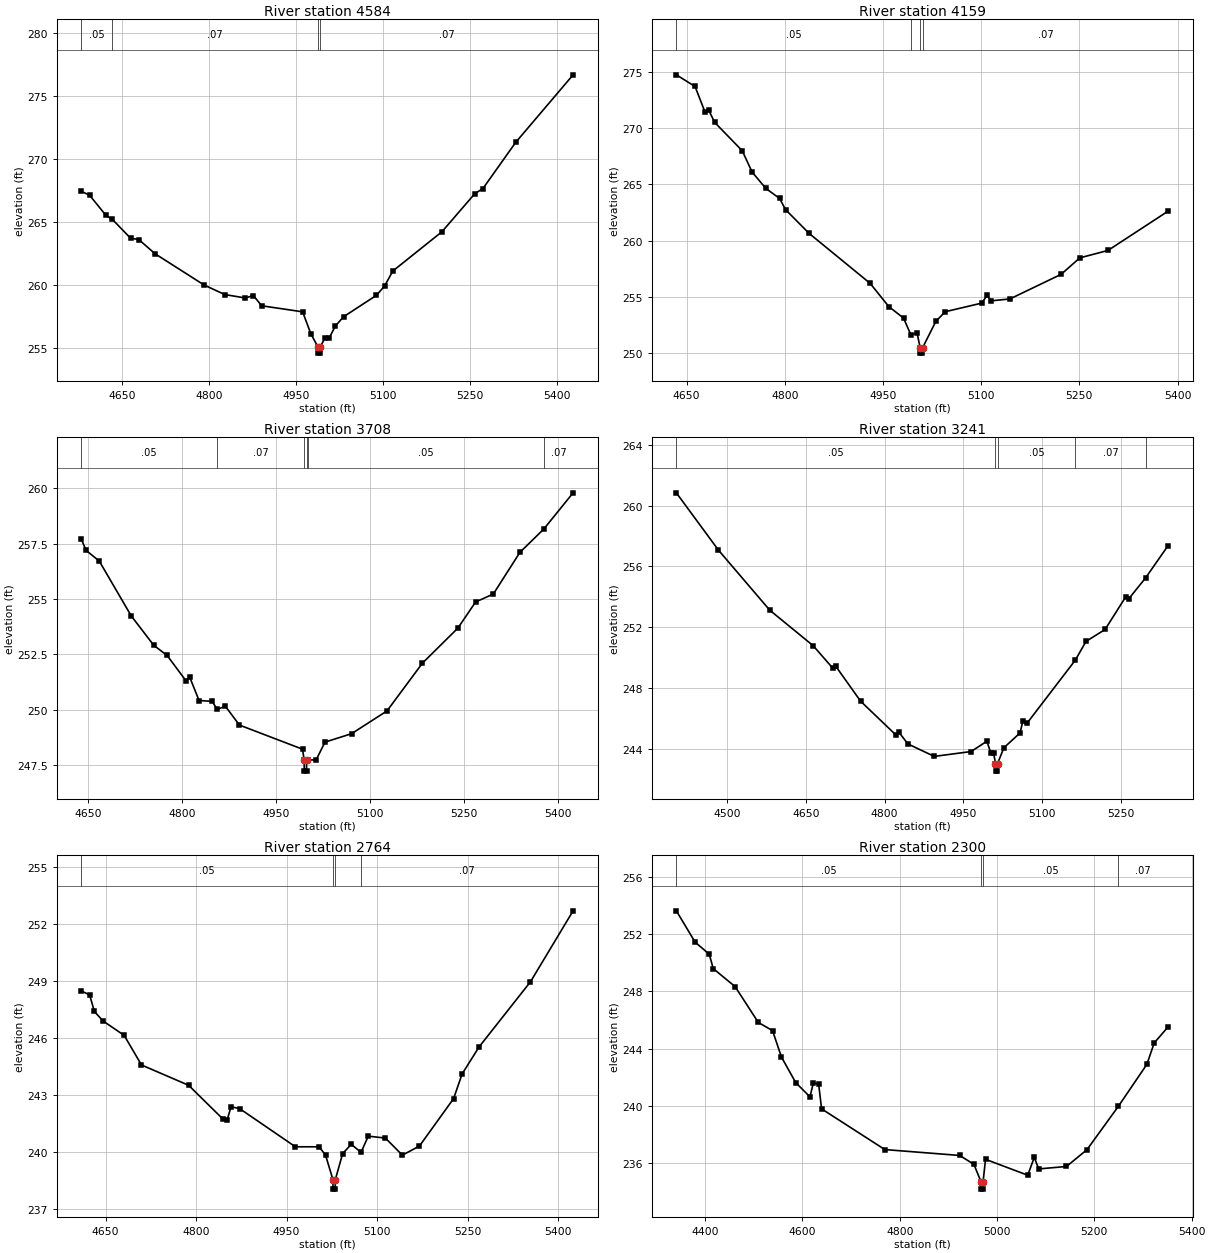
Type RM Length L Ch R = 1,4584,425,425,425
BEGIN DESCRIPTION:
Stream0770 10.0
END DESCRIPTION:
XS GIS Cut Line= 3
      2463325.03     13612674.97      2463625.00     13612375.00
      2463925.01     13612074.99
#Sta/Elev= 30
  4579.9  267.43  4594.0  267.12  4622.3  265.52  4633.4  265.20  4664.7  263.71
  4678.9  263.60  4707.1  262.47  4792.0  259.98  4827.4  259.23  4862.7  258.96
  4876.8  259.15  4891.0  258.34  4961.7  257.86  4975.8  256.12  4988.0  255.08
  4988.2  254.58  4991.7  254.58  4992.0  255.08  5000.6  255.80  5007.7  255.80
  5018.3  256.74  5032.4  257.47  5089.0  259.17  5103.1  259.91  5117.3  261.10
  5202.1  264.22  5258.7  267.24  5272.8  267.65  5329.4  271.32  5428.4  276.68
#Mann=4,-1,0
  4579.9    0.05       0  4633.4    0.07       0  4988.0    0.05       0
  4992.0    0.07       0
Bank Sta=4988,4992
Exp/Cntr=0.3,0.1

Type RM Length L Ch R = 1,4159,451,451,451
BEGIN DESCRIPTION:
Stream0770 9.0
END DESCRIPTION:
XS GIS Cut Line= 3
      2463424.98     13612975.01      2463725.00     13612775.00
      2463975.00     13612475.00
#Sta/Elev= 30
  4634.4  274.77  4663.0  273.73  4678.0  271.48  4684.0  271.60  4693.0  270.53
  4735.1  268.00  4750.1  266.11  4771.1  264.65  4792.2  263.75  4801.2  262.76
  4837.2  260.64  4930.4  256.19  4958.9  254.12  4981.5  253.09  4992.5  251.62
  5002.1  251.78  5006.7  250.47  5006.9  249.97  5010.4  249.97  5010.7  250.47
  5030.8  252.80  5045.1  253.66  5101.1  254.43  5108.9  255.12  5115.4  254.63
  5144.0  254.80  5222.1  256.99  5250.8  258.46  5293.7  259.12  5385.5  262.62
#Mann=4,-1,0
  4634.4    0.05       0  4992.5    0.07       0  5006.7    0.05       0
  5010.7    0.07       0
Bank Sta=5006.7,5010.7
Exp/Cntr=0.3,0.1

Type RM Length L Ch R = 1,3708,467,467,467
BEGIN DESCRIPTION:
Stream0770 8.0
END DESCRIPTION:
XS GIS Cut Line= 3
      2463775.03     13613224.98      2464075.00     13613025.00
      2464375.01     13612724.99
#Sta/Elev= 30
  4639.2  257.70  4646.7  257.20  4667.7  256.72  4718.8  254.24  4754.8  252.91
  4775.9  252.46  4805.9  251.32  4811.9  251.49  4827.0  250.42  4848.0  250.38
  4855.9  250.02  4869.0  250.16  4891.5  249.31  4992.2  248.22  4994.7  247.73
  4995.0  247.23  4998.5  247.23  4998.7  247.73  5000.9  247.73  5013.9  247.74
  5028.0  248.54  5070.4  248.92  5127.0  249.95  5183.6  252.11  5240.1  253.69
  5268.4  254.87  5296.7  255.23  5339.1  257.11  5377.4  258.17  5424.0  259.80
#Mann=6,-1,0
  4639.2    0.05       0  4855.9    0.07       0  4994.7    0.05       0
  4998.7    0.07       0  5000.9    0.05       0  5377.4    0.07       0
Bank Sta=4994.7,4998.7
Exp/Cntr=0.3,0.1

Type RM Length L Ch R = 1,3241,477,477,477
BEGIN DESCRIPTION:
Stream0770 7.0
END DESCRIPTION:
XS GIS Cut Line= 3
      2463725.04     13613425.00      2464325.00     13613375.00
      2464624.96     13613225.02
#Sta/Elev= 30
  4402.9  260.85  4483.1  257.08  4581.0  253.12  4663.8  250.78  4701.4  249.29
  4706.4  249.45  4754.1  247.13  4821.8  244.89  4826.8  245.10  4844.4  244.31
  4894.6  243.49  4964.8  243.81  4994.9  244.49  5002.4  243.72  5007.7  243.72
  5011.3  243.02  5011.6  242.52  5015.1  242.52  5015.3  243.02  5027.3  244.06
  5058.0  245.03  5063.6  245.83  5072.0  245.70  5163.5  249.83  5183.8  251.06
  5220.2  251.85  5259.3  253.98  5264.9  253.85  5297.3  255.24  5340.3  257.37
#Mann=5,-1,0
  4402.9    0.05       0  5011.3    0.05       0  5015.3    0.05       0
  5163.5    0.07       0  5297.3    0.05       0
Bank Sta=5011.3,5015.3
Exp/Cntr=0.3,0.1

Type RM Length L Ch R = 1,2764,464,464,464
BEGIN DESCRIPTION:
Stream0770 6.0
END DESCRIPTION:
XS GIS Cut Line= 3
      2464025.00     13613575.00      2464325.00     13613825.00
      2464625.01     13613524.99
#Sta/Elev= 30
  4610.0  248.48  4623.7  248.27  4631.5  247.40  4645.8  246.90  4680.9  246.14
  4709.6  244.58  4787.7  243.51  4844.3  241.74  4851.5  241.68  4858.0  242.38
  4872.3  242.28  4964.7  240.27  5004.1  240.27  5014.7  239.82  5026.8  238.54
  5027.1  238.04  5030.6  238.04  5030.8  238.54  5042.9  239.91  5057.1  240.40
  5073.4  239.98  5085.4  240.83  5113.7  240.73  5141.9  239.83  5170.2  240.31
  5226.8  242.81  5240.9  244.11  5269.2  245.54  5354.1  248.96  5424.8  252.70
#Mann=4,-1,0
  4610.0    0.05       0  5026.8    0.05       0  5030.8    0.05       0
  5073.4    0.07       0
Bank Sta=5026.8,5030.8
Exp/Cntr=0.3,0.1

Type RM Length L Ch R = 1,2300,440,440,440
BEGIN DESCRIPTION:
Stream0770 5.0
END DESCRIPTION:
XS GIS Cut Line= 3
      2463825.00     13613975.00      2464425.00     13614225.00
      2464724.96     13614025.03
#Sta/Elev= 30
  4341.0  253.61  4379.5  251.43  4408.7  250.58  4416.8  249.58  4461.8  248.32
  4509.5  245.82  4538.7  245.25  4557.1  243.40  4586.4  241.62  4615.6  240.63
  4622.7  241.62  4633.5  241.50  4639.5  239.79  4769.5  236.95  4923.3  236.54
  4952.5  235.92  4967.3  234.69  4967.6  234.19  4971.1  234.19  4971.3  234.69
  4976.4  236.27  5063.1  235.16  5076.6  236.41  5085.6  235.60  5142.7  235.77
  5184.8  236.94  5249.4  239.97  5308.0  242.90  5323.0  244.39  5351.5  245.51
#Mann=4,-1,0
  4341.0    0.05       0  4967.3    0.05       0  4971.3    0.05       0
  5249.4    0.07       0
Bank Sta=4967.3,4971.3
Exp/Cntr=0.3,0.1

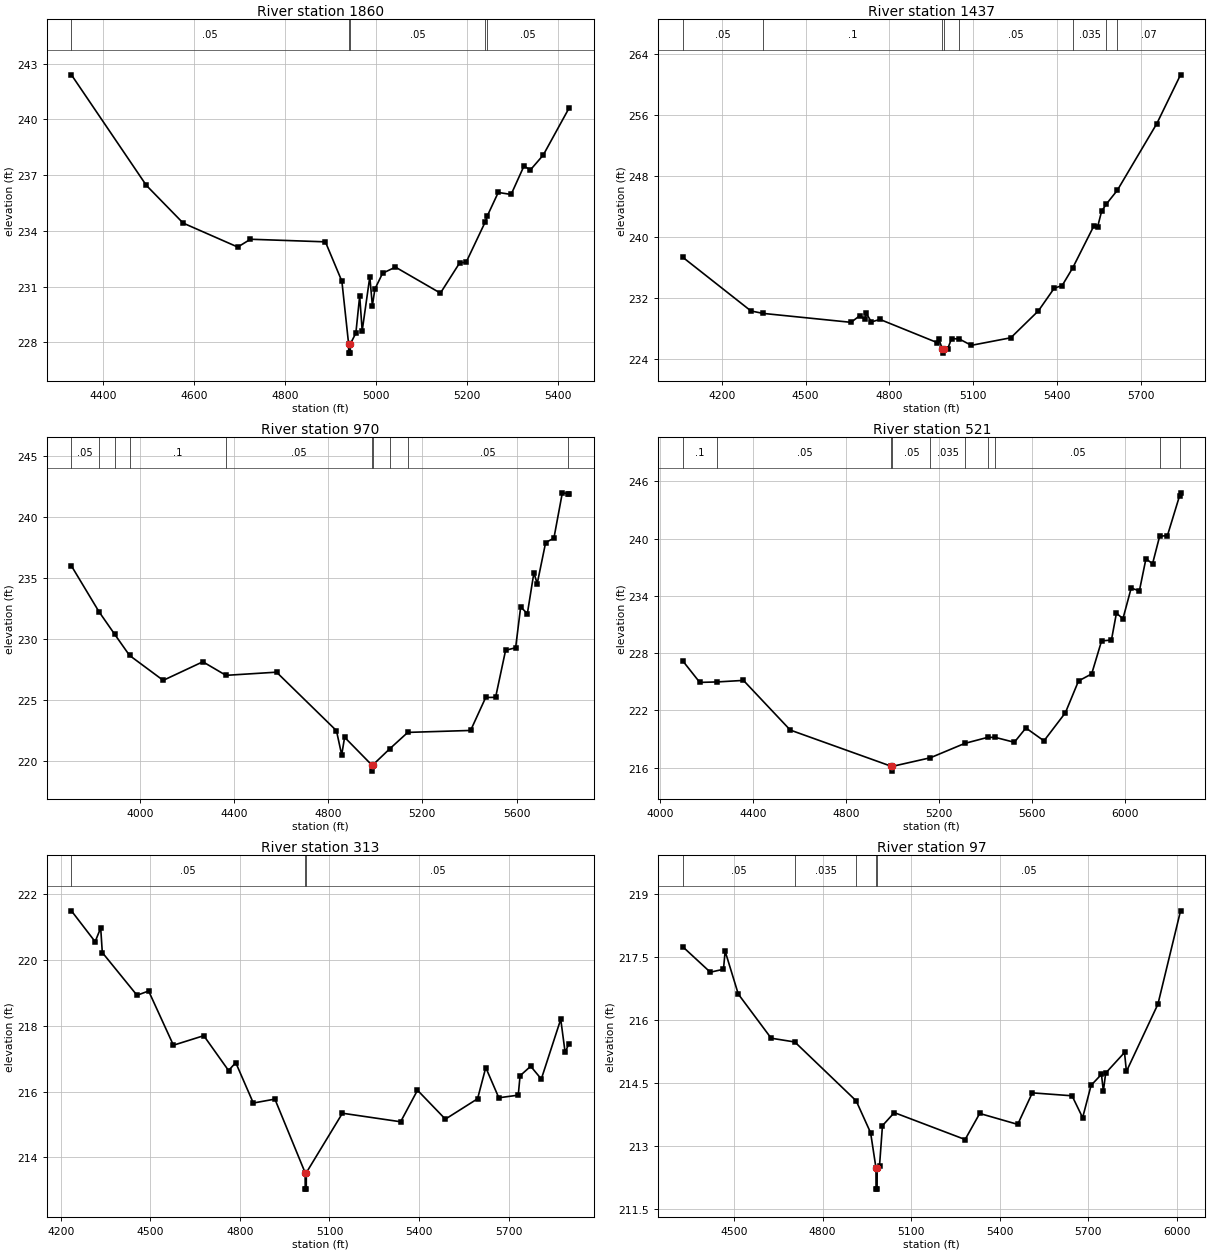
Type RM Length L Ch R = 1,1860,423,423,423
BEGIN DESCRIPTION:
Stream0770 4.0
END DESCRIPTION:
XS GIS Cut Line= 3
      2463925.02     13614325.01      2464525.00     13614625.00
      2464825.03     13614324.97
#Sta/Elev= 30
  4329.9  242.40  4494.8  236.45  4575.8  234.42  4696.0  233.13  4724.0  233.55
  4888.9  233.41  4925.2  231.29  4940.0  227.92  4940.2  227.42  4943.7  227.42
  4944.0  227.92  4956.0  228.50  4964.4  230.50  4969.9  228.62  4986.7  231.53
  4992.3  229.98  4997.9  230.87  5014.8  231.72  5043.1  232.05  5142.1  230.65
  5184.5  232.28  5198.7  232.31  5241.1  234.50  5245.2  234.80  5269.4  236.07
  5297.7  235.96  5326.0  237.49  5340.1  237.28  5368.4  238.08  5425.0  240.60
#Mann=5,-1,0
  4329.9    0.05       0  4940.0    0.05       0  4944.0    0.05       0
  5241.1   0.035       0  5245.2    0.05       0
Bank Sta=4940,4944
Exp/Cntr=0.3,0.1

Type RM Length L Ch R = 1,1437,467,467,467
BEGIN DESCRIPTION:
Stream0770 3.0
END DESCRIPTION:
XS GIS Cut Line= 3
      2463824.96     13614724.99      2464725.00     13614975.00
      2465324.97     13614375.03
#Sta/Elev= 30
  4060.8  237.32  4304.2  230.32  4347.3  230.00  4662.8  228.83  4693.9  229.69
  4712.1  229.23  4717.3  230.03  4735.5  228.88  4766.6  229.21  4972.6  226.16
  4977.8  226.60  4990.3  225.30  4990.6  224.80  4994.3  225.30  5009.1  225.37
  5023.2  226.71  5051.1  226.64  5093.9  225.82  5235.3  226.81  5334.3  230.34
  5390.9  233.30  5419.2  233.64  5457.3  235.97  5532.3  241.41  5546.5  241.35
  5560.6  243.37  5577.4  244.30  5616.9  246.11  5758.6  254.85  5843.4  261.22
#Mann=8,-1,0
  4060.8    0.05       0  4347.3     0.1       0  4990.3    0.05       0
  4994.3     0.1       0  5051.1    0.05       0  5457.3   0.035       0
  5577.4    0.05       0  5616.9    0.07       0
Bank Sta=4990.3,4994.3
Exp/Cntr=0.3,0.1

Type RM Length L Ch R = 1,970,449,449,449
BEGIN DESCRIPTION:
Stream0770 2.0
END DESCRIPTION:
XS GIS Cut Line= 3
      2463724.98     13614874.99      2464925.00     13615375.00
      2465475.02     13614774.97
#Sta/Elev= 30
  3708.8  235.98  3825.9  232.23  3891.9  230.40  3955.8  228.65  4098.8  226.61
  4267.3  228.13  4365.5  227.02  4580.4  227.28  4834.9  222.49  4857.2  220.51
  4869.6  221.95  4985.2  219.68  4985.4  219.18  4989.2  219.68  5061.5  221.01
  5138.0  222.35  5405.0  222.51  5469.1  225.21  5511.1  225.22  5553.6  229.07
  5596.2  229.28  5617.7  232.62  5646.1  232.07  5673.8  235.41  5688.0  234.53
  5723.8  237.89  5758.9  238.25  5794.7  241.96  5819.6  241.89  5822.8  241.89
#Mann=10,-1,0
  3708.8    0.05       0  3825.9    0.07       0  3891.9    0.05       0
  3955.8     0.1       0  4365.5    0.05       0  4985.2    0.05       0
  4989.2    0.05       0  5061.5     0.1       0  5138.0    0.05       0
  5819.6   0.035       0
Bank Sta=4985.2,4989.2
Exp/Cntr=0.3,0.1

Type RM Length L Ch R = 1,521,208,208,208
BEGIN DESCRIPTION:
Stream0770 1.0
END DESCRIPTION:
XS GIS Cut Line= 3
      2464225.02     13615275.02      2464975.00     13615775.00
      2465825.00     13614875.00
#Sta/Elev= 30
  4098.0  227.16  4170.1  224.94  4245.7  224.99  4357.9  225.15  4559.2  219.95
  4994.4  216.15  4994.6  215.65  4998.4  216.15  5161.8  217.05  5309.1  218.55
  5408.8  219.19  5441.1  219.18  5522.7  218.67  5572.4  220.17  5650.1  218.82
  5742.1  221.76  5798.6  225.09  5855.2  225.83  5897.7  229.28  5940.2  229.38
  5961.6  232.19  5989.7  231.61  6025.1  234.82  6060.3  234.52  6088.6  237.89
  6116.9  237.36  6147.5  240.25  6180.9  240.31  6232.9  244.46  6237.3  244.79
#Mann=10,-1,0
  4098.0     0.1       0  4245.7    0.05       0  4994.4    0.05       0
  4998.4    0.05       0  5161.8   0.035       0  5309.1     0.1       0
  5408.8   0.035       0  5441.1    0.05       0  6147.5   0.035       0
  6232.9    0.05       0
Bank Sta=4994.4,4998.4
Exp/Cntr=0.3,0.1

Type RM Length L Ch R = 1,313,216,216,216
BEGIN DESCRIPTION:
E21345
END DESCRIPTION:
XS GIS Cut Line= 4
      2464241.34     13615692.18      2464889.58     13615955.53
      2465082.02     13615955.53      2465711.27     13615503.18
#Sta/Elev= 30
  4235.4  221.50  4314.9  220.56  4333.5  220.98  4338.9  220.23  4455.2  218.93
  4494.1  219.06  4577.2  217.41  4678.9  217.70  4761.9  216.64  4786.0  216.88
  4844.9  215.65  4917.2  215.77  5018.5  213.53  5018.8  213.03  5022.3  213.03
  5022.5  213.53  5143.5  215.34  5338.5  215.08  5395.0  216.04  5488.4  215.16
  5596.3  215.78  5623.8  216.73  5667.5  215.81  5732.6  215.89  5738.7  216.48
  5774.3  216.77  5809.9  216.38  5875.0  218.20  5889.7  217.19  5902.5  217.46
#Mann=3,-1,0
  4235.4    0.05       0  5018.5    0.05       0  5022.5    0.05       0
Bank Sta=5018.5,5022.5
Exp/Cntr=0.3,0.1

Type RM Length L Ch R = 1,97,0,0,0
BEGIN DESCRIPTION:
E21344
END DESCRIPTION:
XS GIS Cut Line= 4
      2464499.59     13615887.14      2464909.83     13616094.80
      2465398.55     13616056.82      2465871.02     13615493.39
#Sta/Elev= 30
  4327.1  217.73  4419.6  217.13  4464.2  217.20  4469.8  217.63  4514.3  216.61
  4625.7  215.56  4705.8  215.47  4913.7  214.07  4962.6  213.31  4980.8  212.47
  4981.0  211.97  4984.5  211.97  4984.8  212.47  4992.7  212.52  5002.7  213.48
  5042.8  213.79  5282.7  213.15  5332.1  213.77  5460.9  213.51  5510.3  214.26
  5644.9  214.19  5680.8  213.67  5709.4  214.44  5744.5  214.70  5751.0  214.30
  5758.8  214.73  5822.6  215.22  5829.1  214.77  5935.8  216.37  6012.4  218.59
#Mann=5,-1,0
  4327.1    0.05       0  4705.8   0.035       0  4913.7    0.05       0
  4980.8    0.05       0  4984.8    0.05       0
Bank Sta=4980.8,4984.8
Exp/Cntr=0.3,0.1

Chan Stop Cuts=-1