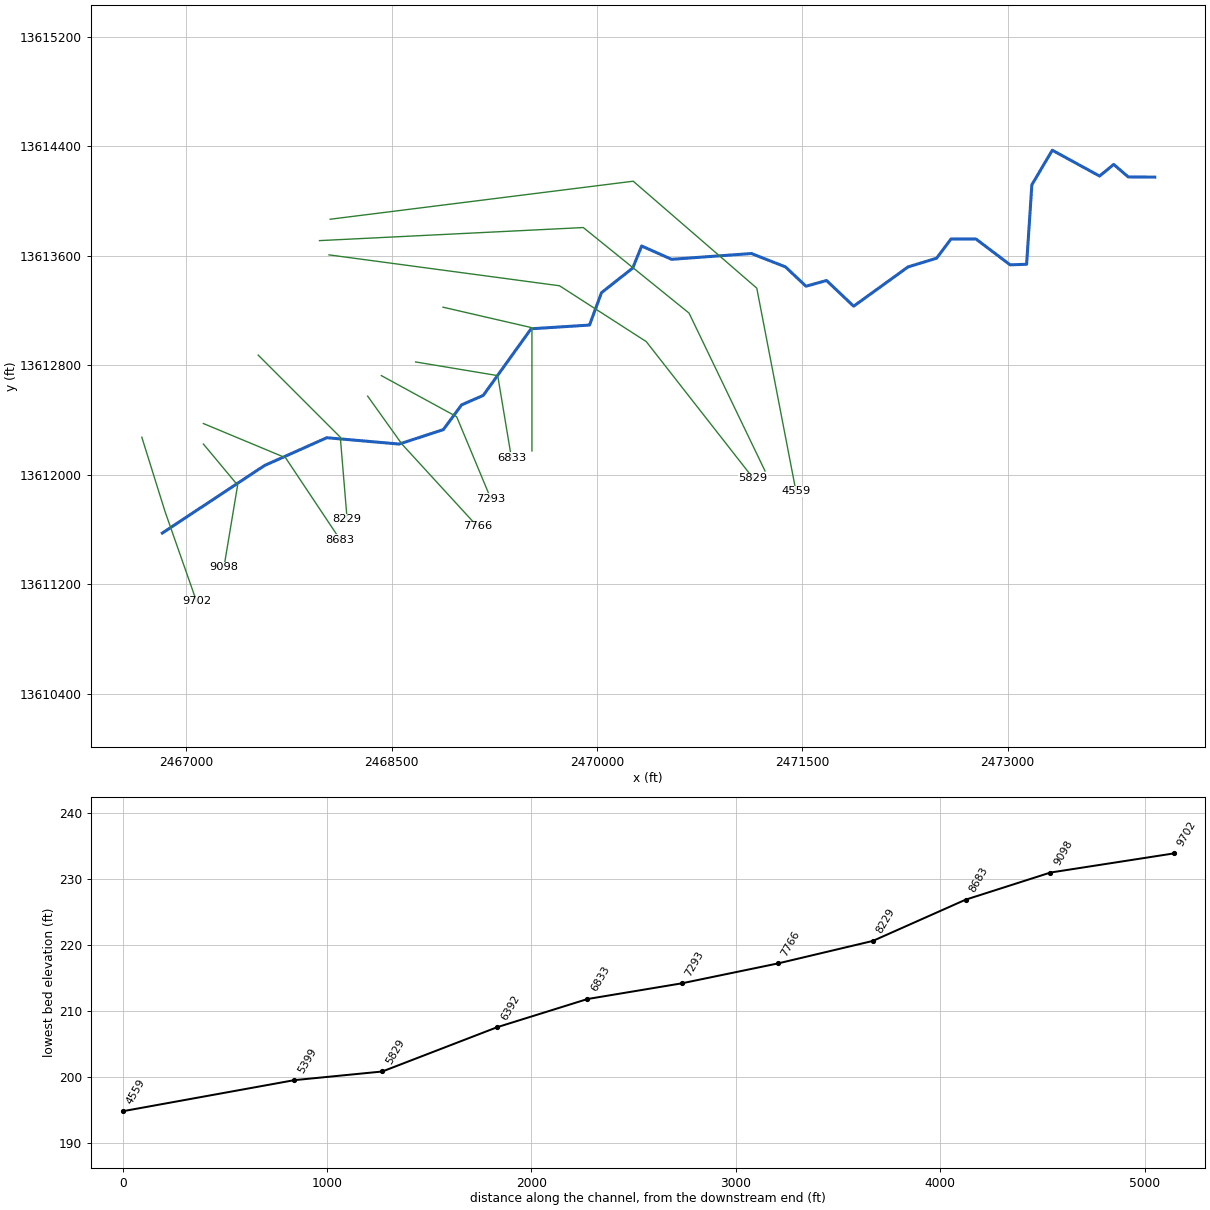
--- Stream0771.prj (project) ---

Proj Title=Stream0771 Base Level Engineering
Current Plan=p01
Default Exp/Contr=0.3,0.1
English Units
Geom File=g01
Flow File=f01
Plan File=p01
BEGIN DESCRIPTION:
Stream0771
END DESCRIPTION:

--- Stream0771.p01 (plan) ---

Plan Title=Multiple Run
Short Identifier=Multiple
Geom File=g01
Flow File=f01
Subcritical Flow
K Sum by GR= 0
Std Step Tol= 0.01
Critical Tol= 0.01
Num of Std Step Trials= 20
Max Error Tol= 0.3
Flow Tol Ratio= 0.001
Split Flow NTrial= 30
Split Flow Tol= 0.02
Split Flow Ratio= 0.02
Log Output Level= 0
Friction Slope Method= 1
Unsteady Friction Slope Method= 2
Unsteady Bridges Friction Slope Method= 1
Parabolic Critical Depth
Global Vel Dist=  1 , 1 , 1
Global Log Level= 0
CheckData=True
Encroach Param= -1, 0, 0, 0
BEGIN DESCRIPTION:
Multiple Run
END DESCRIPTION:

--- Stream0771.f01 (steady flow) ---

Flow Title=Multiple
Number of Profiles=7
Profile Names=10-year,25-year,50-year,1pct_min,100-year,1pct_plu,500-year
River Rch & RM= Stream0771,Reach-1,9702
     794    1307    1779    1173    2341    4671    4016
River Rch & RM= Stream0771,Reach-1,5829
     924    1521    2071    1364    2722    5430    4658
Boundary for River Rch & Prof#=Stream0771,Reach-1,1
Up Type=0
Dn Type=3
Dn Slope=0.005
Boundary for River Rch & Prof#=Stream0771,Reach-1,2
Up Type=0
Dn Type=3
Dn Slope=0.005
Boundary for River Rch & Prof#=Stream0771,Reach-1,3
Up Type=0
Dn Type=3
Dn Slope=0.005
Boundary for River Rch & Prof#=Stream0771,Reach-1,4
Up Type=0
Dn Type=3
Dn Slope=0.005
Boundary for River Rch & Prof#=Stream0771,Reach-1,5
Up Type=0
Dn Type=3
Dn Slope=0.005
Boundary for River Rch & Prof#=Stream0771,Reach-1,6
Up Type=0
Dn Type=3
Dn Slope=0.005
Boundary for River Rch & Prof#=Stream0771,Reach-1,7
Up Type=0
Dn Type=3
Dn Slope=0.005

--- Stream0771.g01 (geometry) ---

Geom Title=Existing Conditions

River Reach=Stream0771,Reach-1
Reach XY= 30
      2466825.00     13611575.00      2467572.71     13612069.15
      2468026.58     13612271.33      2468554.97     13612225.07
      2468877.44     13612330.52      2469011.44     13612511.53
      2469169.39     13612580.59      2469518.79     13613067.20
      2469945.65     13613094.40      2470033.14     13613331.06
      2470261.74     13613511.35      2470326.39     13613671.98
      2470545.20     13613574.78      2471128.30     13613616.92
      2471377.30     13613519.17      2471526.63     13613378.13
      2471677.30     13613419.91      2471875.00     13613232.07
      2472272.70     13613519.17      2472481.19     13613582.86
      2472586.83     13613723.38      2472769.07     13613722.76
      2473018.33     13613534.29      2473138.76     13613538.46
      2473177.07     13614119.14      2473326.33     13614371.67
      2473671.78     13614182.89      2473775.00     13614267.89
      2473881.05     13614176.67      2474075.00     13614175.00

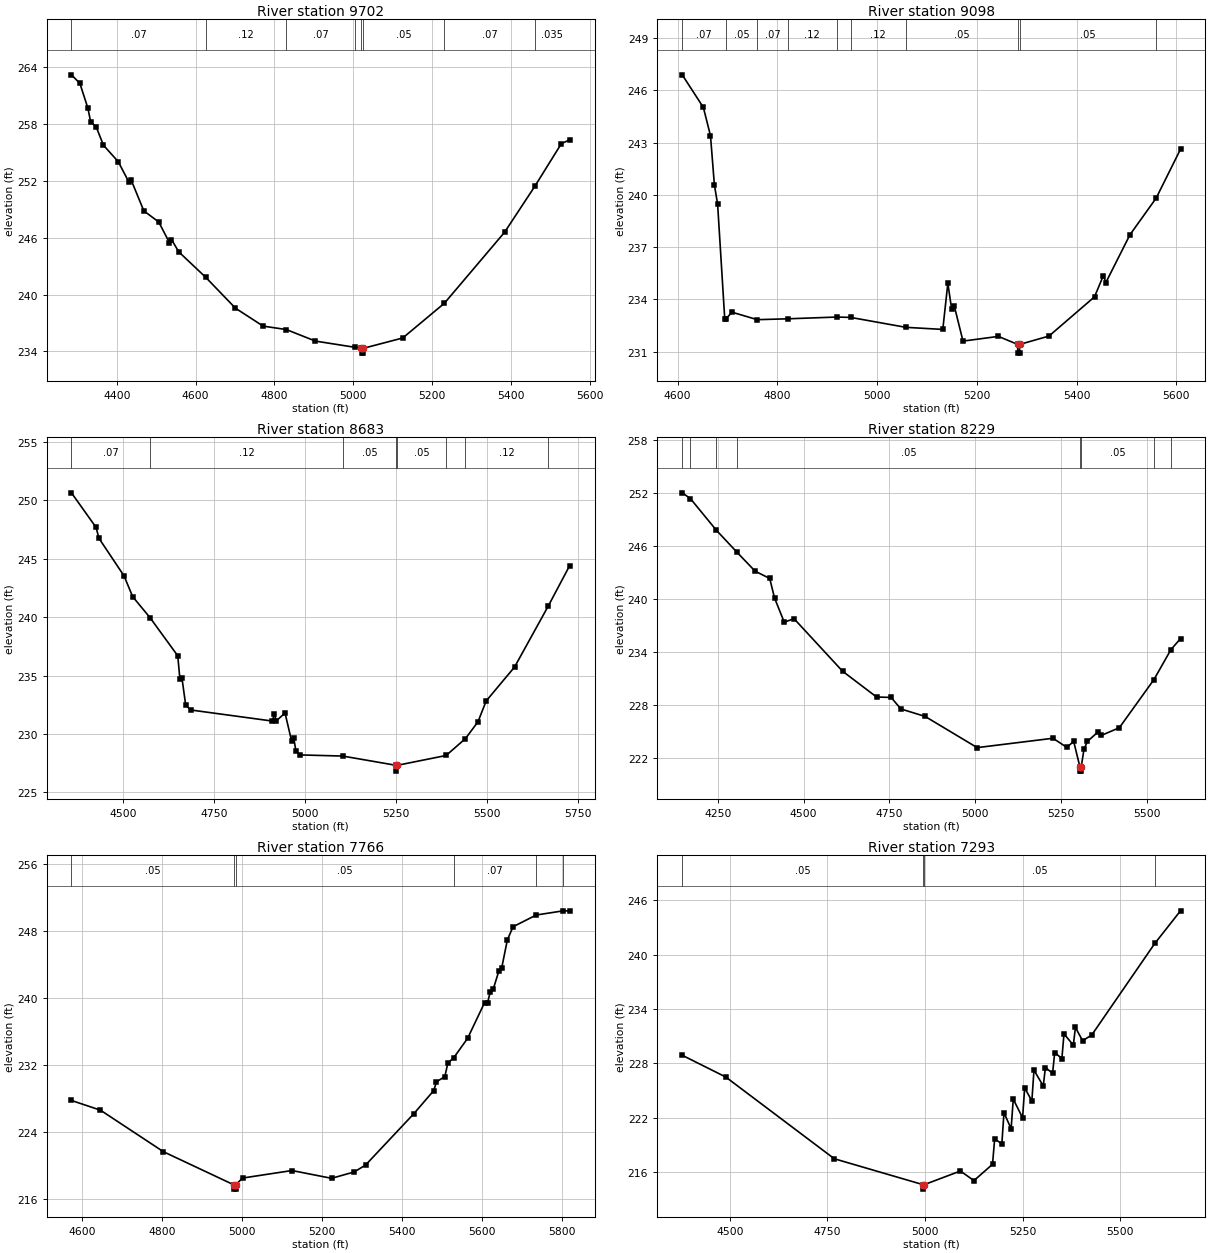
Type RM Length L Ch R = 1,9702,604,604,604
BEGIN DESCRIPTION:
Stream0771 16.0
END DESCRIPTION:
XS GIS Cut Line= 3
      2466675.01     13612274.96      2466844.62     13611732.12
      2467075.01     13611074.96
#Sta/Elev= 30
  4284.6  263.19  4306.0  262.29  4326.5  259.65  4333.3  258.23  4347.4  257.70
  4365.8  255.76  4403.5  254.02  4430.7  251.85  4436.0  252.11  4468.4  248.83
  4506.2  247.66  4533.4  245.48  4538.6  245.81  4557.0  244.51  4625.3  241.83
  4701.1  238.56  4771.3  236.67  4830.0  236.31  4904.2  235.09  5003.5  234.44
  5020.9  234.32  5021.2  233.82  5024.7  233.82  5024.9  234.32  5125.8  235.42
  5231.4  239.08  5384.4  246.58  5461.8  251.47  5528.5  255.93  5549.7  256.33
#Mann=8,-1,0
  4284.6    0.07       0  4625.3    0.12       0  4830.0    0.07       0
  5003.5    0.05       0  5020.9    0.05       0  5024.9    0.05       0
  5231.4    0.07       0  5461.8   0.035       0
Bank Sta=5020.9,5024.9
Exp/Cntr=0.3,0.1

Type RM Length L Ch R = 1,9098,415,415,415
BEGIN DESCRIPTION:
Stream0771 15.0
END DESCRIPTION:
XS GIS Cut Line= 3
      2467125.01     13612224.99      2467375.00     13611925.00
      2467275.00     13611324.98
#Sta/Elev= 30
  4609.5  246.89  4651.8  245.02  4666.1  243.40  4673.9  240.58  4680.4  239.47
  4694.7  232.88  4696.3  232.86  4709.1  233.27  4759.9  232.84  4821.6  232.89
  4919.0  232.99  4946.9  232.97  5057.8  232.40  5131.8  232.28  5141.9  234.93
  5149.5  233.45  5154.6  233.65  5172.3  231.61  5243.3  231.88  5281.9  231.42
  5282.1  230.92  5285.6  230.92  5285.9  231.42  5344.7  231.90  5435.9  234.15
  5453.7  235.37  5458.7  234.97  5506.9  237.71  5559.6  239.82  5608.3  242.62
#Mann=10,-1,0
  4609.5    0.07       0  4696.3    0.05       0  4759.9    0.07       0
  4821.6    0.12       0  4919.0    0.05       0  4946.9    0.12       0
  5057.8    0.05       0  5281.9    0.05       0  5285.9    0.05       0
  5559.6   0.035       0
Bank Sta=5281.9,5285.9
Exp/Cntr=0.3,0.1

Type RM Length L Ch R = 1,8683,454,454,454
BEGIN DESCRIPTION:
Stream0771 14.0
END DESCRIPTION:
XS GIS Cut Line= 3
      2467125.01     13612374.99      2467725.00     13612125.00
      2468125.00     13611525.00
#Sta/Elev= 30
  4356.9  250.65  4424.6  247.69  4432.7  246.75  4501.5  243.54  4525.3  241.76
  4573.0  239.96  4649.4  236.69  4655.3  234.70  4660.8  234.83  4671.1  232.50
  4684.6  232.05  4909.4  231.10  4915.3  231.69  4920.8  231.12  4944.6  231.79
  4963.0  229.35  4968.4  229.69  4974.4  228.56  4985.2  228.20  5103.5  228.10
  5249.8  227.31  5250.0  226.81  5253.8  227.31  5387.9  228.15  5441.2  229.60
  5475.6  231.04  5498.1  232.82  5576.3  235.73  5668.6  240.93  5728.0  244.42
#Mann=8,-1,0
  4356.9    0.07       0  4573.0    0.12       0  5103.5    0.05       0
  5249.8    0.05       0  5253.8    0.05       0  5387.9    0.07       0
  5441.2    0.12       0  5668.6    0.07       0
Bank Sta=5249.8,5253.8
Exp/Cntr=0.3,0.1

Type RM Length L Ch R = 1,8229,463,463,463
BEGIN DESCRIPTION:
Stream0771 13.0
END DESCRIPTION:
XS GIS Cut Line= 3
      2467524.97     13612875.03      2468125.00     13612275.00
      2468175.00     13611675.05
#Sta/Elev= 30
  4146.7  252.06  4170.4  251.41  4245.7  247.84  4305.9  245.34  4358.9  243.19
  4401.3  242.37  4415.4  240.16  4443.7  237.41  4472.0  237.82  4613.4  231.87
  4712.4  228.95  4754.9  228.90  4783.1  227.60  4853.8  226.75  5005.3  223.22
  5226.1  224.28  5266.2  223.25  5286.3  223.92  5304.3  221.06  5304.6  220.56
  5308.1  220.56  5308.3  221.06  5316.4  223.06  5326.4  223.93  5356.5  224.97
  5366.6  224.60  5419.2  225.47  5519.9  230.92  5569.4  234.31  5597.3  235.56
#Mann=8,-1,0
  4146.7    0.05       0  4170.4    0.07       0  4245.7    0.12       0
  4305.9    0.05       0  5304.3    0.05       0  5308.3    0.05       0
  5519.9    0.07       0  5569.4    0.12       0
Bank Sta=5304.3,5308.3
Exp/Cntr=0.3,0.1

Type RM Length L Ch R = 1,7766,473,473,473
BEGIN DESCRIPTION:
Stream0771 12.0
END DESCRIPTION:
XS GIS Cut Line= 3
      2468324.98     13612575.03      2468575.00     13612225.00
      2469125.00     13611625.00
#Sta/Elev= 30
  4574.1  227.74  4646.6  226.58  4803.9  221.62  4980.1  217.66  4980.4  217.16
  4983.9  217.16  4984.1  217.66  5001.2  218.48  5124.8  219.38  5223.5  218.45
  5280.2  219.21  5308.6  220.04  5428.8  226.15  5478.7  228.92  5485.5  229.96
  5506.5  230.60  5513.9  232.20  5528.8  232.85  5563.2  235.15  5605.8  239.43
  5613.2  239.43  5620.0  240.72  5627.4  241.05  5641.5  243.22  5648.3  243.53
  5662.5  246.90  5676.7  248.47  5734.7  249.87  5802.0  250.37  5818.2  250.35
#Mann=6,-1,0
  4574.1    0.05       0  4980.1    0.05       0  4984.1    0.05       0
  5528.8    0.07       0  5734.7    0.12       0  5802.0    0.07       0
Bank Sta=4980.1,4984.1
Exp/Cntr=0.3,0.1

Type RM Length L Ch R = 1,7293,460,460,460
BEGIN DESCRIPTION:
Stream0771 11.0
END DESCRIPTION:
XS GIS Cut Line= 3
      2468425.02     13612724.99      2468975.00     13612425.00
      2469225.01     13611824.98
#Sta/Elev= 30
  4377.9  228.90  4489.4  226.50  4767.5  217.48  4994.3  214.63  4994.6  214.13
  4998.3  214.63  5090.5  216.13  5125.2  215.07  5172.8  216.87  5178.3  219.68
  5196.7  219.12  5202.1  222.56  5220.5  220.80  5225.9  224.06  5249.8  222.01
  5255.2  225.30  5273.6  223.86  5279.0  227.26  5302.8  225.51  5308.3  227.55
  5326.7  226.91  5332.1  229.20  5350.5  228.54  5355.9  231.26  5379.8  230.02
  5385.2  231.97  5403.6  230.51  5426.9  231.13  5588.5  241.24  5654.4  244.84
#Mann=4,-1,0
  4377.9    0.05       0  4994.3    0.05       0  4998.3    0.05       0
  5588.5    0.07       0
Bank Sta=4994.3,4998.3
Exp/Cntr=0.3,0.1

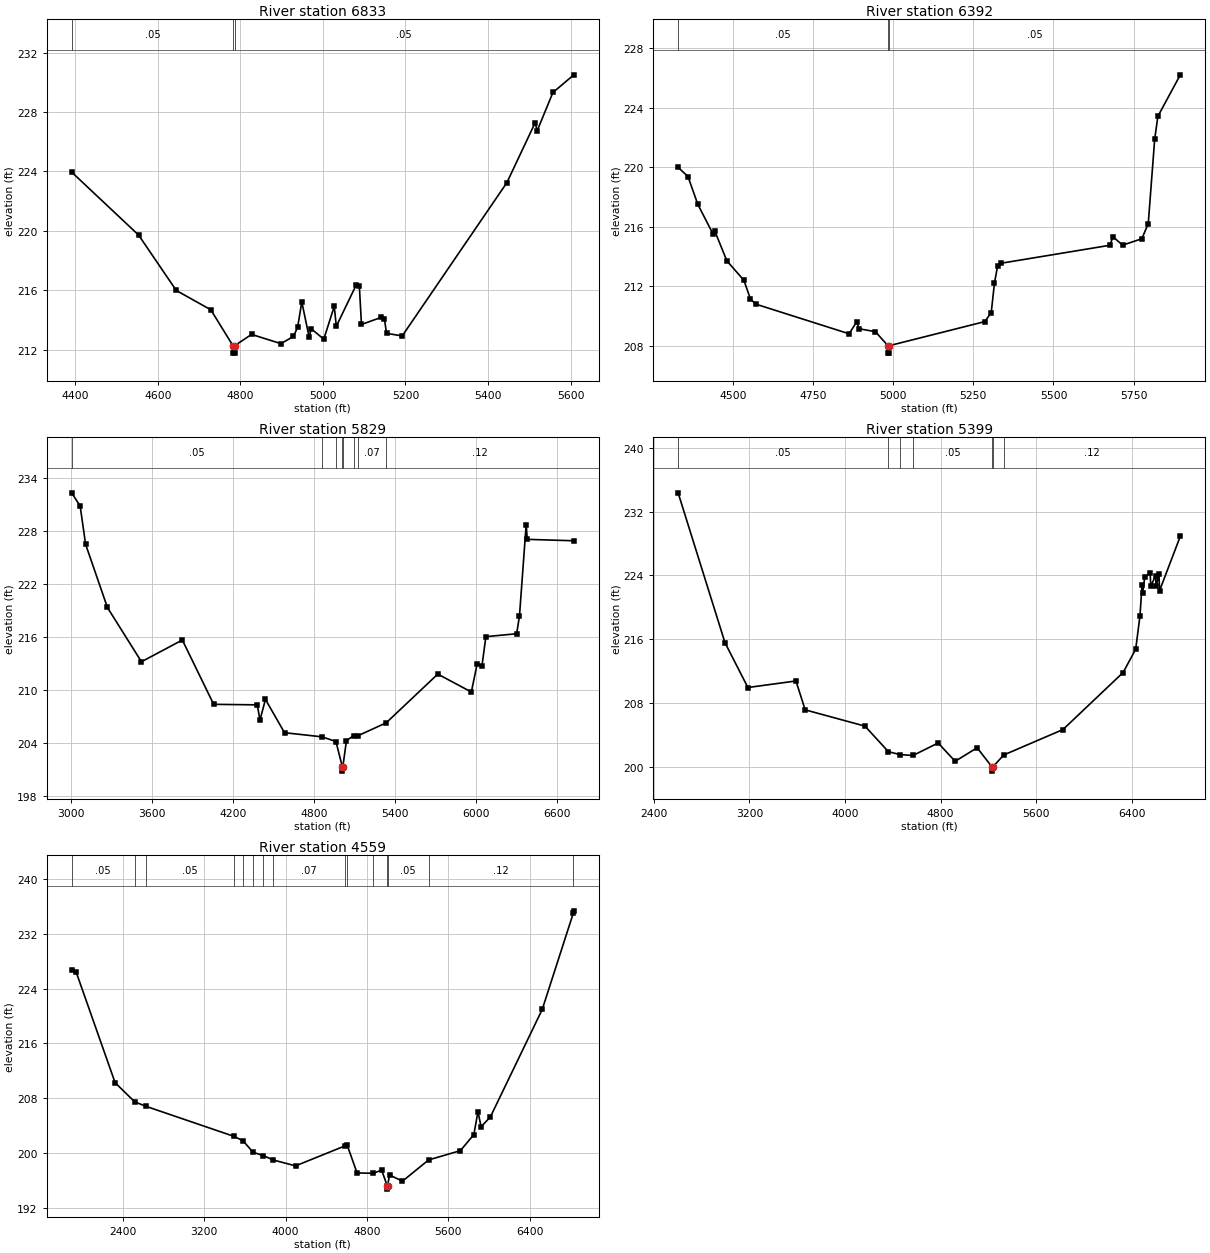
Type RM Length L Ch R = 1,6833,441,441,441
BEGIN DESCRIPTION:
Stream0771 10.0
END DESCRIPTION:
XS GIS Cut Line= 3
      2468675.05     13612824.99      2469275.00     13612725.00
      2469375.00     13612125.01
#Sta/Elev= 30
  4391.5  223.95  4553.7  219.71  4644.9  215.98  4728.5  214.68  4782.3  212.26
  4782.5  211.76  4786.0  211.76  4786.3  212.26  4827.4  213.02  4898.3  212.40
  4928.8  212.88  4938.9  213.50  4949.0  215.21  4966.8  212.84  4971.8  213.40
  5002.3  212.70  5027.6  214.91  5032.7  213.57  5080.8  216.35  5088.4  216.29
  5093.5  213.69  5141.7  214.17  5149.3  214.03  5154.3  213.09  5192.3  212.92
  5445.8  223.24  5514.2  227.27  5519.3  226.74  5557.3  229.31  5608.0  230.50
#Mann=3,-1,0
  4391.5    0.05       0  4782.3    0.05       0  4786.3    0.05       0
Bank Sta=4782.3,4786.3
Exp/Cntr=0.3,0.1

Type RM Length L Ch R = 1,6392,563,563,563
BEGIN DESCRIPTION:
Stream0771 9.0
END DESCRIPTION:
XS GIS Cut Line= 3
      2468875.03     13613224.99      2469525.00     13613075.00
      2469525.00     13612174.96
#Sta/Elev= 30
  4328.7  219.99  4359.5  219.37  4390.2  217.50  4438.1  215.49  4443.3  215.70
  4480.9  213.70  4533.9  212.40  4554.5  211.13  4571.6  210.79  4862.3  208.80
  4886.3  209.62  4893.1  209.14  4944.4  208.94  4983.5  208.00  4983.7  207.50
  4987.2  207.50  4987.5  208.00  5285.8  209.62  5305.8  210.23  5315.8  212.20
  5325.8  213.38  5335.8  213.54  5675.8  214.75  5685.8  215.32  5715.8  214.76
  5775.8  215.19  5795.8  216.21  5815.8  221.87  5825.8  223.42  5895.8  226.21
#Mann=3,-1,0
  4328.7    0.05       0  4983.5    0.05       0  4987.5    0.05       0
Bank Sta=4983.5,4987.5
Exp/Cntr=0.3,0.1

Type RM Length L Ch R = 1,5829,430,430,430
BEGIN DESCRIPTION:
XS7701
END DESCRIPTION:
XS GIS Cut Line= 4
      2468042.58     13613607.11      2469726.56     13613381.42
      2470360.24     13612973.44      2471140.74     13611976.14
#Sta/Elev= 30
  3002.4  232.36  3065.4  230.86  3105.7  226.52  3267.2  219.35  3519.4  213.19
  3822.1  215.66  4054.1  208.36  4377.0  208.30  4397.2  206.57  4437.5  208.92
  4578.8  205.14  4857.5  204.67  4959.6  204.14  5006.8  201.28  5007.1  200.78
  5010.8  201.28  5037.6  204.25  5091.0  204.80  5121.7  204.79  5331.8  206.26
  5713.9  211.79  5962.5  209.76  6005.9  212.98  6041.2  212.73  6070.1  216.04
  6298.0  216.37  6318.8  218.37  6368.5  228.76  6376.7  227.08  6721.5  226.92
#Mann=8,-1,0
  3002.4    0.05       0  4857.5   0.035       0  4959.6    0.07       0
  5006.8    0.05       0  5010.8    0.07       0  5091.0    0.12       0
  5121.7    0.07       0  5331.8    0.12       0
Bank Sta=5006.8,5010.8
Exp/Cntr=0.3,0.1

Type RM Length L Ch R = 1,5399,840,840,840
BEGIN DESCRIPTION:
XS7700
END DESCRIPTION:
XS GIS Cut Line= 4
      2467973.04     13613711.28      2469900.17     13613806.77
      2470672.74     13613181.77      2471227.63     13612028.65
#Sta/Elev= 30
  2603.6  234.35  2996.0  215.56  3187.6  209.95  3589.9  210.77  3666.9  207.15
  4167.5  205.11  4363.8  201.90  4462.1  201.54  4569.2  201.43  4779.8  203.00
  4922.1  200.70  5106.0  202.40  5231.9  199.97  5232.2  199.47  5235.9  199.97
  5328.3  201.49  5824.4  204.68  6327.7  211.83  6433.2  214.75  6469.1  218.95
  6486.1  222.81  6491.7  221.79  6508.8  223.80  6554.0  224.31  6559.6  222.63
  6599.3  223.98  6604.8  222.61  6627.5  224.23  6633.0  222.09  6806.5  228.91
#Mann=7,-1,0
  2603.6    0.05       0  4363.8    0.12       0  4462.1    0.07       0
  4569.2    0.05       0  5231.9    0.05       0  5235.9    0.05       0
  5328.3    0.12       0
Bank Sta=5231.9,5235.9
Exp/Cntr=0.3,0.1

Type RM Length L Ch R = 1,4559,0,0,0
BEGIN DESCRIPTION:
XS7699
END DESCRIPTION:
XS GIS Cut Line= 4
      2468051.20     13613867.53      2470264.76     13614145.31
      2471167.53     13613364.06      2471453.96     13611879.85
#Sta/Elev= 30
  1897.5  226.66  1941.6  226.42  2324.6  210.28  2517.0  207.49  2625.1  206.85
  3495.8  202.44  3582.5  201.80  3681.3  200.13  3780.1  199.66  3878.9  199.01
  4098.4  198.15  4580.1  201.04  4605.8  201.18  4703.0  197.12  4863.9  197.07
  4944.3  197.54  4999.3  195.26  4999.5  194.76  5003.3  195.26  5022.1  196.82
  5149.4  195.92  5406.5  199.02  5718.5  200.37  5850.9  202.71  5891.7  206.06
  5922.2  203.85  6013.9  205.30  6523.1  220.96  6827.7  234.96  6833.9  235.34
#Mann=15,-1,0
  1897.5    0.05       0  2517.0    0.12       0  2625.1    0.05       0
  3495.8    0.07       0  3582.5    0.12       0  3681.3    0.05       0
  3780.1    0.12       0  3878.9    0.07       0  4580.1   0.035       0
  4605.8    0.12       0  4863.9    0.05       0  4999.3    0.05       0
  5003.3    0.05       0  5406.5    0.12       0  6827.7    0.07       0
Bank Sta=4999.3,5003.3
Exp/Cntr=0.3,0.1

Chan Stop Cuts=-1