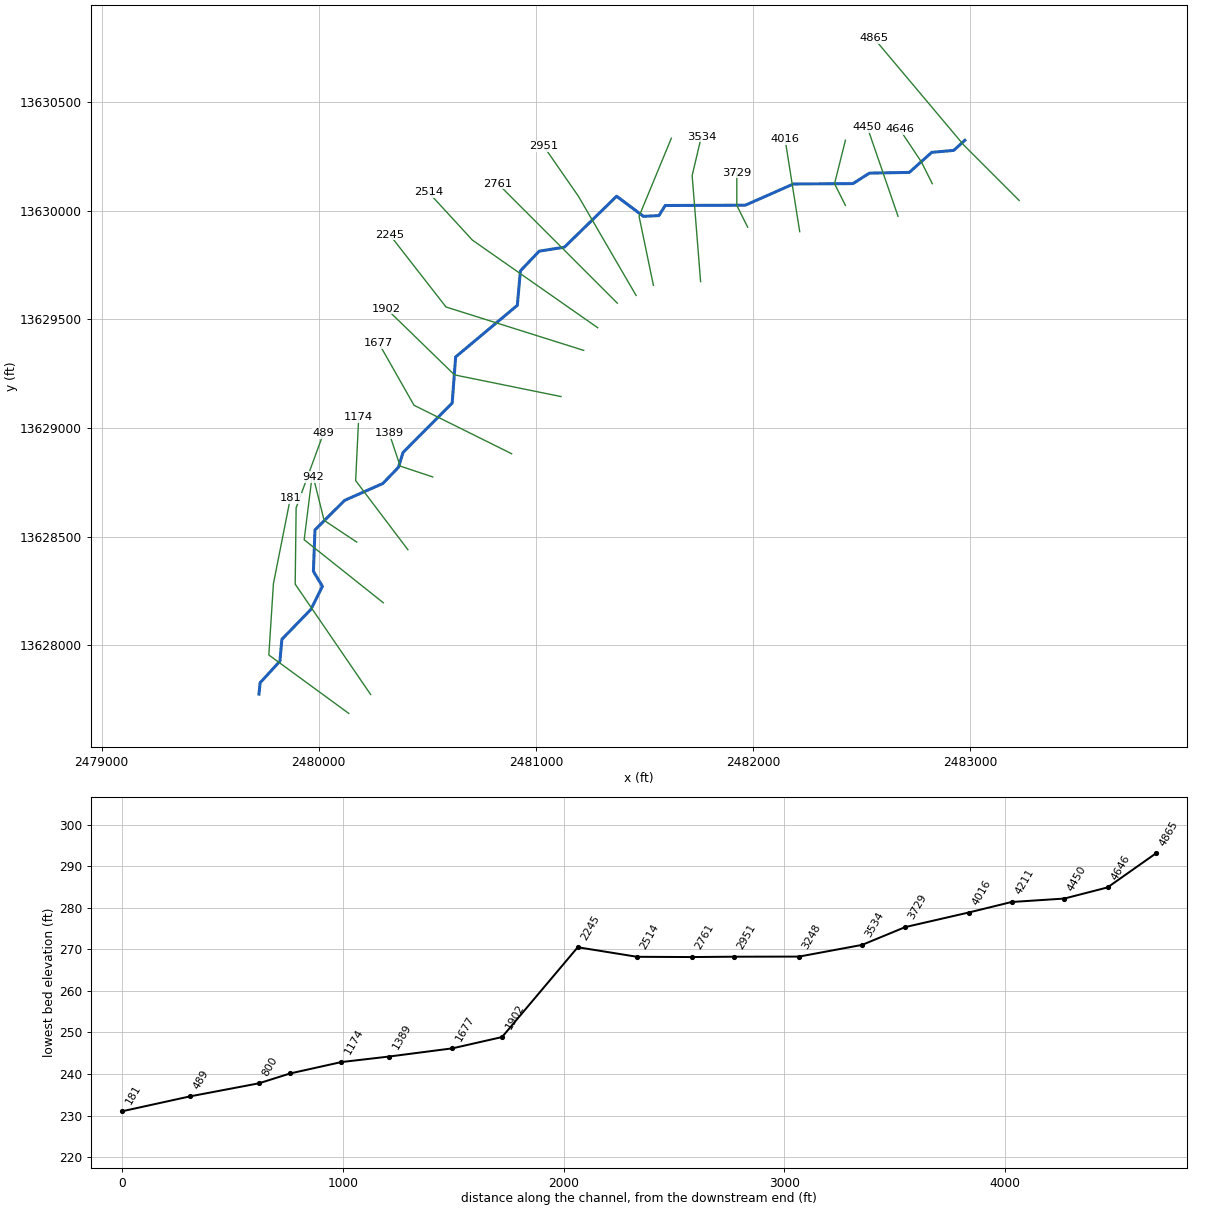
--- Stream0774.prj (project) ---

Proj Title=Stream0774 Base Level Engineering
Current Plan=p01
Default Exp/Contr=0.3,0.1
English Units
Geom File=g01
Flow File=f01
Plan File=p01
BEGIN DESCRIPTION:
Stream0774
END DESCRIPTION:

--- Stream0774.p01 (plan) ---

Plan Title=Multiple Run
Short Identifier=Multiple
Geom File=g01
Flow File=f01
Subcritical Flow
K Sum by GR= 0
Std Step Tol= 0.01
Critical Tol= 0.01
Num of Std Step Trials= 20
Max Error Tol= 0.3
Flow Tol Ratio= 0.001
Split Flow NTrial= 30
Split Flow Tol= 0.02
Split Flow Ratio= 0.02
Log Output Level= 0
Friction Slope Method= 1
Unsteady Friction Slope Method= 2
Unsteady Bridges Friction Slope Method= 1
Parabolic Critical Depth
Global Vel Dist=  1 , 1 , 1
Global Log Level= 0
CheckData=True
Encroach Param= -1, 0, 0, 0
BEGIN DESCRIPTION:
Multiple Run
END DESCRIPTION:

--- Stream0774.f01 (steady flow) ---

Flow Title=Multiple
Number of Profiles=7
Profile Names=10-year,25-year,50-year,1pct_min,100-year,1pct_plu,500-year
River Rch & RM= Stream0774,Reach-1,4865
     641    1043    1410     925    1846    3683    3129
Boundary for River Rch & Prof#=Stream0774,Reach-1,1
Up Type=0
Dn Type=3
Dn Slope=0.005
Boundary for River Rch & Prof#=Stream0774,Reach-1,2
Up Type=0
Dn Type=3
Dn Slope=0.005
Boundary for River Rch & Prof#=Stream0774,Reach-1,3
Up Type=0
Dn Type=3
Dn Slope=0.005
Boundary for River Rch & Prof#=Stream0774,Reach-1,4
Up Type=0
Dn Type=3
Dn Slope=0.005
Boundary for River Rch & Prof#=Stream0774,Reach-1,5
Up Type=0
Dn Type=3
Dn Slope=0.005
Boundary for River Rch & Prof#=Stream0774,Reach-1,6
Up Type=0
Dn Type=3
Dn Slope=0.005
Boundary for River Rch & Prof#=Stream0774,Reach-1,7
Up Type=0
Dn Type=3
Dn Slope=0.005

--- Stream0774.g01 (geometry) ---

Geom Title=Existing Conditions

River Reach=Stream0774,Reach-1
Reach XY= 30
      2482975.00     13630325.00      2482923.59     13630278.39
      2482822.57     13630269.48      2482719.14     13630177.07
      2482535.51     13630173.78      2482459.78     13630125.52
      2482185.50     13630123.78      2481964.50     13630026.22
      2481595.29     13630024.70      2481566.50     13629978.37
      2481495.20     13629974.75      2481371.66     13630067.40
      2481131.17     13629832.86      2481015.19     13629814.49
      2480928.54     13629723.54      2480914.52     13629565.20
      2480630.45     13629327.47      2480614.52     13629115.20
      2480388.63     13628888.21      2480366.85     13628818.93
      2480295.13     13628744.77      2480118.94     13628666.86
      2479982.81     13628531.19      2479975.66     13628340.16
      2480016.96     13628271.68      2479964.25     13628165.32
      2479830.52     13628027.43      2479821.39     13627926.50
      2479730.33     13627827.51      2479725.00     13627775.00

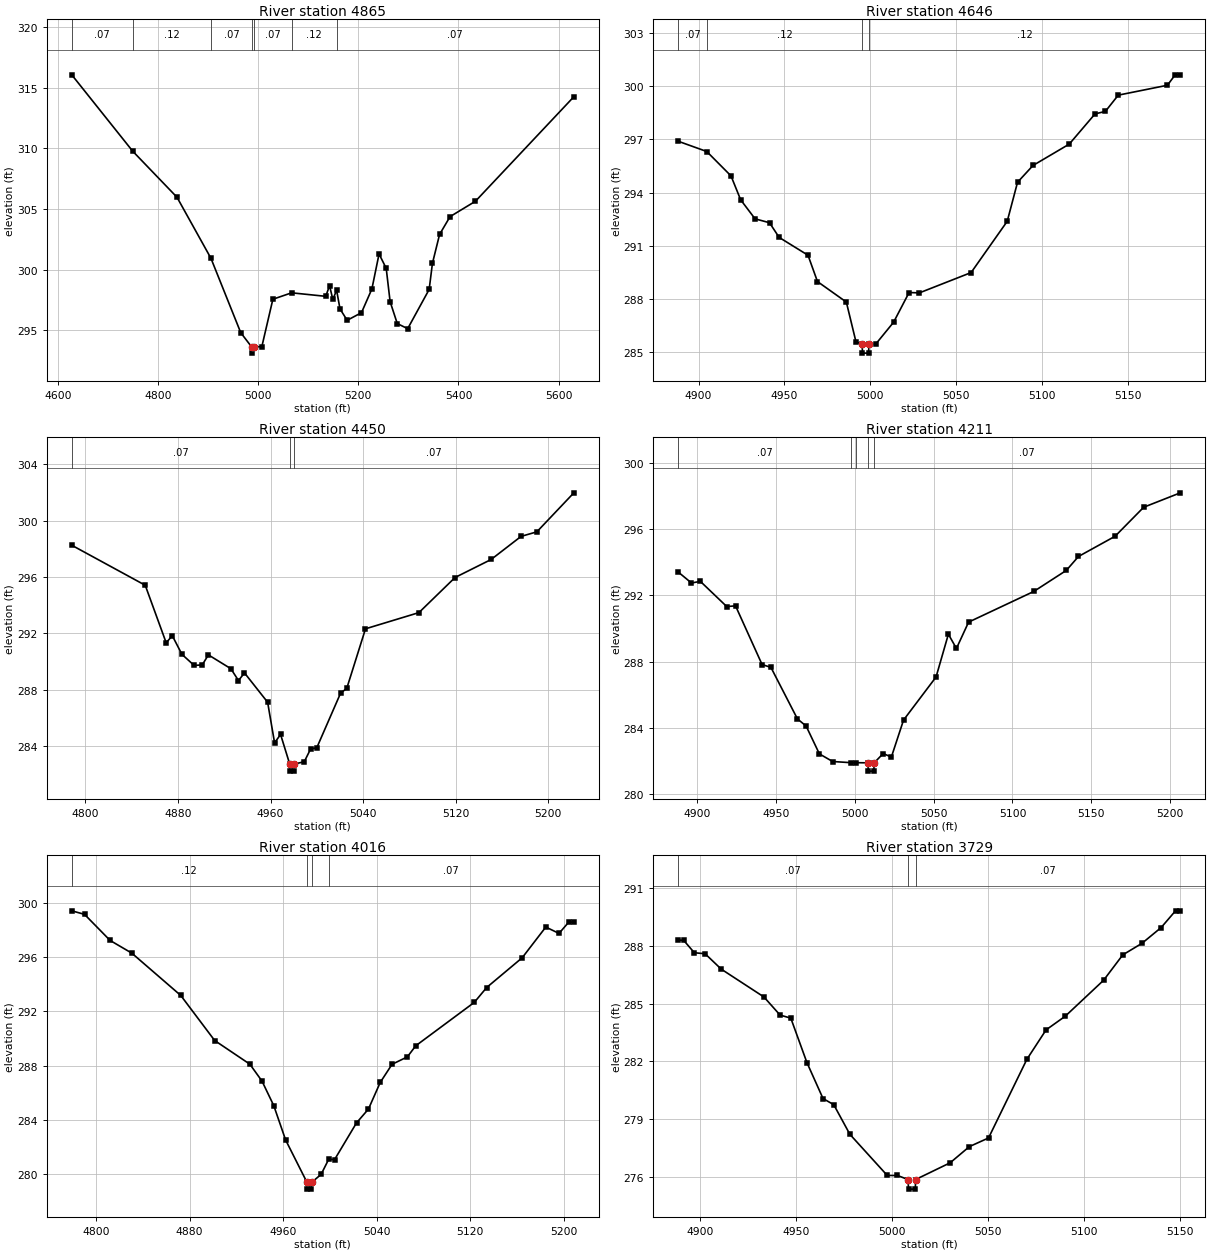
Type RM Length L Ch R = 1,4865,219,219,219
BEGIN DESCRIPTION:
XS7709
END DESCRIPTION:
XS GIS Cut Line= 3
      2483225.09     13630047.82      2482969.01     13630303.91
      2482556.68     13630794.36
#Sta/Elev= 30
  4627.6  316.08  4749.2  309.78  4837.8  305.97  4905.6  300.93  4965.1  294.79
  4987.1  293.60  4987.3  293.10  4991.1  293.60  5007.3  293.64  5029.3  297.55
  5066.8  298.08  5134.9  297.79  5142.5  298.67  5149.1  297.53  5156.6  298.30
  5163.4  296.75  5177.7  295.81  5206.3  296.44  5227.1  298.40  5241.4  301.29
  5255.7  300.10  5263.5  297.35  5277.8  295.54  5298.6  295.12  5341.5  298.36
  5348.0  300.51  5362.3  302.90  5383.2  304.37  5433.9  305.64  5630.5  314.27
#Mann=7,-1,0
  4627.6    0.07       0  4749.2    0.12       0  4905.6    0.07       0
  4987.1    0.05       0  4991.1    0.07       0  5066.8    0.12       0
  5156.6    0.07       0
Bank Sta=4987.1,4991.1
Exp/Cntr=0.3,0.1

Type RM Length L Ch R = 1,4646,196,196,196
BEGIN DESCRIPTION:
Stream0774 9.0
END DESCRIPTION:
XS GIS Cut Line= 3
      2482825.00     13630125.01      2482775.00     13630225.00
      2482674.98     13630375.02
#Sta/Elev= 30
  4888.2  296.90  4904.8  296.32  4918.9  294.94  4924.5  293.59  4932.9  292.51
  4941.3  292.29  4946.9  291.46  4963.7  290.45  4969.2  288.96  4986.0  287.80
  4991.6  285.55  4995.2  285.41  4995.4  284.91  4998.9  284.91  4999.2  285.41
  5003.0  285.41  5013.5  286.66  5022.5  288.34  5028.5  288.32  5058.6  289.47
  5079.6  292.37  5085.6  294.58  5094.6  295.53  5115.7  296.74  5130.7  298.45
  5136.7  298.59  5144.2  299.51  5172.8  300.07  5177.3  300.66  5180.3  300.66
#Mann=4,-1,0
  4888.2    0.07       0  4904.8    0.12       0  4995.2    0.05       0
  4999.2    0.12       0
Bank Sta=4995.2,4999.2
Exp/Cntr=0.3,0.1

Type RM Length L Ch R = 1,4450,239,239,239
BEGIN DESCRIPTION:
E21354
END DESCRIPTION:
XS GIS Cut Line= 2
      2482667.36     13629974.98      2482525.88     13630385.27
#Sta/Elev= 30
  4788.2  298.26  4851.7  295.42  4869.8  291.34  4875.1  291.84  4883.4  290.52
  4894.0  289.73  4901.0  289.77  4906.3  290.48  4925.7  289.50  4932.3  288.66
  4937.5  289.20  4957.5  287.12  4963.5  284.24  4968.7  284.83  4976.6  282.73
  4976.9  282.23  4980.4  282.23  4980.6  282.73  4989.2  282.90  4994.7  283.81
  5000.0  283.89  5020.6  287.77  5025.9  288.10  5042.1  292.33  5088.3  293.48
  5119.5  295.97  5150.7  297.25  5176.6  298.89  5190.2  299.21  5222.2  301.98
#Mann=3,-1,0
  4788.2    0.07       0  4976.6    0.05       0  4980.6    0.07       0
Bank Sta=4976.6,4980.6
Exp/Cntr=0.3,0.1

Type RM Length L Ch R = 1,4211,195,195,195
BEGIN DESCRIPTION:
Stream0774 8.0
END DESCRIPTION:
XS GIS Cut Line= 3
      2482425.00     13630025.01      2482375.00     13630125.00
      2482425.01     13630325.05
#Sta/Elev= 30
  4888.3  293.41  4896.7  292.75  4902.3  292.85  4919.0  291.33  4924.6  291.37
  4941.4  287.83  4947.0  287.66  4963.8  284.55  4969.3  284.12  4977.7  282.44
  4986.1  281.98  4997.7  281.91  5001.0  281.91  5008.4  281.90  5008.7  281.40
  5012.2  281.40  5012.4  281.90  5018.1  282.46  5023.3  282.25  5031.0  284.48
  5051.6  287.08  5059.4  289.66  5064.5  288.80  5072.2  290.39  5113.5  292.24
  5134.1  293.51  5141.8  294.35  5165.0  295.57  5183.1  297.32  5206.3  298.19
#Mann=5,-1,0
  4888.3    0.07       0  4997.7    0.12       0  5001.0    0.07       0
  5008.4    0.05       0  5012.4    0.07       0
Bank Sta=5008.4,5012.4
Exp/Cntr=0.3,0.1

Type RM Length L Ch R = 1,4016,287,287,287
BEGIN DESCRIPTION:
E21353
END DESCRIPTION:
XS GIS Cut Line= 2
      2482214.59     13629904.25      2482147.40     13630328.66
#Sta/Elev= 30
  4779.1  299.44  4790.0  299.18  4811.9  297.25  4830.5  296.31  4872.4  293.18
  4901.4  289.85  4931.5  288.10  4941.9  286.85  4952.0  285.03  4962.1  282.50
  4980.4  279.36  4980.6  278.86  4984.1  278.86  4984.4  279.36  4992.5  279.95
  4999.0  281.07  5004.0  281.04  5022.8  283.76  5033.0  284.78  5043.1  286.75
  5053.2  288.09  5066.3  288.64  5073.5  289.46  5123.6  292.67  5134.2  293.77
  5164.6  295.97  5184.8  298.24  5196.1  297.77  5204.4  298.60  5208.8  298.60
#Mann=4,-1,0
  4779.1    0.12       0  4980.4    0.05       0  4984.4    0.12       0
  4999.0    0.07       0
Bank Sta=4980.4,4984.4
Exp/Cntr=0.3,0.1

Type RM Length L Ch R = 1,3729,195,195,195
BEGIN DESCRIPTION:
Stream0774 7.0
END DESCRIPTION:
XS GIS Cut Line= 3
      2481975.01     13629924.98      2481925.00     13630025.00
      2481925.00     13630174.97
#Sta/Elev= 30
  4888.6  288.30  4891.4  288.30  4897.0  287.65  4902.6  287.60  4911.0  286.80
  4933.3  285.35  4941.7  284.41  4947.3  284.25  4955.7  281.94  4964.1  280.07
  4969.7  279.75  4978.1  278.21  4997.6  276.07  5002.9  276.07  5008.4  275.86
  5008.7  275.36  5012.2  275.36  5012.4  275.86  5030.4  276.73  5040.4  277.57
  5050.4  278.02  5070.4  282.11  5080.4  283.64  5090.4  284.35  5110.4  286.22
  5120.4  287.54  5130.4  288.14  5140.4  288.96  5147.9  289.83  5150.4  289.83
#Mann=3,-1,0
  4888.6    0.07       0  5008.4    0.05       0  5012.4    0.07       0
Bank Sta=5008.4,5012.4
Exp/Cntr=0.3,0.1

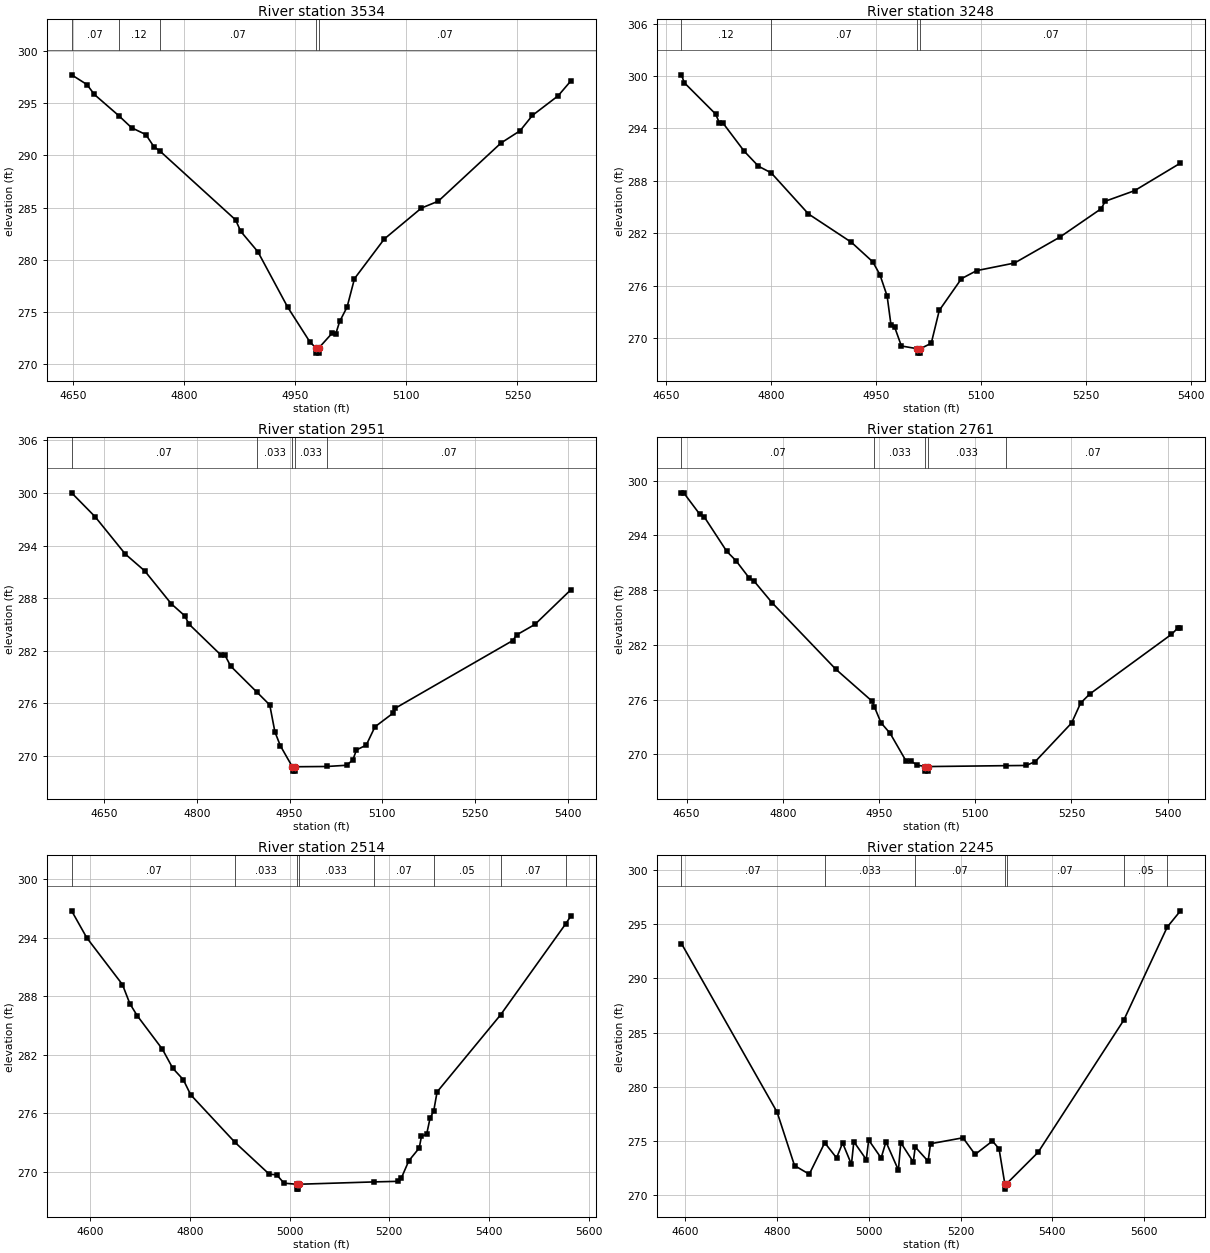
Type RM Length L Ch R = 1,3534,286,286,286
BEGIN DESCRIPTION:
E21352
END DESCRIPTION:
XS GIS Cut Line= 3
      2481758.30     13629674.36      2481719.39     13630162.45
      2481761.50     13630341.42
#Sta/Elev= 30
  4648.2  297.71  4668.9  296.78  4678.9  295.83  4711.7  293.81  4729.1  292.65
  4748.4  291.99  4759.2  290.84  4767.5  290.41  4869.5  283.83  4876.5  282.73
  4899.6  280.78  4939.8  275.48  4969.9  272.14  4977.9  271.58  4978.1  271.08
  4981.6  271.08  4981.9  271.58  4999.6  272.97  5004.6  272.90  5010.0  274.11
  5020.0  275.49  5030.0  278.21  5070.2  282.00  5120.3  284.96  5143.1  285.62
  5227.8  291.19  5253.5  292.36  5270.2  293.83  5304.8  295.70  5321.7  297.10
#Mann=5,-1,0
  4648.2    0.07       0  4711.7    0.12       0  4767.5    0.07       0
  4977.9    0.05       0  4981.9    0.07       0
Bank Sta=4977.9,4981.9
Exp/Cntr=0.3,0.1

Type RM Length L Ch R = 1,3248,297,297,297
BEGIN DESCRIPTION:
Stream0774 6.0
END DESCRIPTION:
XS GIS Cut Line= 3
      2481541.06     13629657.20      2481475.00     13629975.00
      2481623.53     13630334.31
#Sta/Elev= 30
  4671.6  300.14  4675.6  299.24  4720.4  295.65  4725.7  294.66  4730.8  294.63
  4761.3  291.39  4781.7  289.67  4799.9  288.91  4853.2  284.20  4914.5  280.96
  4945.1  278.72  4955.3  277.25  4965.6  274.81  4971.1  271.52  4976.3  271.26
  4986.0  269.08  5008.9  268.76  5009.1  268.26  5012.6  268.26  5012.9  268.76
  5028.7  269.39  5040.2  273.16  5071.9  276.79  5093.6  277.71  5147.7  278.58
  5212.6  281.55  5271.6  284.80  5277.5  285.66  5319.4  286.87  5385.0  290.03
#Mann=4,-1,0
  4671.6    0.12       0  4799.9    0.07       0  5008.9    0.05       0
  5012.9    0.07       0
Bank Sta=5008.9,5012.9
Exp/Cntr=0.3,0.1

Type RM Length L Ch R = 1,2951,190,190,190
BEGIN DESCRIPTION:
E21351
END DESCRIPTION:
XS GIS Cut Line= 3
      2481461.16     13629610.66      2481195.88     13630066.95
      2481036.73     13630296.83
#Sta/Elev= 30
  4597.3  300.02  4635.3  297.29  4684.1  293.03  4715.6  291.10  4758.6  287.34
  4780.1  285.99  4787.4  285.01  4838.9  281.49  4845.2  281.50  4854.6  280.23
  4897.0  277.26  4917.9  275.79  4926.2  272.72  4934.9  271.15  4954.4  268.73
  4954.7  268.23  4958.2  268.23  4958.4  268.73  5010.2  268.76  5042.5  268.90
  5052.4  269.53  5058.2  270.65  5074.0  271.20  5088.1  273.29  5117.0  274.83
  5121.1  275.42  5311.2  283.15  5317.3  283.79  5347.0  284.99  5404.7  288.92
#Mann=5,-1,0
  4597.3    0.07       0  4897.0   0.033       0  4954.4   0.033       0
  4958.4   0.033       0  5010.2    0.07       0
Bank Sta=4954.4,4958.4
Exp/Cntr=0.3,0.1

Type RM Length L Ch R = 1,2761,247,247,247
BEGIN DESCRIPTION:
Stream0774 5.0
END DESCRIPTION:
XS GIS Cut Line= 3
      2481374.99     13629575.01      2481125.00     13629825.00
      2480825.00     13630125.00
#Sta/Elev= 30
  4642.1  298.68  4645.6  298.68  4670.4  296.35  4677.4  296.06  4712.8  292.25
  4726.9  291.25  4748.1  289.30  4755.2  289.00  4783.5  286.61  4882.5  279.34
  4939.1  275.83  4942.9  275.19  4953.2  273.45  4967.4  272.29  4992.1  269.27
  4999.2  269.27  5009.8  268.81  5021.9  268.65  5022.2  268.15  5025.7  268.15
  5025.9  268.65  5147.8  268.75  5179.5  268.77  5193.6  269.20  5250.2  273.43
  5264.3  275.62  5278.5  276.61  5405.8  283.15  5416.4  283.89  5419.9  283.89
#Mann=5,-1,0
  4642.1    0.07       0  4942.9   0.033       0  5021.9   0.033       0
  5025.9   0.033       0  5147.8    0.07       0
Bank Sta=5021.9,5025.9
Exp/Cntr=0.3,0.1

Type RM Length L Ch R = 1,2514,269,269,269
BEGIN DESCRIPTION:
E21350
END DESCRIPTION:
XS GIS Cut Line= 3
      2481284.33     13629462.07      2480707.75     13629865.32
      2480506.13     13630084.63
#Sta/Elev= 30
  4562.5  296.75  4593.0  293.98  4664.5  289.19  4679.3  287.24  4694.1  286.00
  4744.7  282.56  4765.6  280.60  4786.6  279.44  4801.4  277.89  4890.5  273.00
  4959.2  269.74  4974.1  269.68  4988.8  268.82  5013.9  268.71  5014.2  268.21
  5017.7  268.21  5017.9  268.71  5169.5  268.95  5218.2  269.01  5224.3  269.35
  5239.2  271.11  5260.1  272.42  5264.7  273.64  5275.0  273.83  5281.8  275.46
  5289.3  276.24  5296.0  278.18  5423.4  286.08  5553.9  295.40  5564.0  296.18
#Mann=8,-1,0
  4562.5    0.07       0  4890.5   0.033       0  5013.9   0.033       0
  5017.9   0.033       0  5169.5    0.07       0  5289.3    0.05       0
  5423.4    0.07       0  5553.9    0.05       0
Bank Sta=5013.9,5017.9
Exp/Cntr=0.3,0.1

Type RM Length L Ch R = 1,2245,343,343,343
BEGIN DESCRIPTION:
Stream0774 4.0
END DESCRIPTION:
XS GIS Cut Line= 3
      2481219.91     13629357.72      2480586.20     13629557.38
      2480326.40     13629890.79
#Sta/Elev= 30
  4591.9  293.23  4800.3  277.63  4838.2  272.69  4870.3  271.89  4904.0  274.80
  4929.8  273.40  4943.0  274.78  4962.2  272.80  4967.4  274.90  4994.5  273.25
  4999.8  275.05  5026.9  273.39  5037.4  274.89  5064.5  272.27  5069.7  274.81
  5096.9  273.02  5101.2  274.41  5129.2  273.09  5134.5  274.71  5205.2  275.26
  5231.6  273.72  5269.4  274.96  5283.8  274.24  5296.3  271.01  5296.6  270.51
  5300.3  271.01  5368.9  273.92  5555.7  286.16  5650.2  294.76  5679.0  296.26
#Mann=7,-1,0
  4591.9    0.07       0  4904.0   0.033       0  5101.2    0.07       0
  5296.3   0.033       0  5300.3    0.07       0  5555.7    0.05       0
  5650.2    0.07       0
Bank Sta=5296.3,5300.3
Exp/Cntr=0.3,0.1

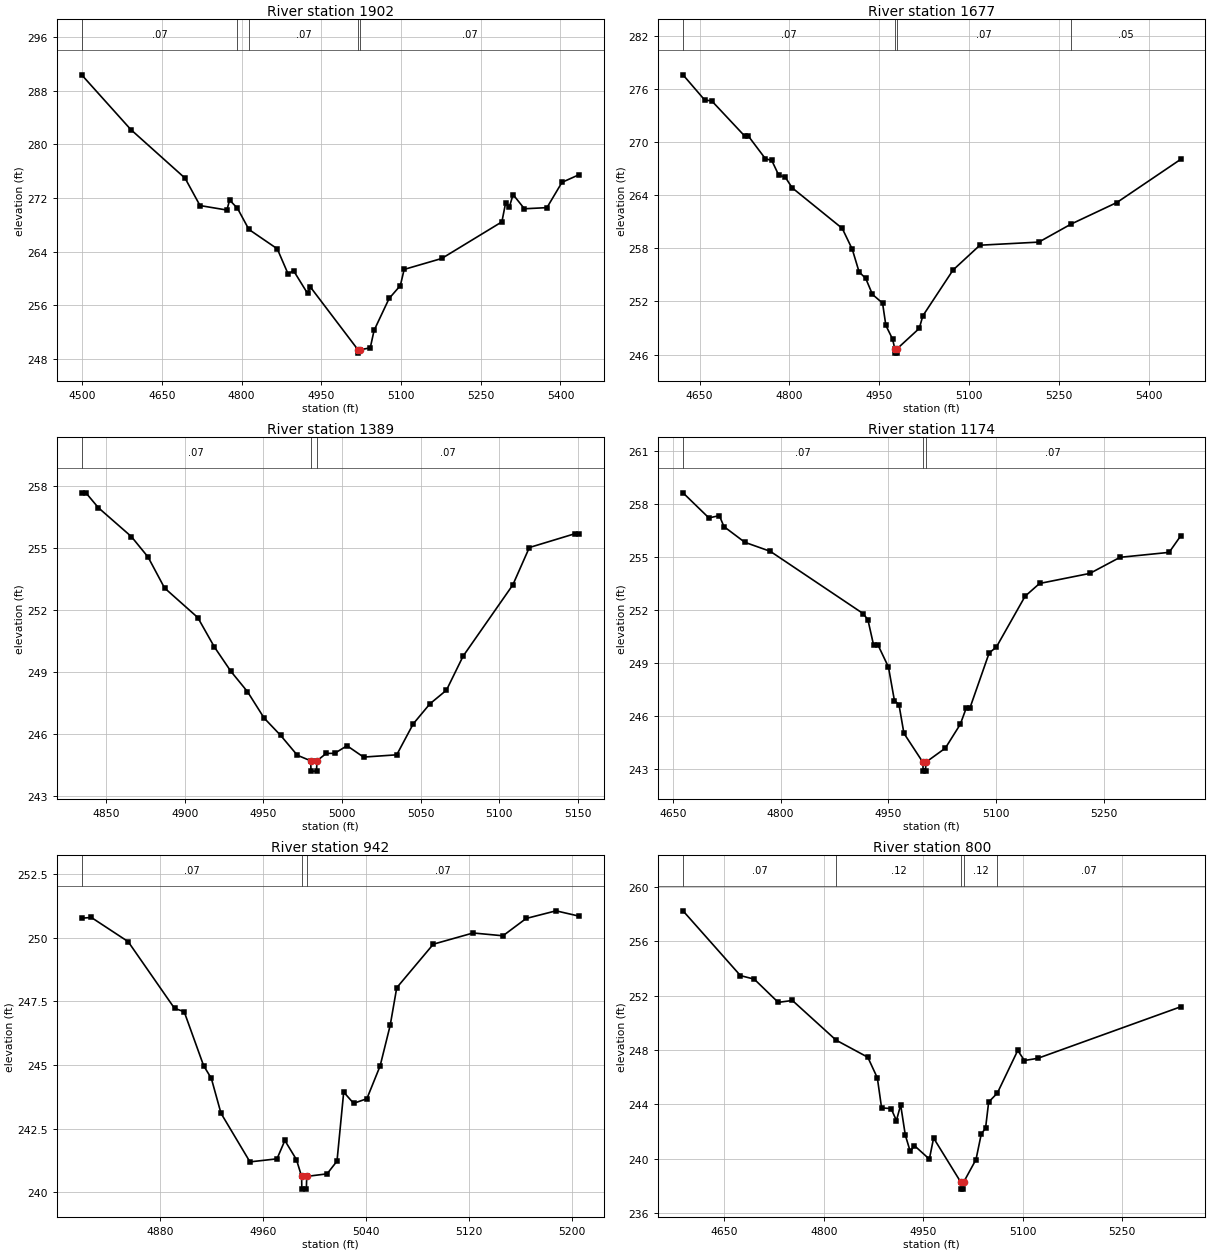
Type RM Length L Ch R = 1,1902,225,225,225
BEGIN DESCRIPTION:
Stream0774 3.0
END DESCRIPTION:
XS GIS Cut Line= 3
      2481115.69     13629145.06      2480625.26     13629244.88
      2480312.78     13629548.68
#Sta/Elev= 30
  4498.9  290.38  4591.4  282.22  4693.5  274.97  4721.6  270.89  4772.2  270.22
  4777.3  271.71  4792.1  270.48  4813.6  267.33  4867.0  264.44  4887.4  260.69
  4897.6  261.19  4924.0  257.79  4929.1  258.77  5018.9  249.39  5019.1  248.89
  5022.9  249.39  5042.0  249.68  5049.2  252.28  5077.5  257.04  5098.6  258.96
  5105.8  261.37  5176.5  263.00  5289.7  268.46  5296.6  271.23  5303.8  270.69
  5310.8  272.53  5332.1  270.41  5374.5  270.58  5402.8  274.35  5435.2  275.50
#Mann=5,-1,0
  4498.9    0.07       0  4792.1    0.12       0  4813.6    0.07       0
  5018.9    0.05       0  5022.9    0.07       0
Bank Sta=5018.9,5022.9
Exp/Cntr=0.3,0.1

Type RM Length L Ch R = 1,1677,288,288,288
BEGIN DESCRIPTION:
E21349
END DESCRIPTION:
XS GIS Cut Line= 3
      2480888.15     13628881.98      2480438.92     13629104.83
      2480276.59     13629390.68
#Sta/Elev= 30
  4622.4  277.58  4658.4  274.75  4670.6  274.62  4725.6  270.65  4731.2  270.69
  4759.9  268.11  4770.5  267.92  4782.2  266.24  4792.9  266.04  4804.5  264.83
  4888.1  260.25  4904.9  257.88  4916.2  255.34  4927.3  254.60  4938.5  252.80
  4955.4  251.81  4960.9  249.29  4972.0  247.77  4975.8  246.67  4976.0  246.17
  4979.5  246.17  4979.8  246.67  5016.6  248.96  5022.6  250.38  5073.0  255.55
  5117.8  258.35  5216.1  258.70  5269.8  260.73  5346.4  263.17  5452.6  268.03
#Mann=4,-1,0
  4622.4    0.07       0  4975.8    0.05       0  4979.8    0.07       0
  5269.8    0.05       0
Bank Sta=4975.8,4979.8
Exp/Cntr=0.3,0.1

Type RM Length L Ch R = 1,1389,215,215,215
BEGIN DESCRIPTION:
Stream0774 2.0
END DESCRIPTION:
XS GIS Cut Line= 3
      2480525.02     13628774.99      2480375.00     13628825.00
      2480324.98     13628975.05
#Sta/Elev= 30
  4834.5  257.67  4837.2  257.67  4845.1  256.95  4866.1  255.55  4876.7  254.56
  4887.2  253.06  4908.3  251.63  4918.9  250.20  4929.4  249.02  4939.9  248.04
  4950.5  246.76  4961.0  245.92  4971.6  244.96  4980.1  244.69  4980.3  244.19
  4983.8  244.19  4984.1  244.69  4990.0  245.05  4995.3  245.05  5003.2  245.42
  5013.7  244.87  5034.8  244.98  5045.3  246.48  5055.9  247.45  5066.4  248.11
  5077.0  249.76  5108.6  253.21  5119.1  255.02  5148.1  255.69  5150.8  255.69
#Mann=3,-1,0
  4834.5    0.07       0  4980.1    0.05       0  4984.1    0.07       0
Bank Sta=4980.1,4984.1
Exp/Cntr=0.3,0.1

Type RM Length L Ch R = 1,1174,232,232,232
BEGIN DESCRIPTION:
E21348
END DESCRIPTION:
XS GIS Cut Line= 3
      2480410.65     13628439.80      2480170.10     13628758.18
      2480184.20     13629050.91
#Sta/Elev= 30
  4664.2  258.62  4700.2  257.20  4714.8  257.33  4721.1  256.71  4750.2  255.82
  4785.6  255.31  4914.6  251.79  4921.4  251.44  4929.2  250.02  4935.4  250.01
  4950.0  248.76  4958.3  246.86  4964.6  246.64  4971.5  245.01  4997.9  243.37
  4998.2  242.87  5001.7  242.87  5001.9  243.37  5029.1  244.17  5049.9  245.52
  5058.1  246.43  5063.2  246.43  5090.1  249.56  5100.1  249.89  5140.1  252.77
  5160.2  253.49  5230.2  254.06  5272.1  254.97  5340.4  255.25  5356.3  256.17
#Mann=3,-1,0
  4664.2    0.07       0  4997.9    0.05       0  5001.9    0.07       0
Bank Sta=4997.9,5001.9
Exp/Cntr=0.3,0.1

Type RM Length L Ch R = 1,942,142,142,142
BEGIN DESCRIPTION:
Stream0774 1.0
END DESCRIPTION:
XS GIS Cut Line= 3
      2480175.01     13628474.99      2480025.00     13628575.00
      2479975.01     13628774.96
#Sta/Elev= 30
  4819.4  250.77  4826.9  250.80  4855.5  249.85  4891.5  247.23  4899.0  247.10
  4914.1  244.98  4920.1  244.48  4927.6  243.11  4950.1  241.20  4971.1  241.32
  4977.2  242.04  4986.2  241.29  4990.2  240.63  4990.4  240.13  4993.9  240.13
  4994.2  240.63  5010.0  240.73  5017.7  241.23  5022.9  243.94  5030.6  243.50
  5040.9  243.68  5051.2  244.97  5059.0  246.56  5064.1  248.04  5092.5  249.75
  5123.4  250.19  5146.6  250.08  5164.6  250.76  5187.8  251.06  5205.8  250.85
#Mann=3,-1,0
  4819.4    0.07       0  4990.2    0.05       0  4994.2    0.07       0
Bank Sta=4990.2,4994.2
Exp/Cntr=0.3,0.1

Type RM Length L Ch R = 1,800,311,311,311
BEGIN DESCRIPTION:
E21347
END DESCRIPTION:
XS GIS Cut Line= 3
      2480297.46     13628195.75      2479933.10     13628485.82
      2479968.48     13628768.80
#Sta/Elev= 30
  4587.5  258.24  4674.2  253.47  4695.0  253.21  4731.2  251.50  4752.6  251.64
  4818.5  248.72  4866.4  247.46  4880.8  245.94  4887.2  243.73  4901.6  243.68
  4909.6  242.80  4916.0  243.95  4923.0  241.73  4930.4  240.53  4936.8  240.95
  4959.3  239.96  4965.7  241.51  5006.9  238.25  5007.2  237.75  5010.7  237.75
  5010.9  238.25  5029.7  239.93  5037.7  241.82  5044.1  242.23  5048.8  244.16
  5061.9  244.82  5092.7  247.96  5102.8  247.22  5122.9  247.38  5338.4  251.17
#Mann=5,-1,0
  4587.5    0.07       0  4818.5    0.12       0  5006.9    0.05       0
  5010.9    0.12       0  5061.9    0.07       0
Bank Sta=5006.9,5010.9
Exp/Cntr=0.3,0.1

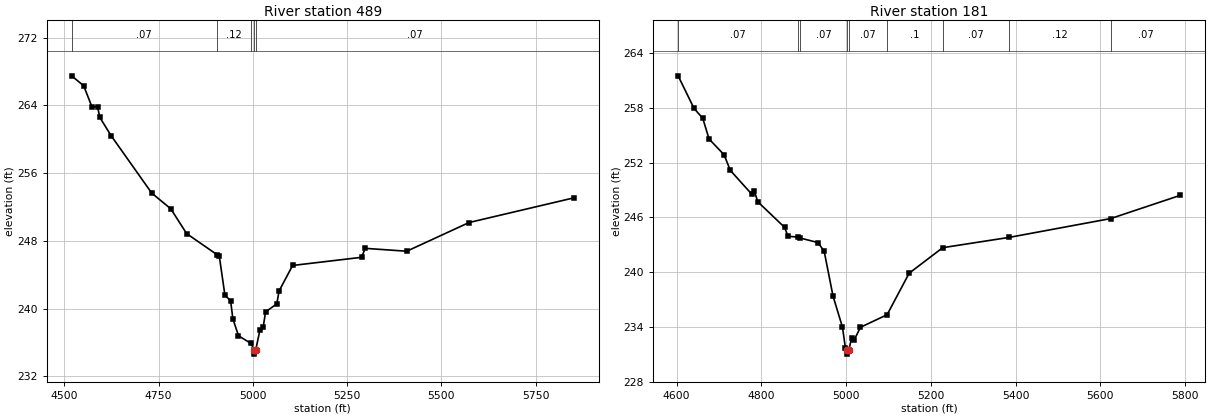
Type RM Length L Ch R = 1,489,308,308,308
BEGIN DESCRIPTION:
XS7708
END DESCRIPTION:
XS GIS Cut Line= 4
      2480238.96     13627773.55      2479891.75     13628281.34
      2479896.09     13628632.90      2480021.97     13628975.79
#Sta/Elev= 30
  4519.4  267.48  4551.4  266.30  4573.2  263.82  4588.1  263.83  4594.2  262.56
  4624.0  260.42  4731.7  253.64  4782.5  251.77  4824.4  248.85  4904.8  246.37
  4911.1  246.17  4926.0  241.55  4940.9  240.95  4947.0  238.80  4961.9  236.79
  4994.7  235.89  5003.7  235.12  5004.0  234.62  5007.7  235.12  5018.8  237.47
  5027.6  237.86  5033.7  239.60  5063.5  240.56  5069.6  242.08  5105.5  245.09
  5288.2  246.05  5298.2  247.11  5408.2  246.77  5573.6  250.16  5851.4  253.07
#Mann=5,-1,0
  4519.4    0.07       0  4904.8    0.12       0  4994.7    0.07       0
  5003.7    0.05       0  5007.7    0.07       0
Bank Sta=5003.7,5007.7
Exp/Cntr=0.3,0.1

Type RM Length L Ch R = 1,181,0,0,0
BEGIN DESCRIPTION:
E21346
END DESCRIPTION:
XS GIS Cut Line= 4
      2480138.23     13627686.43      2479770.39     13627955.24
      2479791.62     13628284.20      2479869.43     13628676.83
#Sta/Elev= 30
  4603.5  261.49  4641.0  257.93  4661.8  256.83  4676.5  254.58  4712.0  252.85
  4726.7  251.14  4776.9  248.56  4783.1  248.92  4791.5  247.71  4855.2  244.89
  4862.6  243.93  4887.0  243.84  4890.5  243.75  4933.6  243.24  4948.3  242.29
  4969.2  237.38  4991.5  233.98  4998.5  231.68  5002.7  231.53  5003.0  231.03
  5006.7  231.53  5013.2  232.82  5019.4  232.61  5034.0  233.97  5096.8  235.34
  5149.0  239.89  5228.1  242.68  5385.5  243.81  5624.9  245.87  5789.0  248.41
#Mann=9,-1,0
  4603.5    0.07       0  4887.0    0.12       0  4890.5    0.07       0
  5002.7    0.05       0  5006.7    0.07       0  5096.8     0.1       0
  5228.1    0.07       0  5385.5    0.12       0  5624.9    0.07       0
Bank Sta=5002.7,5006.7
Exp/Cntr=0.3,0.1

Chan Stop Cuts=-1