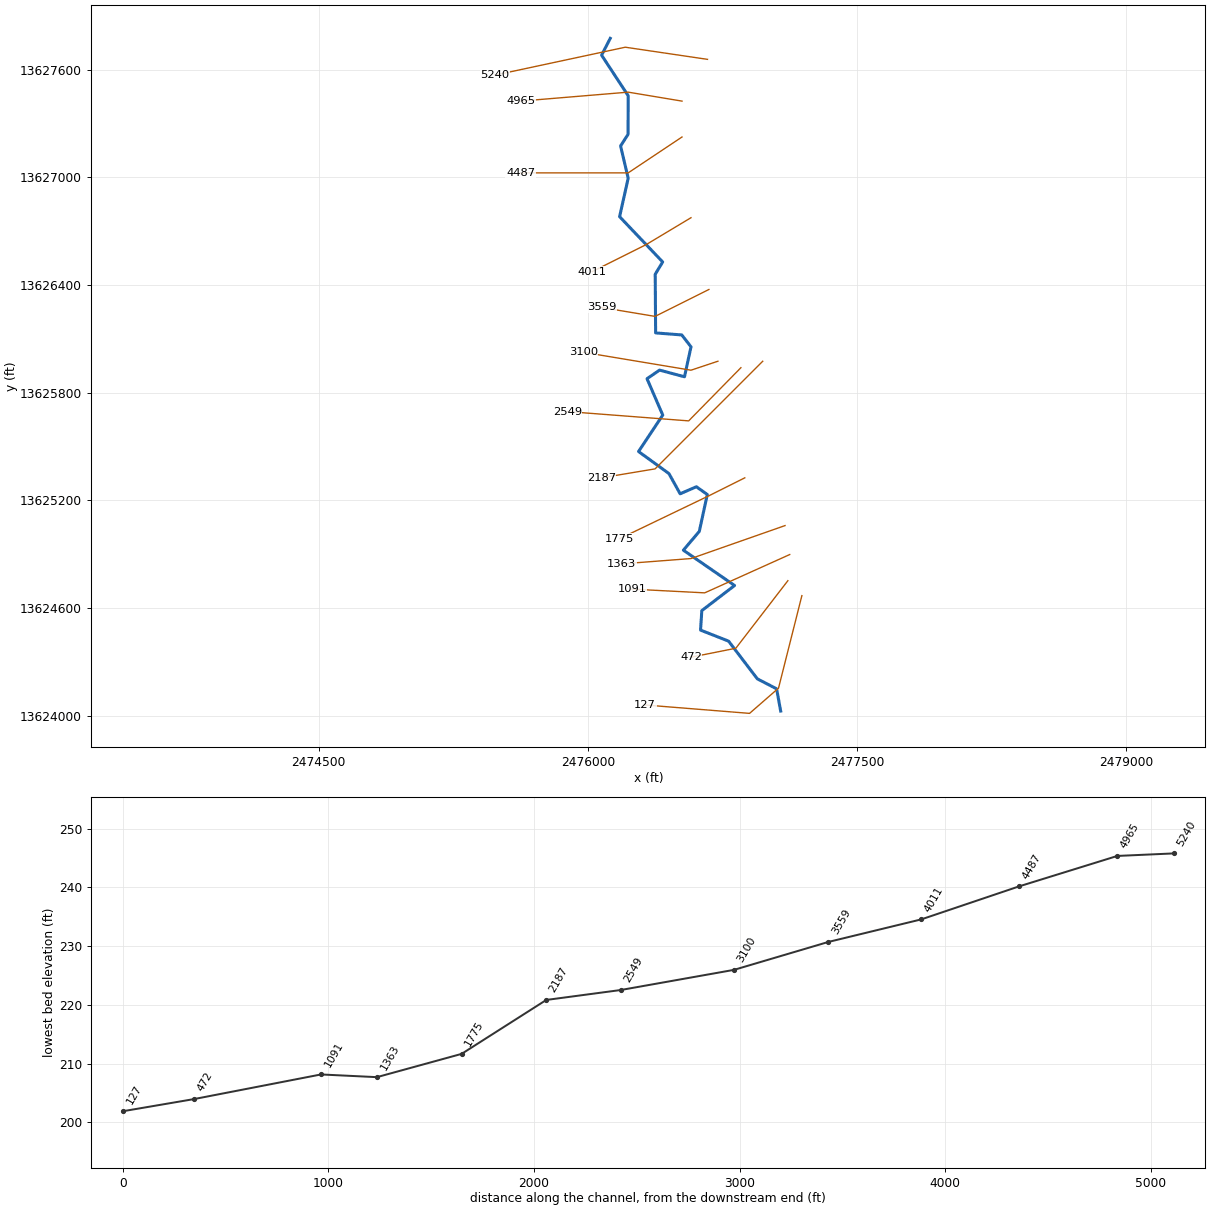
--- Stream0775.prj (project) ---

Proj Title=Stream0775 Base Level Engineering
Current Plan=p01
Default Exp/Contr=0.3,0.1
English Units
Geom File=g01
Flow File=f01
Plan File=p01
BEGIN DESCRIPTION:
Stream0775
END DESCRIPTION:

--- Stream0775.p01 (plan) ---

Plan Title=Multiple Run
Short Identifier=Multiple
Geom File=g01
Flow File=f01
Subcritical Flow
K Sum by GR= 0
Std Step Tol= 0.01
Critical Tol= 0.01
Num of Std Step Trials= 20
Max Error Tol= 0.3
Flow Tol Ratio= 0.001
Split Flow NTrial= 30
Split Flow Tol= 0.02
Split Flow Ratio= 0.02
Log Output Level= 0
Friction Slope Method= 1
Unsteady Friction Slope Method= 2
Unsteady Bridges Friction Slope Method= 1
Parabolic Critical Depth
Global Vel Dist=  1 , 1 , 1
Global Log Level= 0
CheckData=True
Encroach Param= -1, 0, 0, 0
BEGIN DESCRIPTION:
Multiple Run
END DESCRIPTION:

--- Stream0775.f01 (steady flow) ---

Flow Title=Multiple
Number of Profiles=7
Profile Names=10-year,25-year,50-year,1pct_min,100-year,1pct_plu,500-year
River Rch & RM= Stream0775,Reach-1,5240
     765    1255    1707    1126    2246    4481    3847
Boundary for River Rch & Prof#=Stream0775,Reach-1,1
Up Type=0
Dn Type=3
Dn Slope=0.005
Boundary for River Rch & Prof#=Stream0775,Reach-1,2
Up Type=0
Dn Type=3
Dn Slope=0.005
Boundary for River Rch & Prof#=Stream0775,Reach-1,3
Up Type=0
Dn Type=3
Dn Slope=0.005
Boundary for River Rch & Prof#=Stream0775,Reach-1,4
Up Type=0
Dn Type=3
Dn Slope=0.005
Boundary for River Rch & Prof#=Stream0775,Reach-1,5
Up Type=0
Dn Type=3
Dn Slope=0.005
Boundary for River Rch & Prof#=Stream0775,Reach-1,6
Up Type=0
Dn Type=3
Dn Slope=0.005
Boundary for River Rch & Prof#=Stream0775,Reach-1,7
Up Type=0
Dn Type=3
Dn Slope=0.005

--- Stream0775.g01 (geometry) ---

Geom Title=Existing Conditions

River Reach=Stream0775,Reach-1
Reach XY= 30
      2476125.00     13627775.00      2476076.74     13627681.05
      2476225.04     13627455.02      2476224.34     13627240.16
      2476182.56     13627175.00      2476224.95     13626995.04
      2476177.05     13626780.86      2476417.21     13626528.42
      2476375.66     13626459.84      2476377.91     13626132.91
      2476523.77     13626121.55      2476575.11     13626055.12
      2476538.81     13625888.35      2476399.86     13625925.52
      2476329.97     13625877.59      2476417.70     13625674.92
      2476282.76     13625471.58      2476452.14     13625348.82
      2476514.63     13625235.98      2476605.06     13625275.32
      2476665.99     13625232.12      2476621.43     13625026.47
      2476532.59     13624921.65      2476818.02     13624724.80
      2476635.42     13624584.81      2476628.36     13624476.25
      2476784.81     13624414.49      2476944.77     13624204.59
      2477052.29     13624148.93      2477075.00     13624025.00

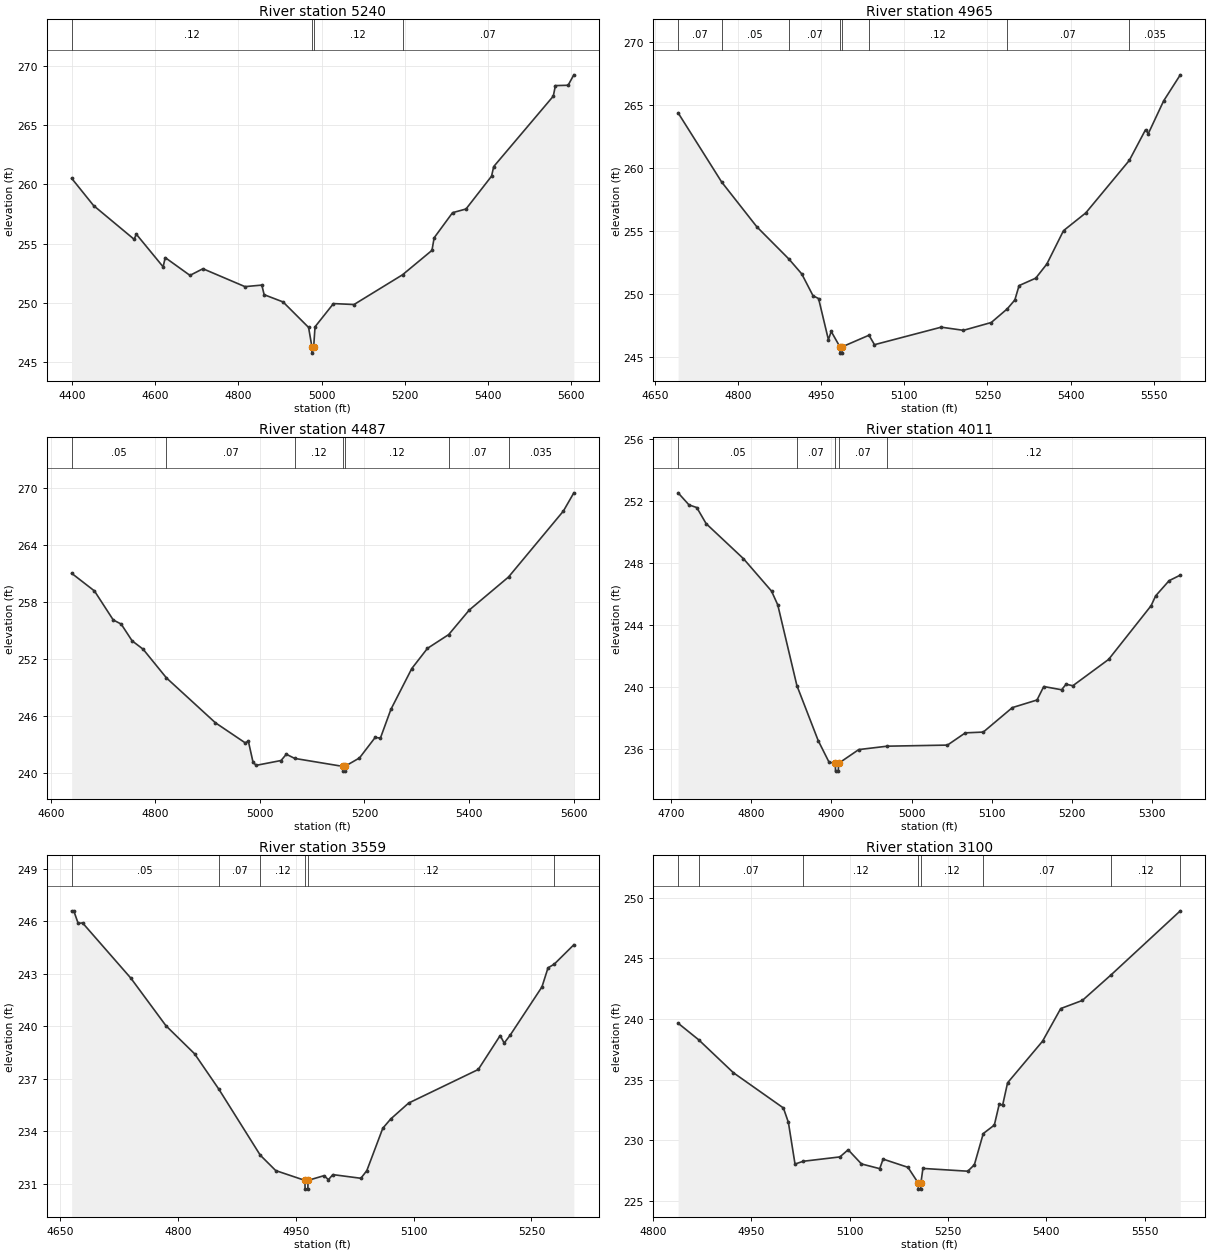
Type RM Length L Ch R = 1,5240,275,275,275
BEGIN DESCRIPTION:
XS7711
END DESCRIPTION:
XS GIS Cut Line= 3
      2476667.16     13627657.82      2476208.85     13627725.52
      2475481.55     13627569.67
#Sta/Elev= 30
  4399.3  260.52  4452.0  258.22  4549.6  255.37  4554.6  255.81  4619.2  253.05
  4624.2  253.83  4683.7  252.33  4714.9  252.89  4815.9  251.38  4856.4  251.51
  4862.0  250.70  4907.4  250.09  4968.8  247.94  4977.0  246.27  4977.3  245.77
  4981.0  246.27  4984.3  247.99  5028.6  249.95  5078.0  249.87  5194.6  252.38
  5265.4  254.44  5270.6  255.50  5314.9  257.62  5347.2  257.93  5408.6  260.70
  5413.8  261.51  5557.0  267.45  5562.1  268.34  5592.6  268.37  5606.4  269.25
#Mann=4,-1,0
  4399.3    0.12       0  4977.0    0.05       0  4981.0    0.12       0
  5194.6    0.07       0
Bank Sta=4977,4981
Exp/Cntr=0.3,0.1

Type RM Length L Ch R = 1,4965,478,478,478
BEGIN DESCRIPTION:
Stream0775 10.0
END DESCRIPTION:
XS GIS Cut Line= 3
      2476525.05     13627424.99      2476225.00     13627475.00
      2475624.96     13627425.00
#Sta/Elev= 30
  4691.7  264.41  4770.3  258.92  4833.7  255.37  4891.6  252.81  4914.8  251.63
  4935.1  249.90  4945.2  249.67  4962.9  246.41  4968.0  247.06  4983.7  245.84
  4984.0  245.34  4987.5  245.34  4987.7  245.84  5036.1  246.76  5046.1  246.01
  5166.5  247.40  5206.6  247.15  5256.8  247.77  5285.6  248.85  5299.4  249.56
  5307.0  250.70  5337.1  251.29  5357.1  252.41  5387.2  255.06  5427.4  256.47
  5506.0  260.64  5535.2  263.07  5540.3  262.77  5567.9  265.36  5598.0  267.43
#Mann=8,-1,0
  4691.7    0.07       0  4770.3    0.05       0  4891.6    0.07       0
  4983.7    0.05       0  4987.7    0.07       0  5036.1    0.12       0
  5285.6    0.07       0  5506.0   0.035       0
Bank Sta=4983.7,4987.7
Exp/Cntr=0.3,0.1

Type RM Length L Ch R = 1,4487,476,476,476
BEGIN DESCRIPTION:
Stream0775 9.0
END DESCRIPTION:
XS GIS Cut Line= 3
      2476525.01     13627225.00      2476225.00     13627025.00
      2475624.96     13627025.00
#Sta/Elev= 30
  4640.0  261.01  4683.6  259.15  4719.6  256.09  4734.7  255.66  4755.7  253.89
  4776.7  253.01  4821.4  249.98  4914.9  245.26  4972.0  243.14  4978.0  243.32
  4987.0  241.09  4993.0  240.77  5040.6  241.28  5050.6  241.94  5066.7  241.50
  5158.6  240.66  5158.8  240.16  5162.3  240.16  5162.6  240.66  5190.6  241.55
  5220.6  243.71  5230.6  243.64  5250.6  246.66  5290.6  250.97  5320.6  253.10
  5361.2  254.55  5400.6  257.14  5475.7  260.62  5580.6  267.57  5600.6  269.49
#Mann=7,-1,0
  4640.0    0.05       0  4821.4    0.07       0  5066.7    0.12       0
  5158.6    0.05       0  5162.6    0.12       0  5361.2    0.07       0
  5475.7   0.035       0
Bank Sta=5158.6,5162.6
Exp/Cntr=0.3,0.1

Type RM Length L Ch R = 1,4011,452,452,452
BEGIN DESCRIPTION:
Stream0775 8.0
END DESCRIPTION:
XS GIS Cut Line= 3
      2476575.01     13626775.00      2476325.00     13626625.00
      2476024.97     13626474.98
#Sta/Elev= 30
  4708.5  252.50  4722.1  251.72  4731.8  251.55  4743.5  250.51  4790.1  248.25
  4825.1  246.16  4832.9  245.27  4856.8  240.06  4883.4  236.51  4897.0  235.11
  4904.8  235.04  4905.0  234.54  4908.5  234.54  4908.8  235.04  4934.0  235.93
  4969.6  236.15  5044.8  236.22  5067.1  237.01  5089.5  237.06  5125.8  238.64
  5156.6  239.13  5165.0  240.00  5187.3  239.79  5192.9  240.15  5201.3  240.05
  5246.0  241.75  5299.1  245.22  5304.7  245.85  5321.5  246.83  5335.5  247.19
#Mann=5,-1,0
  4708.5    0.05       0  4856.8    0.07       0  4904.8    0.05       0
  4908.8    0.07       0  4969.6    0.12       0
Bank Sta=4904.8,4908.8
Exp/Cntr=0.3,0.1

Type RM Length L Ch R = 1,3559,459,459,459
BEGIN DESCRIPTION:
Stream0775 7.0
END DESCRIPTION:
XS GIS Cut Line= 3
      2476674.96     13626374.98      2476375.00     13626225.00
      2476075.00     13626275.00
#Sta/Elev= 30
  4664.5  246.61  4667.2  246.61  4672.8  245.89  4678.4  245.92  4739.9  242.76
  4784.6  240.04  4821.0  238.44  4852.0  236.41  4904.7  232.64  4924.4  231.76
  4961.5  231.20  4961.8  230.70  4965.3  230.70  4965.5  231.20  4985.9  231.47
  4991.5  231.24  4997.1  231.53  5032.8  231.32  5040.4  231.76  5060.7  234.18
  5070.8  234.71  5093.6  235.62  5182.3  237.54  5210.2  239.48  5215.3  239.05
  5222.9  239.50  5263.4  242.26  5271.1  243.35  5279.0  243.56  5304.0  244.67
#Mann=6,-1,0
  4664.5    0.05       0  4852.0    0.07       0  4904.7    0.12       0
  4961.5    0.05       0  4965.5    0.12       0  5279.0    0.07       0
Bank Sta=4961.5,4965.5
Exp/Cntr=0.3,0.1

Type RM Length L Ch R = 1,3100,551,551,551
BEGIN DESCRIPTION:
Stream0775 6.0
END DESCRIPTION:
XS GIS Cut Line= 3
      2476725.03     13625975.01      2476575.00     13625925.00
      2475975.02     13626025.00
#Sta/Elev= 30
  4838.1  239.65  4869.3  238.29  4922.5  235.56  4998.8  232.65  5006.4  231.46
  5016.5  228.02  5029.0  228.25  5085.0  228.61  5097.6  229.20  5117.9  228.03
  5145.8  227.64  5150.9  228.43  5188.9  227.75  5204.6  226.45  5204.9  225.95
  5208.4  225.95  5208.6  226.45  5211.7  227.66  5280.1  227.43  5290.2  227.96
  5303.8  230.54  5320.7  231.24  5328.3  233.00  5333.3  232.87  5340.9  234.73
  5394.2  238.16  5422.0  240.86  5455.0  241.53  5499.0  243.65  5604.5  248.93
#Mann=8,-1,0
  4838.1    0.05       0  4869.3    0.07       0  5029.0    0.12       0
  5204.6    0.05       0  5208.6    0.12       0  5303.8    0.07       0
  5499.0    0.12       0  5604.5   0.035       0
Bank Sta=5204.6,5208.6
Exp/Cntr=0.3,0.1

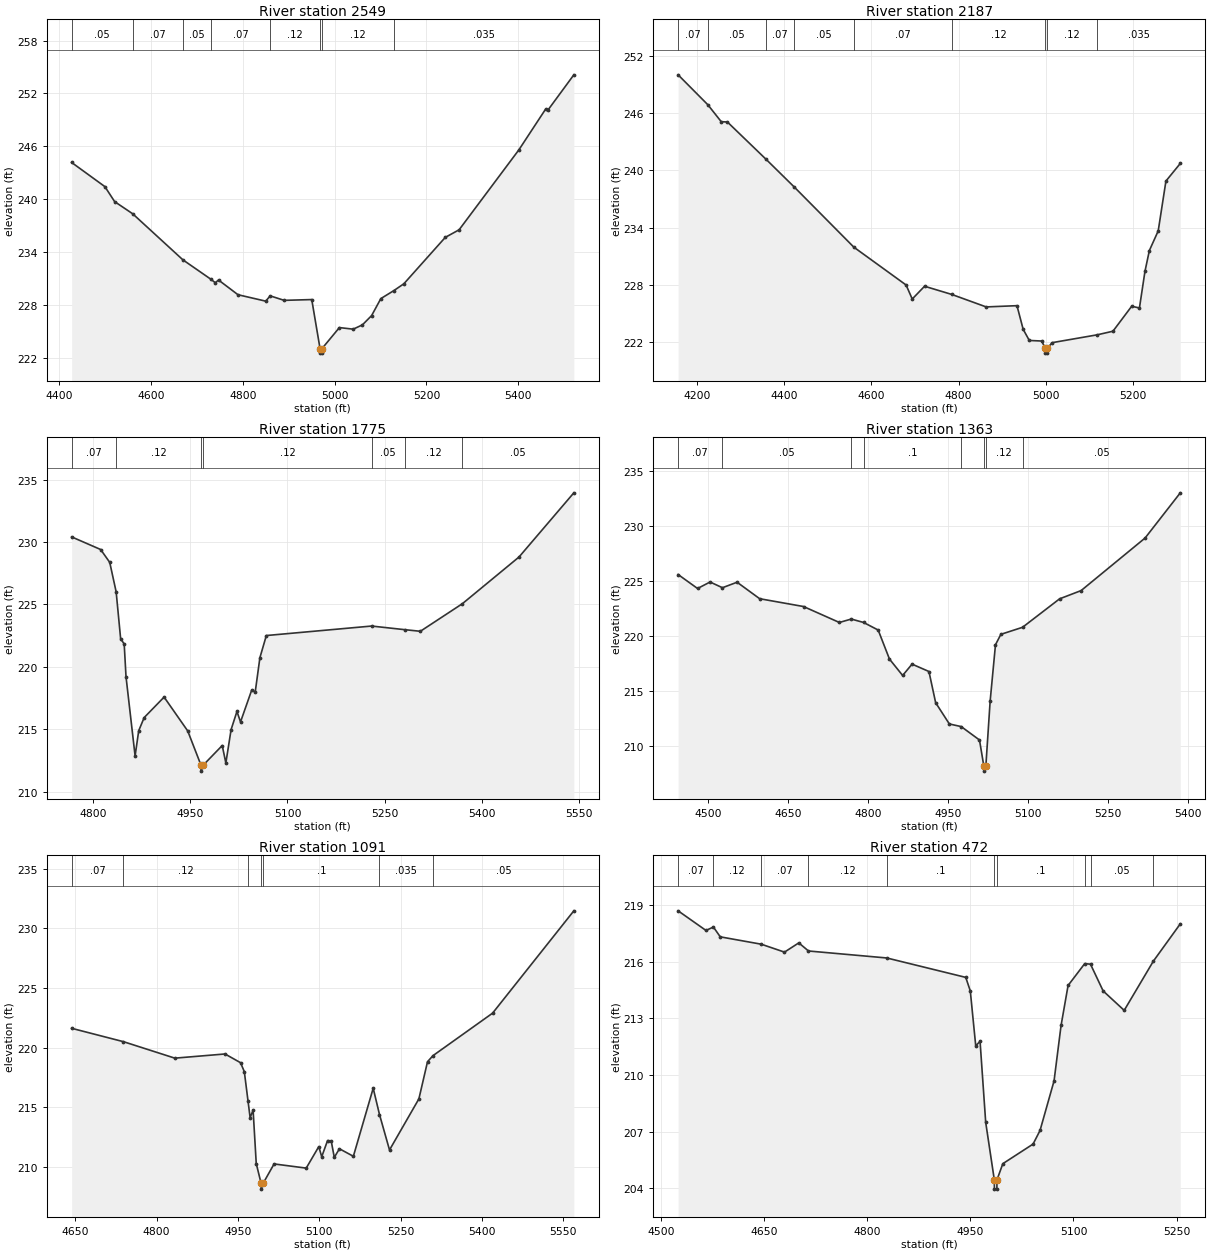
Type RM Length L Ch R = 1,2549,362,362,362
BEGIN DESCRIPTION:
E21355
END DESCRIPTION:
XS GIS Cut Line= 3
      2476853.38     13625938.99      2476562.10     13625642.51
      2475885.82     13625694.53
#Sta/Elev= 30
  4427.1  244.16  4499.5  241.42  4520.7  239.72  4560.0  238.34  4669.4  233.11
  4730.3  230.91  4740.0  230.51  4747.0  230.82  4789.4  229.15  4849.8  228.42
  4859.6  229.02  4890.0  228.51  4950.1  228.60  4968.2  223.02  4968.4  222.52
  4971.9  222.52  4972.2  223.02  5010.3  225.42  5040.4  225.24  5060.5  225.73
  5080.5  226.78  5100.6  228.71  5129.0  229.62  5150.7  230.39  5241.0  235.66
  5271.1  236.52  5401.5  245.61  5459.3  250.20  5464.3  250.09  5521.0  254.11
#Mann=8,-1,0
  4427.1    0.05       0  4560.0    0.07       0  4669.4    0.05       0
  4730.3    0.07       0  4859.6    0.12       0  4968.2    0.05       0
  4972.2    0.12       0  5129.0   0.035       0
Bank Sta=4968.2,4972.2
Exp/Cntr=0.3,0.1

Type RM Length L Ch R = 1,2187,412,412,412
BEGIN DESCRIPTION:
Stream0775 5.0
END DESCRIPTION:
XS GIS Cut Line= 3
      2476975.00     13625975.00      2476375.00     13625375.00
      2476074.97     13625324.99
#Sta/Elev= 30
  4156.3  250.04  4224.5  246.90  4255.3  245.12  4269.4  245.09  4358.5  241.16
  4423.2  238.25  4559.7  231.95  4679.6  227.98  4693.7  226.51  4722.0  227.85
  4784.4  226.99  4863.4  225.68  4934.1  225.81  4948.3  223.33  4962.4  222.16
  4990.7  222.10  4999.3  221.33  4999.5  220.83  5003.0  220.83  5003.3  221.33
  5015.0  221.93  5118.1  222.75  5154.4  223.13  5197.4  225.75  5215.2  225.57
  5227.9  229.42  5238.0  231.60  5258.3  233.66  5276.0  238.89  5309.0  240.74
#Mann=9,-1,0
  4156.3    0.07       0  4224.5    0.05       0  4358.5    0.07       0
  4423.2    0.05       0  4559.7    0.07       0  4784.4    0.12       0
  4999.3    0.05       0  5003.3    0.12       0  5118.1   0.035       0
Bank Sta=4999.3,5003.3
Exp/Cntr=0.3,0.1

Type RM Length L Ch R = 1,1775,412,412,412
BEGIN DESCRIPTION:
Stream0775 4.0
END DESCRIPTION:
XS GIS Cut Line= 3
      2476874.99     13625325.00      2476675.00     13625225.00
      2476178.83     13624986.53
#Sta/Elev= 30
  4767.3  230.41  4812.0  229.40  4826.0  228.37  4835.9  226.01  4842.8  222.26
  4848.3  221.83  4851.1  219.21  4865.1  212.87  4870.7  214.89  4879.1  215.94
  4909.8  217.58  4946.2  214.87  4966.5  212.15  4966.8  211.65  4970.5  212.15
  4999.4  213.70  5005.0  212.30  5013.1  214.98  5022.1  216.43  5027.6  215.59
  5044.7  218.12  5050.3  218.00  5057.5  220.74  5067.4  222.51  5229.7  223.27
  5280.7  222.98  5304.8  222.85  5369.6  225.06  5456.9  228.80  5541.4  233.94
#Mann=7,-1,0
  4767.3    0.07       0  4835.9    0.12       0  4966.5    0.05       0
  4970.5    0.12       0  5229.7    0.05       0  5280.7    0.12       0
  5369.6    0.05       0
Bank Sta=4966.5,4970.5
Exp/Cntr=0.3,0.1

Type RM Length L Ch R = 1,1363,272,272,272
BEGIN DESCRIPTION:
Stream0775 3.0
END DESCRIPTION:
XS GIS Cut Line= 3
      2477099.43     13625058.84      2476575.00     13624875.00
      2476189.06     13624845.39
#Sta/Elev= 30
  4443.5  225.57  4480.0  224.30  4503.5  224.89  4526.7  224.37  4554.2  224.87
  4596.6  223.37  4678.9  222.66  4746.2  221.21  4768.6  221.52  4791.7  221.21
  4819.1  220.52  4840.3  217.88  4865.0  216.39  4882.7  217.42  4914.4  216.75
  4927.0  213.91  4952.7  211.98  4975.0  211.74  5009.3  210.52  5017.3  208.19
  5017.5  207.69  5021.3  208.19  5029.3  214.06  5039.3  219.18  5049.4  220.13
  5090.1  220.77  5159.7  223.36  5200.1  224.11  5320.2  228.89  5386.3  233.00
#Mann=8,-1,0
  4443.5    0.07       0  4526.7    0.05       0  4768.6    0.12       0
  4791.7     0.1       0  4975.0    0.12       0  5017.3    0.05       0
  5021.3    0.12       0  5090.1    0.05       0
Bank Sta=5017.3,5021.3
Exp/Cntr=0.3,0.1

Type RM Length L Ch R = 1,1091,619,619,619
BEGIN DESCRIPTION:
Stream0775 2.0
END DESCRIPTION:
XS GIS Cut Line= 3
      2477125.51     13624897.39      2476651.56     13624683.85
      2476245.32     13624704.69
#Sta/Elev= 30
  4643.2  221.62  4738.8  220.50  4833.6  219.12  4926.2  219.47  4954.8  218.74
  4961.8  217.99  4968.6  215.54  4972.5  214.14  4978.0  214.77  4983.8  210.29
  4992.7  208.65  4993.0  208.15  4996.7  208.65  5016.7  210.26  5076.0  209.91
  5099.2  211.71  5104.6  210.86  5115.4  212.22  5122.3  212.14  5127.8  210.81
  5137.3  211.53  5163.0  210.90  5199.6  216.60  5211.2  214.40  5229.7  211.43
  5283.9  215.71  5299.8  218.82  5309.9  219.33  5419.9  222.89  5569.8  231.46
#Mann=7,-1,0
  4643.2    0.07       0  4738.8    0.12       0  4968.6     0.1       0
  4992.7    0.05       0  4996.7     0.1       0  5211.2   0.035       0
  5309.9    0.05       0
Bank Sta=4992.7,4996.7
Exp/Cntr=0.3,0.1

Type RM Length L Ch R = 1,472,345,345,345
BEGIN DESCRIPTION:
Stream0775 1.0
END DESCRIPTION:
XS GIS Cut Line= 3
      2477115.11     13624751.57      2476825.00     13624375.00
      2476575.01     13624325.00
#Sta/Elev= 30
  4525.1  218.71  4565.6  217.67  4576.4  217.85  4586.4  217.33  4646.0  216.94
  4679.8  216.52  4700.6  217.01  4714.7  216.58  4828.5  216.21  4943.4  215.18
  4950.0  214.46  4957.9  211.55  4964.2  211.79  4972.4  207.49  4984.9  204.45
  4985.1  203.95  4988.6  203.95  4988.9  204.45  4997.3  205.30  5041.3  206.34
  5051.4  207.06  5071.8  209.69  5082.0  212.63  5092.2  214.75  5116.4  215.91
  5124.8  215.88  5143.2  214.46  5173.8  213.43  5216.2  216.04  5255.4  218.02
#Mann=10,-1,0
  4525.1    0.07       0  4576.4    0.12       0  4646.0    0.07       0
  4714.7    0.12       0  4828.5     0.1       0  4984.9    0.05       0
  4988.9     0.1       0  5116.4    0.12       0  5124.8    0.05       0
  5216.2    0.12       0
Bank Sta=4984.9,4988.9
Exp/Cntr=0.3,0.1

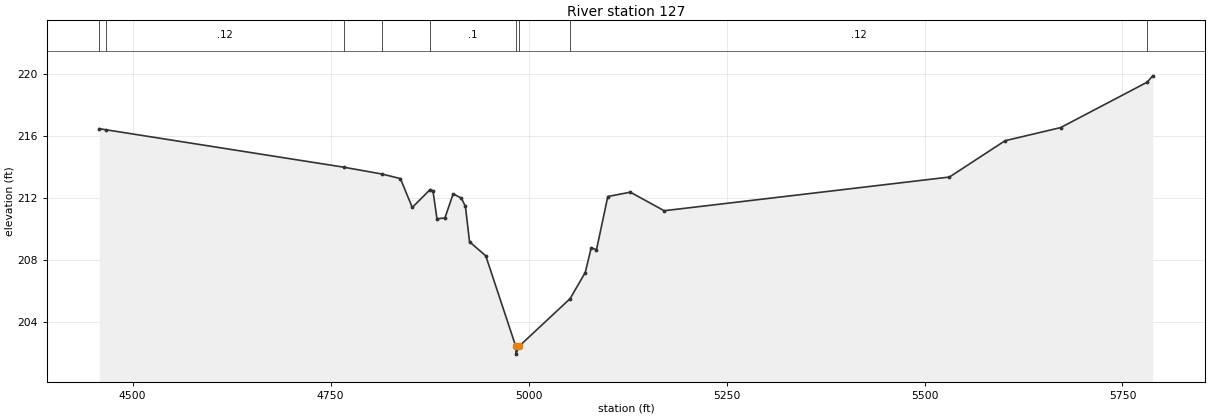
Type RM Length L Ch R = 1,127,0,0,0
BEGIN DESCRIPTION:
XS7710
END DESCRIPTION:
XS GIS Cut Line= 4
      2477193.24     13624668.26      2477063.02     13624152.60
      2476901.56     13624011.98      2476319.09     13624058.78
#Sta/Elev= 30
  4457.9  216.48  4466.4  216.41  4766.4  213.99  4815.4  213.54  4838.2  213.25
  4853.2  211.38  4875.7  212.54  4879.3  212.46  4884.4  210.65  4894.4  210.70
  4904.8  212.26  4915.1  211.99  4920.3  211.45  4925.5  209.16  4946.0  208.25
  4983.9  202.39  4984.2  201.89  4987.9  202.39  5052.5  205.48  5071.6  207.17
  5079.2  208.78  5085.8  208.64  5100.1  212.09  5128.5  212.37  5171.3  211.17
  5531.5  213.35  5601.7  215.70  5671.9  216.55  5781.2  219.49  5788.2  219.90
#Mann=9,-1,0
  4457.9    0.07       0  4466.4    0.12       0  4766.4    0.07       0
  4815.4    0.12       0  4875.7     0.1       0  4983.9    0.05       0
  4987.9     0.1       0  5052.5    0.12       0  5781.2   0.035       0
Bank Sta=4983.9,4987.9
Exp/Cntr=0.3,0.1

Chan Stop Cuts=-1