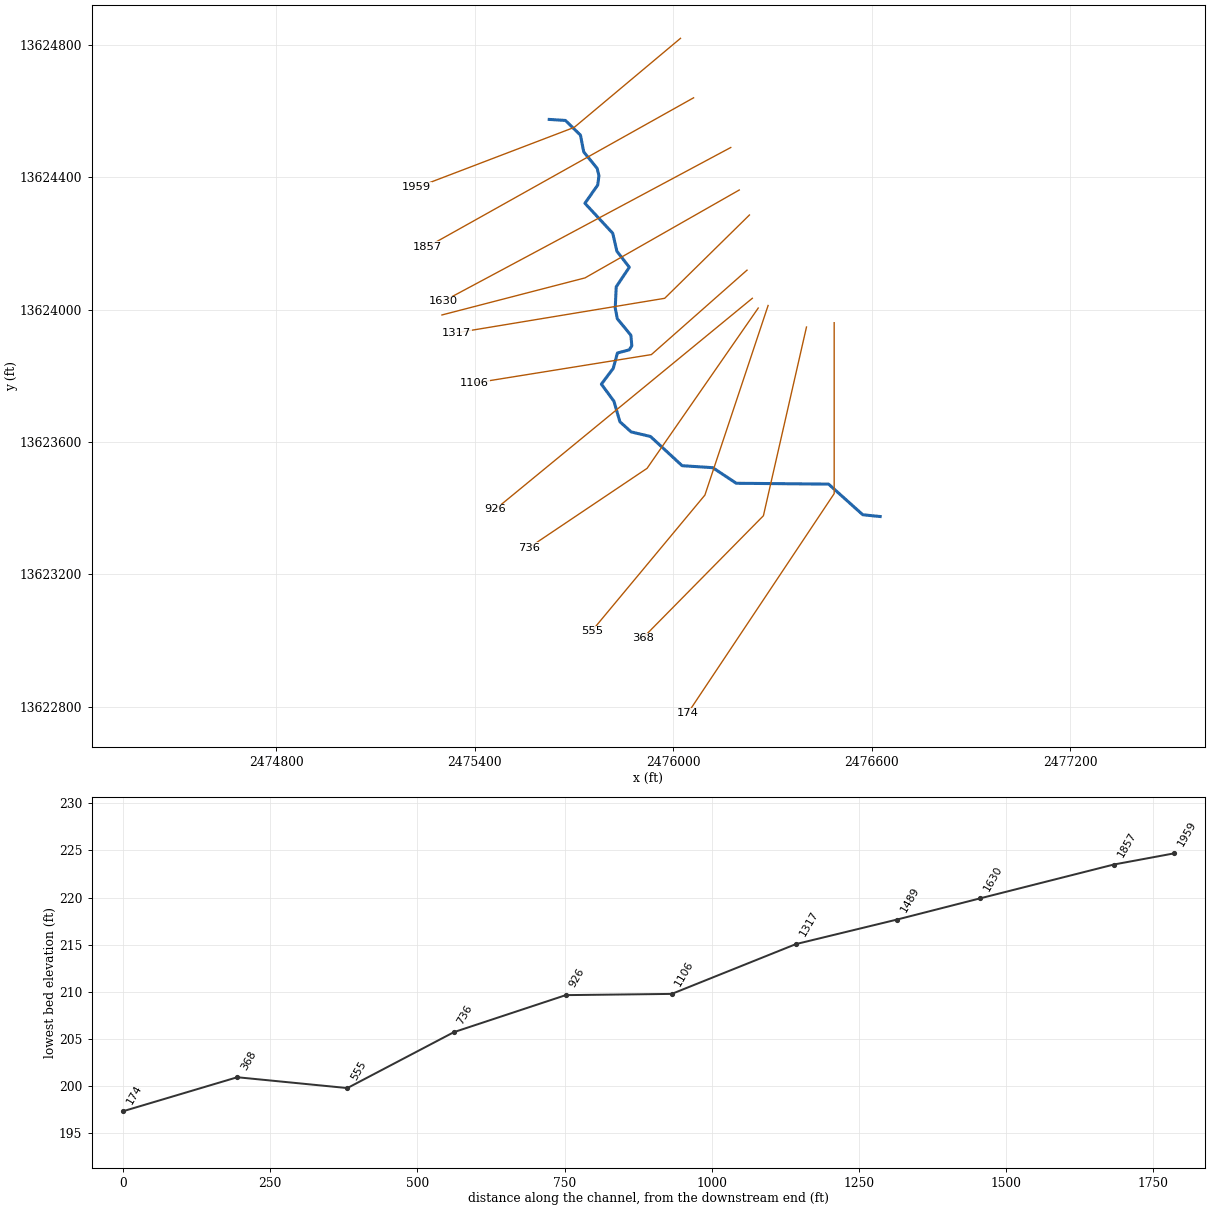
--- Stream0776.prj (project) ---

Proj Title=Stream0776 Base Level Engineering
Current Plan=p01
Default Exp/Contr=0.3,0.1
English Units
Geom File=g01
Flow File=f01
Plan File=p01
Y Axis Title=Elevation
X Axis Title(PF)=Main Channel Distance
X Axis Title(XS)=Station
BEGIN DESCRIPTION:
Stream0776
END DESCRIPTION:
DSS Export Rating Curves= 0
DSS Export Rating Curve Sorted= 0
DSS Export Volume Flow Curves= 0
DXF OffsetX= 0
DXF OffsetY= 0
DXF ScaleX= 1
DXF ScaleY= 10

--- Stream0776.p01 (plan) ---

Plan Title=Multiple Run
Short Identifier=Multiple
Geom File=g01
Flow File=f01
Subcritical Flow
K Sum by GR= 0
Std Step Tol= 0.01
Critical Tol= 0.01
Num of Std Step Trials= 20
Max Error Tol= 0.3
Flow Tol Ratio= 0.001
Split Flow NTrial= 30
Split Flow Tol= 0.02
Split Flow Ratio= 0.02
Log Output Level= 0
Friction Slope Method= 1
Unsteady Friction Slope Method= 2
Unsteady Bridges Friction Slope Method= 1
Parabolic Critical Depth
Global Vel Dist=  1 , 1 , 1
Global Log Level= 0
CheckData=True
Encroach Param= -1, 0, 0, 0
BEGIN DESCRIPTION:
Multiple Run
END DESCRIPTION:

--- Stream0776.f01 (steady flow) ---

Flow Title=Multiple
Number of Profiles=7
Profile Names=10-year,25-year,50-year,1pct_min,100-year,1pct_plu,500-year
River Rch & RM= Stream0776,Reach-1,1959
     393     620     821     529    1055    2105    1721
Boundary for River Rch & Prof#=Stream0776,Reach-1,1
Up Type=0
Dn Type=3
Dn Slope=0.005
Boundary for River Rch & Prof#=Stream0776,Reach-1,2
Up Type=0
Dn Type=3
Dn Slope=0.005
Boundary for River Rch & Prof#=Stream0776,Reach-1,3
Up Type=0
Dn Type=3
Dn Slope=0.005
Boundary for River Rch & Prof#=Stream0776,Reach-1,4
Up Type=0
Dn Type=3
Dn Slope=0.005
Boundary for River Rch & Prof#=Stream0776,Reach-1,5
Up Type=0
Dn Type=3
Dn Slope=0.005
Boundary for River Rch & Prof#=Stream0776,Reach-1,6
Up Type=0
Dn Type=3
Dn Slope=0.005
Boundary for River Rch & Prof#=Stream0776,Reach-1,7
Up Type=0
Dn Type=3
Dn Slope=0.005

--- Stream0776.g01 (geometry) ---

Geom Title=Existing Conditions
Program Version=4.10

River Reach=Stream0776      ,Reach-1
Reach XY= 30
        2475625.       13624575.      2475673.97     13624571.86
      2475719.32     13624527.52      2475729.24     13624476.75
      2475769.64     13624427.19      2475775.22      13624404.8
      2475771.39     13624376.63      2475732.83      13624321.6
      2475816.84     13624231.05      2475829.45     13624176.65
      2475866.96     13624128.32      2475827.37     13624069.11
      2475824.43     13624004.95      2475830.74     13623972.64
      2475871.73     13623922.92      2475874.51     13623891.12
      2475866.87      13623878.7      2475831.08     13623869.23
      2475818.52     13623823.02      2475782.49     13623775.03
      2475820.53     13623723.32      2475838.46     13623661.44
      2475872.46     13623630.75      2475931.02     13623616.81
       2476026.5     13623528.62      2476119.02     13623522.64
      2476190.22     13623475.52      2476469.15     13623472.94
      2476572.49     13623380.33        2476625.       13623375.

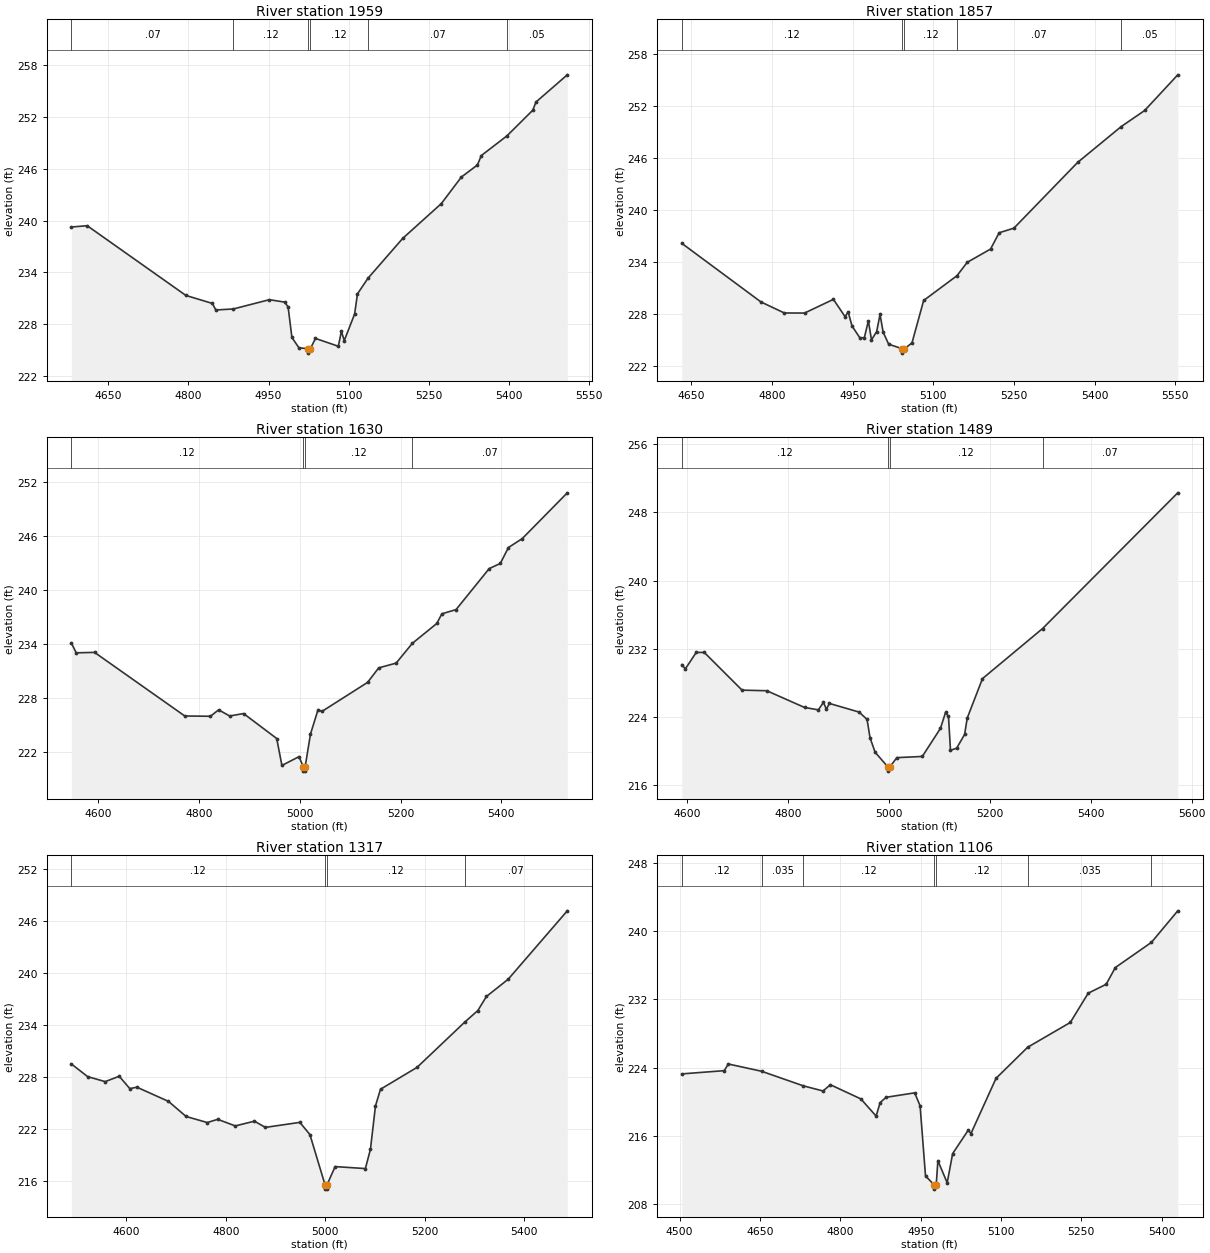
Type RM Length L Ch R = 1 ,1959    ,102,102,102
BEGIN DESCRIPTION:
XS7717
END DESCRIPTION:
XS GIS Cut Line= 3
      2476021.61     13624820.05      2475700.43     13624550.95
      2475224.73     13624369.32
#Sta/Elev= 30
  4580.8  239.25  4610.5   239.4  4795.2  231.35  4844.7  230.43  4851.2  229.67
  4884.1  229.79  4951.4  230.86    4980  230.58  4986.5  230.02  4993.6   226.5
  5006.7  225.31  5024.1  225.19  5024.3  224.69  5028.1  225.19  5037.7  226.39
  5080.5  225.48  5086.2  227.21  5091.6  226.14    5111  229.21  5116.3  231.53
  5135.9  233.33  5201.2  237.95  5273.2  241.95  5310.8  245.02  5340.8  246.41
  5348.1   247.5    5396  249.77  5444.5  252.74  5450.4  253.68    5509  256.82
#Mann= 6 ,-1 , 0
  4580.8     .07       0  4884.1     .12       0  5024.1     .05       0
  5028.1     .12       0  5135.9     .07       0    5396     .05       0
Bank Sta=5024.1,5028.1
XS Rating Curve= 0 ,0
Exp/Cntr=0.3,0.1

Type RM Length L Ch R = 1 ,1857    ,227,227,227
BEGIN DESCRIPTION:
E21360
END DESCRIPTION:
XS GIS Cut Line= 2
      2476061.16     13624640.36      2475256.49     13624189.85
#Sta/Elev= 30
  4632.2  236.17  4779.4  229.41  4822.8  228.14  4860.4  228.13  4914.1  229.71
  4935.8  227.71  4941.5  228.26  4948.7  226.64  4963.2  225.28  4971.6  225.29
  4979.1  227.23  4984.9  225.04  4994.5  225.99  5000.8  227.97  5006.6  225.93
  5016.8  224.54  5042.2  224.01  5042.5  223.51  5046.2  224.01  5060.2  224.69
  5081.9  229.58  5143.9  232.44  5162.9  233.98  5206.3  235.51  5222.3  237.39
  5249.7  237.92  5368.4  245.51  5449.2  249.63  5492.9  251.49  5554.4   255.6
#Mann= 5 ,-1 , 0
  4632.2     .12       0  5042.2     .05       0  5046.2     .12       0
  5143.9     .07       0  5449.2     .05       0
Bank Sta=5042.2,5046.2
XS Rating Curve= 0 ,0
Exp/Cntr=0.3,0.1

Type RM Length L Ch R = 1 ,1630    ,141,141,141
BEGIN DESCRIPTION:
XS7716
END DESCRIPTION:
XS GIS Cut Line= 2
      2476173.52     13624490.19      2475305.45     13624025.77
#Sta/Elev= 30
  4546.4  234.14  4556.1  233.05  4592.5   233.1  4771.6  226.04  4822.5  226.01
  4838.8  226.72  4860.7  226.04  4888.3  226.31  4954.1  223.54  4964.4  220.55
  4998.4  221.53  5006.6  220.42  5006.9  219.92  5010.4  219.92  5010.6  220.42
  5021.1  224.03  5036.2  226.75  5043.7  226.54  5134.5  229.77  5156.5  231.38
  5191.2  231.91  5223.4  234.11  5271.9  236.31  5281.9  237.38  5310.1  237.85
  5375.9   242.4  5397.9  242.97  5414.1  244.74  5441.7  245.74  5530.9  250.81
#Mann= 4 ,-1 , 0
  4546.4     .12       0  5006.6     .05       0  5010.6     .12       0
  5223.4     .07       0
Bank Sta=5006.6,5010.6
XS Rating Curve= 0 ,0
Exp/Cntr=0.3,0.1

Type RM Length L Ch R = 1 ,1489    ,172,172,172
BEGIN DESCRIPTION:
E21359
END DESCRIPTION:
XS GIS Cut Line= 3
       2476199.2     13624361.73      2475733.07     13624096.11
      2475300.73     13623984.12
#Sta/Elev= 30
  4589.4  230.15  4596.4  229.65    4618  231.58  4633.9  231.58  4708.8  227.16
  4757.8  227.09  4832.7  225.13  4860.1  224.85  4870.2  225.73  4875.9  224.93
    4882   225.6  4940.8  224.59  4956.6  223.73  4962.5  221.58  4972.5  219.89
  4997.8  218.17  4998.1  217.67  5001.8  218.17  5015.7  219.25  5066.1  219.39
  5102.1  222.68  5112.2  224.55    5118  224.09    5122  220.11  5134.2  220.36
    5150  221.97  5155.2  223.89  5185.4  228.51  5304.4  234.37  5572.5  250.28
#Mann= 4 ,-1 , 0
  4589.4     .12       0  4997.8     .05       0  5001.8     .12       0
  5304.4     .07       0
Bank Sta=4997.8,5001.8
XS Rating Curve= 0 ,0
Exp/Cntr=0.3,0.1

Type RM Length L Ch R = 1 ,1317    ,211,211,211
BEGIN DESCRIPTION:
XS7715
END DESCRIPTION:
XS GIS Cut Line= 3
      2476229.98     13624286.23      2475973.87     13624034.46
      2475344.57      13623930.3
#Sta/Elev= 30
  4489.3   229.5    4522  228.04  4557.3  227.46  4585.6  228.08  4606.9  226.65
    4621  226.82  4684.6  225.18    4720  223.44  4762.5  222.74  4783.6  223.11
  4818.9  222.35  4857.4   222.9  4879.3  222.18  4948.7  222.76  4968.9  221.35
  4999.3  215.56  4999.6  215.06  5003.1  215.06  5003.3  215.56  5019.6  217.66
  5080.4  217.43  5090.6  219.66  5100.7  224.66  5110.8  226.58  5184.4  229.11
  5279.7   234.3  5306.5  235.66  5323.7  237.28  5367.5  239.27  5486.3  247.16
#Mann= 4 ,-1 , 0
  4489.3     .12       0  4999.3     .05       0  5003.3     .12       0
  5279.7     .07       0
Bank Sta=4999.3,5003.3
XS Rating Curve= 0 ,0
Exp/Cntr=0.3,0.1

Type RM Length L Ch R = 1 ,1106    ,180,180,180
BEGIN DESCRIPTION:
E21358
END DESCRIPTION:
XS GIS Cut Line= 3
      2476222.69     13624119.58      2475933.59     13623864.34
      2475399.91     13623778.43
#Sta/Elev= 30
    4504  223.26  4583.3  223.64  4590.8  224.42  4652.9  223.57    4731  221.86
  4767.7  221.26  4781.5  221.99  4838.4  220.33  4866.9  218.32  4874.4   219.9
  4885.4  220.52  4938.9  221.04    4949  219.52  4959.1  211.32  4975.1  210.27
  4975.3  209.77  4979.1  210.27  4982.2   213.1  4999.6  210.51  5009.8  213.93
  5038.9  216.67    5044  216.28  5090.8  222.74  5149.9  226.38  5229.5  229.28
    5263  232.71  5296.5  233.75  5313.6  235.71  5381.1  238.66  5430.2  242.35
#Mann= 7 ,-1 , 0
    4504     .12       0  4652.9    .035       0    4731     .12       0
  4975.1     .05       0  4979.1     .12       0  5149.9    .035       0
  5381.1     .07       0
Bank Sta=4975.1,4979.1
XS Rating Curve= 0 ,0
Exp/Cntr=0.3,0.1

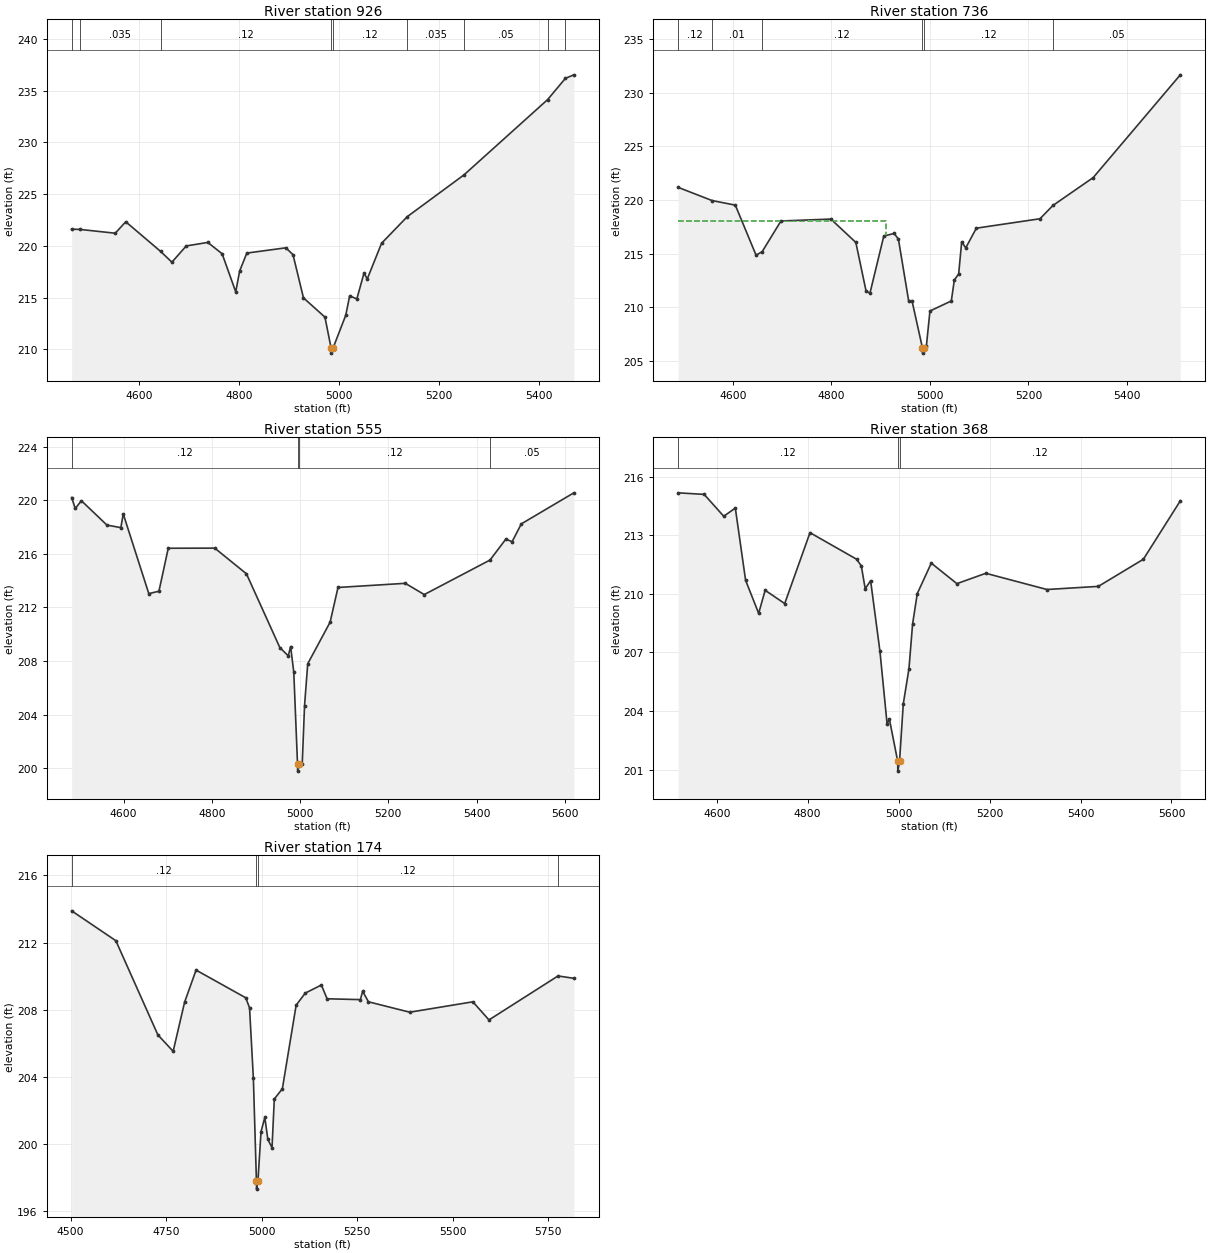
Type RM Length L Ch R = 1 ,926     ,190,190,190
BEGIN DESCRIPTION:
XS7714
END DESCRIPTION:
XS GIS Cut Line= 2
      2476238.66     13624034.49      2475461.68     13623396.41
#Sta/Elev= 30
    4465  221.62  4481.2   221.6  4552.3  221.23  4573.3  222.34  4642.9  219.48
  4665.7  218.43  4694.4     220  4737.5  220.34  4766.2  219.25  4793.5  215.56
  4801.3  217.57  4815.7  219.31  4893.9  219.82  4908.2  219.15  4929.1  214.98
  4972.1  213.12  4984.4  210.14  4984.7  209.64  4988.4  210.14  5013.7  213.29
  5021.6  215.17    5036  214.88  5050.3  217.38  5056.8  216.81  5085.5  220.26
  5136.9  222.83  5250.5  226.87  5417.8  234.14  5453.5   236.2  5470.4  236.54
#Mann= 9 ,-1 , 0
    4465     .12       0  4481.2    .035       0  4642.9     .12       0
  4984.4     .05       0  4988.4     .12       0  5136.9    .035       0
  5250.5     .05       0  5417.8    .035       0  5453.5     .05       0
Bank Sta=4984.4,4988.4
XS Rating Curve= 0 ,0
Exp/Cntr=0.3,0.1

Type RM Length L Ch R = 1 ,736     ,181,181,181
BEGIN DESCRIPTION:
E21357
END DESCRIPTION:
XS GIS Cut Line= 3
      2476256.51     13624004.97      2475920.57     13623520.59
      2475563.82     13623281.02
#Sta/Elev= 30
  4488.9  221.18  4557.6  219.95    4605  219.52  4647.1  214.85  4659.5  215.18
  4697.6  218.04  4798.9  218.22  4849.6  216.04  4870.5  211.47  4878.3  211.32
  4906.3  216.63  4927.3  216.88    4936  216.35    4957  210.53  4963.5  210.61
  4984.7  206.21  4984.9  205.71  4988.7  206.21  4992.8   206.4    5000  209.64
  5043.4  210.58  5049.5  212.54  5058.3   213.1  5064.4   216.1  5072.6  215.53
  5094.2  217.37  5223.3  218.25  5249.6  219.49  5331.3  222.09  5508.1  231.68
#Mann= 6 ,-1 , 0
  4488.9     .12       0  4557.6     .01       0  4659.5     .12       0
  4984.7     .05       0  4988.7     .12       0  5249.6     .05       0
#XS Ineff= 2 , 0
       0    4911     218               0
Permanent Ineff=
       F       F
Bank Sta=4984.7,4988.7
XS Rating Curve= 0 ,0
Exp/Cntr=0.3,0.1

Type RM Length L Ch R = 1 ,555     ,187,187,187
BEGIN DESCRIPTION:
XS7713
END DESCRIPTION:
XS GIS Cut Line= 3
      2476286.37     13624012.74       2476095.4     13623439.84
      2475753.57     13623028.79
#Sta/Elev= 30
  4482.1  220.21  4490.3  219.39  4504.2  219.97  4562.1  218.15  4593.7  217.96
    4599  218.99    4657  213.03    4680  213.21  4701.1  216.42  4806.5  216.43
  4878.4  214.51  4954.1     209  4973.2  208.38  4978.5  209.08  4985.7  207.16
  4994.2  200.27  4994.5  199.77  4998.2  200.27  5004.8  200.28  5010.1  204.67
  5017.3  207.79  5068.1   210.9  5085.9  213.49  5238.5   213.8  5281.5  212.96
  5430.6  215.54  5466.4   217.1  5480.7  216.91  5501.5  218.24  5620.6  220.56
#Mann= 4 ,-1 , 0
  4482.1     .12       0  4994.2     .05       0  4998.2     .12       0
  5430.6     .05       0
Bank Sta=4994.2,4998.2
XS Rating Curve= 0 ,0
Exp/Cntr=0.3,0.1

Type RM Length L Ch R = 1 ,368     ,194,194,194
BEGIN DESCRIPTION:
E21356
END DESCRIPTION:
XS GIS Cut Line= 3
      2476402.35     13623947.69      2476272.14     13623377.36
      2475907.55     13623007.57
#Sta/Elev= 30
  4515.1  215.17  4572.4  215.09  4615.4  213.97  4640.9  214.39  4663.5  210.69
  4692.2     209  4706.5  210.18  4749.5   209.5  4805.1  213.13  4907.6  211.77
  4917.9  211.43  4926.5  210.26  4938.4  210.67  4958.9  207.06  4974.6  203.34
  4979.7  203.58    4998  201.42  4998.2  200.92    5002  201.42  5010.2  204.36
  5022.7  206.16  5030.7  208.45    5041  210.01  5071.8  211.57  5128.1  210.52
  5191.7  211.05  5326.1  210.22  5439.2  210.38  5538.2  211.77  5619.4  214.76
#Mann= 3 ,-1 , 0
  4515.1     .12       0    4998     .05       0    5002     .12       0
Bank Sta=4998,5002
XS Rating Curve= 0 ,0
Exp/Cntr=0.3,0.1

Type RM Length L Ch R = 1 ,174     ,0,0,0
BEGIN DESCRIPTION:
XS7712
END DESCRIPTION:
XS GIS Cut Line= 3
      2476486.02     13623960.72      2476486.02     13623444.18
      2476043.34     13622780.15
#Sta/Elev= 30
  4502.8  213.89  4618.5  212.11  4728.5   206.5  4768.5  205.52  4798.5  208.45
  4828.5  210.36  4958.5  208.71  4968.5  208.11  4978.5  203.91  4986.5  197.81
  4986.8  197.31  4990.5  197.81  4998.5  200.73  5008.5  201.58  5016.4  200.27
  5027.3  199.78  5033.3  202.68  5054.4  203.29  5090.5  208.27  5114.4  208.99
  5156.5  209.47  5171.5  208.65  5258.6   208.6  5264.6   209.1  5279.7  208.47
  5387.8  207.85  5553.1  208.47  5595.2  207.39    5776  210.01  5817.4  209.87
#Mann= 4 ,-1 , 0
  4502.8     .12       0  4986.5     .05       0  4990.5     .12       0
    5776     .05       0
Bank Sta=4986.5,4990.5
XS Rating Curve= 0 ,0
Exp/Cntr=0.3,0.1

Chan Stop Cuts=-1
Use User Specified Reach Order=0
Composite Channel Slope=5