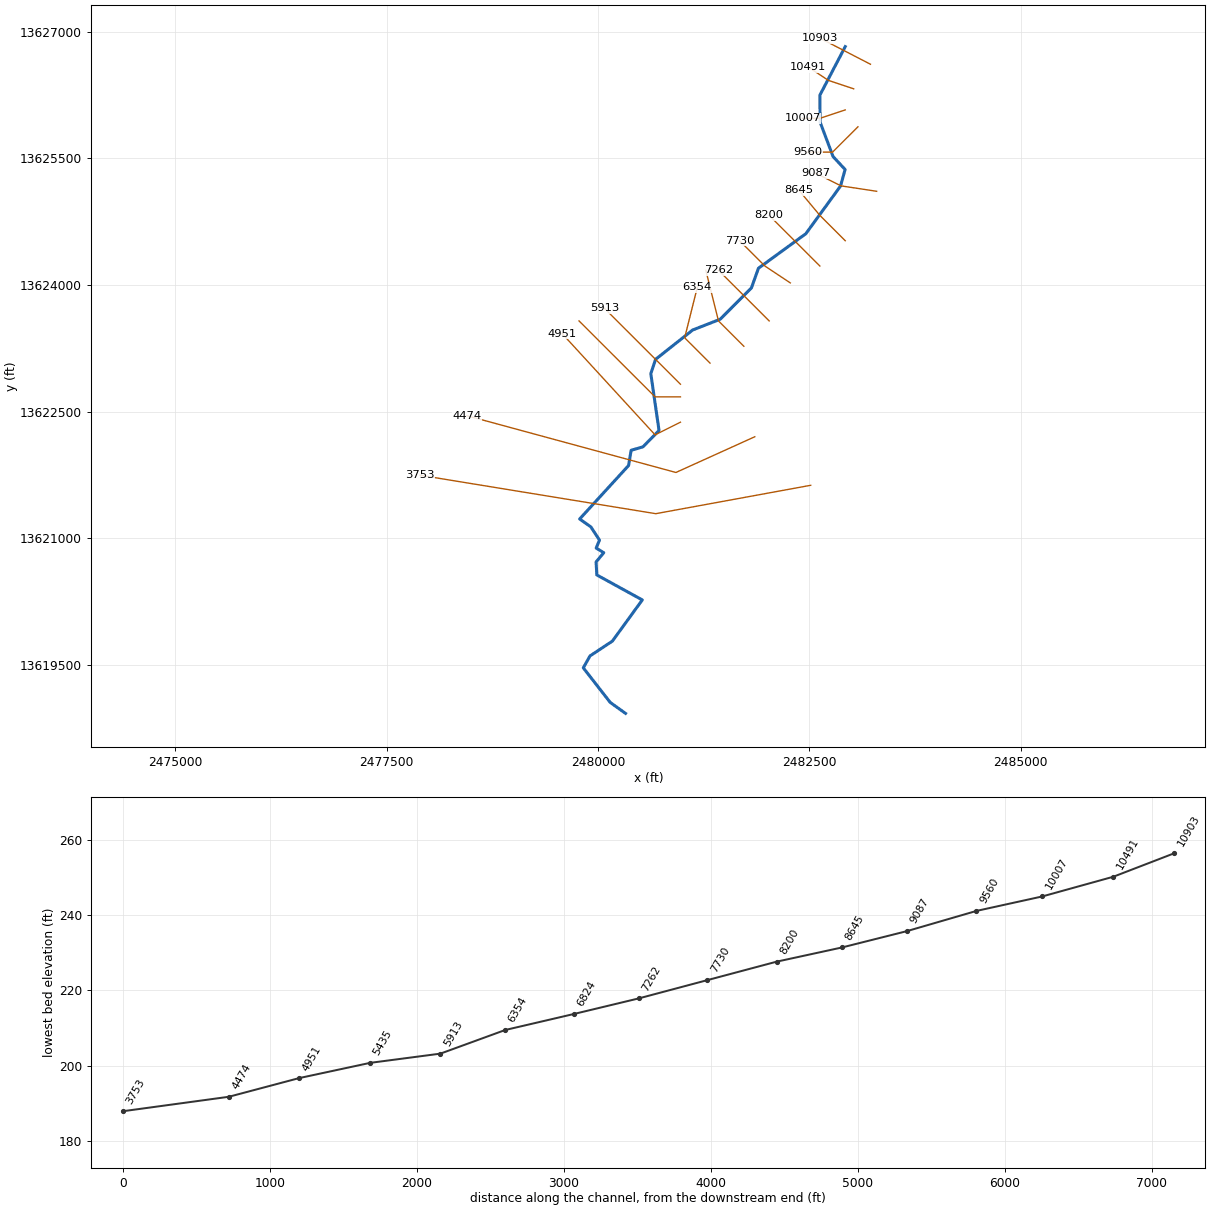
--- Stream0777.prj (project) ---

Proj Title=Stream0777 Base Level Engineering
Current Plan=p01
Default Exp/Contr=0.3,0.1
English Units
Geom File=g01
Flow File=f01
Plan File=p01
BEGIN DESCRIPTION:
Stream0777
END DESCRIPTION:

--- Stream0777.p01 (plan) ---

Plan Title=Multiple Run
Short Identifier=Multiple
Geom File=g01
Flow File=f01
Subcritical Flow
K Sum by GR= 0
Std Step Tol= 0.01
Critical Tol= 0.01
Num of Std Step Trials= 20
Max Error Tol= 0.3
Flow Tol Ratio= 0.001
Split Flow NTrial= 30
Split Flow Tol= 0.02
Split Flow Ratio= 0.02
Log Output Level= 0
Friction Slope Method= 1
Unsteady Friction Slope Method= 2
Unsteady Bridges Friction Slope Method= 1
Parabolic Critical Depth
Global Vel Dist=  1 , 1 , 1
Global Log Level= 0
CheckData=True
Encroach Param= -1, 0, 0, 0
BEGIN DESCRIPTION:
Multiple Run
END DESCRIPTION:

--- Stream0777.f01 (steady flow) ---

Flow Title=Multiple
Number of Profiles=7
Profile Names=10-year,25-year,50-year,1pct_min,100-year,1pct_plu,500-year
River Rch & RM= Stream0777,Reach-1,10903
     402     629     828     530    1057    2110    1703
River Rch & RM= Stream0777,Reach-1,9087
     607     972    1301     843    1683    3357    2786
Boundary for River Rch & Prof#=Stream0777,Reach-1,1
Up Type=0
Dn Type=3
Dn Slope=0.005
Boundary for River Rch & Prof#=Stream0777,Reach-1,2
Up Type=0
Dn Type=3
Dn Slope=0.005
Boundary for River Rch & Prof#=Stream0777,Reach-1,3
Up Type=0
Dn Type=3
Dn Slope=0.005
Boundary for River Rch & Prof#=Stream0777,Reach-1,4
Up Type=0
Dn Type=3
Dn Slope=0.005
Boundary for River Rch & Prof#=Stream0777,Reach-1,5
Up Type=0
Dn Type=3
Dn Slope=0.005
Boundary for River Rch & Prof#=Stream0777,Reach-1,6
Up Type=0
Dn Type=3
Dn Slope=0.005
Boundary for River Rch & Prof#=Stream0777,Reach-1,7
Up Type=0
Dn Type=3
Dn Slope=0.005

--- Stream0777.g01 (geometry) ---

Geom Title=Existing Conditions

River Reach=Stream0777,Reach-1
Reach XY= 30
      2482925.00     13626825.00      2482624.79     13626250.09
      2482627.24     13625930.93      2482780.47     13625522.55
      2482923.04     13625369.11      2482869.17     13625172.70
      2482458.50     13624607.95      2481897.85     13624198.84
      2481814.48     13623965.21      2481445.13     13623594.77
      2481118.94     13623466.86      2480680.59     13623119.39
      2480624.60     13622950.00      2480721.54     13622276.50
      2480531.17     13622082.86      2480391.44     13622042.13
      2480361.35     13621861.66      2479782.53     13621228.15
      2479914.35     13621135.00      2480017.16     13620978.38
      2479977.72     13620883.50      2480067.46     13620828.57
      2479977.07     13620719.14      2479985.46     13620565.18
      2480523.50     13620269.13      2480169.38     13619780.62
      2479904.52     13619605.37      2479825.70     13619464.30
      2480144.21     13619054.61      2480325.00     13618925.00

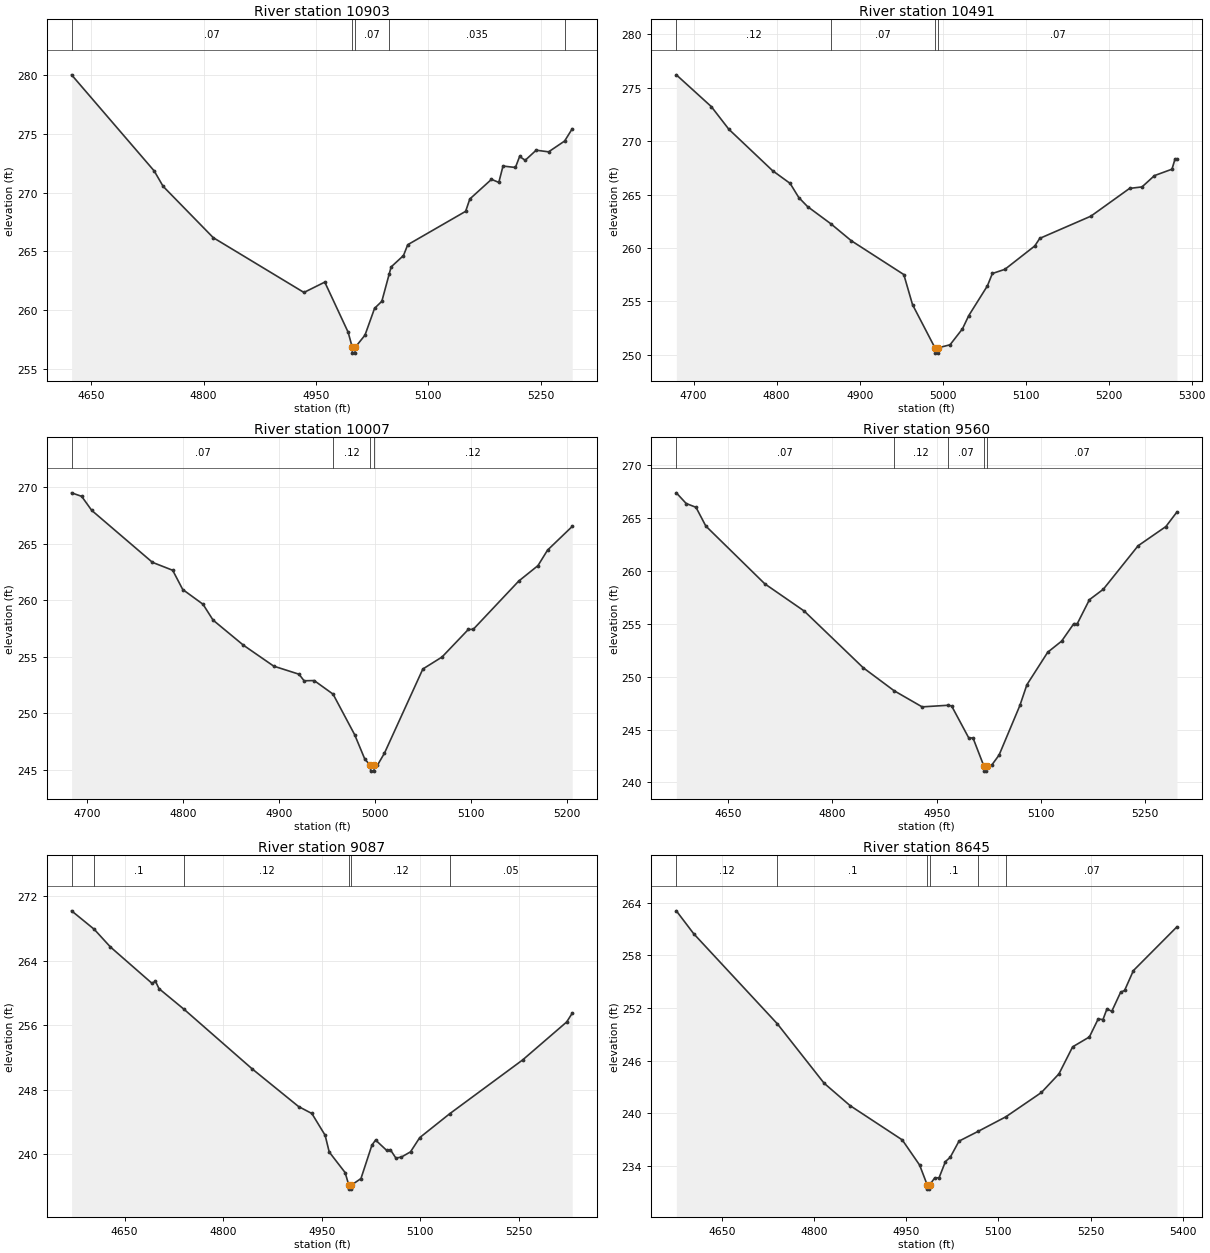
Type RM Length L Ch R = 1,10903,412,412,412
BEGIN DESCRIPTION:
E21361
END DESCRIPTION:
XS GIS Cut Line= 2
      2483223.13     13626616.22      2482629.20     13626923.04
#Sta/Elev= 30
  4623.7  280.02  4734.1  271.84  4745.9  270.54  4812.9  266.17  4934.0  261.51
  4961.8  262.39  4993.0  258.13  4998.5  256.85  4998.7  256.35  5002.2  256.35
  5002.5  256.85  5015.5  257.88  5028.3  260.16  5038.0  260.76  5047.8  263.07
  5050.4  263.68  5066.9  264.65  5072.6  265.57  5149.9  268.41  5155.5  269.46
  5184.4  271.13  5194.2  270.87  5199.8  272.26  5216.4  272.14  5222.0  273.08
  5229.4  272.75  5244.1  273.61  5260.7  273.47  5282.1  274.39  5292.2  275.43
#Mann=5,-1,0
  4623.7    0.07       0  4998.5    0.05       0  5002.5    0.07       0
  5047.8   0.035       0  5282.1    0.07       0
Bank Sta=4998.5,5002.5
Exp/Cntr=0.3,0.1

Type RM Length L Ch R = 1,10491,484,484,484
BEGIN DESCRIPTION:
Stream0777 17.0
END DESCRIPTION:
XS GIS Cut Line= 4
      2483025.02     13626324.99      2482725.00     13626425.00
      2482575.00     13626525.00      2482486.24     13626584.17
#Sta/Elev= 30
  4679.1  276.22  4721.3  273.24  4742.4  271.12  4795.1  267.24  4816.2  266.05
  4826.7  264.72  4837.2  263.88  4865.4  262.26  4889.9  260.68  4953.2  257.51
  4963.7  254.69  4990.7  250.65  4991.0  250.15  4994.5  250.15  4994.7  250.65
  5008.9  250.93  5023.9  252.43  5031.4  253.66  5053.9  256.45  5059.9  257.61
  5075.0  258.00  5111.0  260.19  5117.0  260.90  5178.6  262.98  5225.2  265.58
  5240.2  265.72  5255.2  266.78  5276.3  267.38  5280.0  268.34  5282.3  268.34
#Mann=4,-1,0
  4679.1    0.12       0  4865.4    0.07       0  4990.7    0.05       0
  4994.7    0.07       0
Bank Sta=4990.7,4994.7
Exp/Cntr=0.3,0.1

Type RM Length L Ch R = 1,10007,447,447,447
BEGIN DESCRIPTION:
Stream0777 16.0
END DESCRIPTION:
XS GIS Cut Line= 4
      2482924.97     13626074.99      2482625.00     13625975.00
      2482525.00     13625975.00      2482419.29     13625975.00
#Sta/Elev= 30
  4683.4  269.49  4693.9  269.18  4704.4  267.94  4767.7  263.35  4788.8  262.65
  4799.3  260.95  4820.4  259.65  4830.9  258.25  4862.6  256.03  4894.2  254.18
  4920.5  253.47  4925.8  252.89  4936.3  252.91  4956.0  251.71  4978.5  248.13
  4989.1  245.97  4995.0  245.41  4995.2  244.91  4998.7  244.91  4999.0  245.41
  5002.1  245.41  5009.6  246.50  5049.6  253.93  5069.6  254.99  5097.1  257.43
  5102.1  257.43  5149.6  261.70  5169.6  263.06  5179.6  264.43  5205.3  266.52
#Mann=4,-1,0
  4683.4    0.07       0  4956.0    0.12       0  4995.0    0.05       0
  4999.0    0.12       0
Bank Sta=4995,4999
Exp/Cntr=0.3,0.1

Type RM Length L Ch R = 1,9560,473,473,473
BEGIN DESCRIPTION:
Stream0777 15.0
END DESCRIPTION:
XS GIS Cut Line= 4
      2483075.01     13625875.01      2482775.00     13625575.00
      2482625.00     13625575.00      2482479.08     13625575.00
#Sta/Elev= 30
  4575.4  267.40  4589.6  266.39  4603.7  266.03  4617.8  264.26  4702.7  258.79
  4759.3  256.22  4844.1  250.86  4888.6  248.68  4929.0  247.15  4966.0  247.30
  4971.4  247.24  4996.1  244.21  5002.2  244.21  5017.7  241.57  5017.9  241.07
  5021.4  241.07  5021.7  241.57  5029.7  241.69  5039.7  242.59  5069.7  247.29
  5079.7  249.24  5109.7  252.32  5129.7  253.37  5147.2  255.02  5152.2  255.02
  5169.7  257.29  5189.7  258.28  5239.7  262.39  5279.7  264.21  5295.6  265.59
#Mann=5,-1,0
  4575.4    0.07       0  4888.6    0.12       0  4966.0    0.07       0
  5017.7    0.05       0  5021.7    0.07       0
Bank Sta=5017.7,5021.7
Exp/Cntr=0.3,0.1

Type RM Length L Ch R = 1,9087,442,442,442
BEGIN DESCRIPTION:
Stream0777 14.0
END DESCRIPTION:
XS GIS Cut Line= 3
      2483296.44     13625110.84      2482875.00     13625175.00
      2482575.01     13625325.00
#Sta/Elev= 30
  4569.4  270.18  4603.9  267.89  4628.4  265.71  4691.9  261.19  4697.0  261.46
  4702.4  260.54  4740.4  257.99  4844.0  250.61  4914.8  245.93  4935.0  245.07
  4955.2  242.37  4961.4  240.30  4985.6  237.75  4991.2  236.20  4991.4  235.70
  4994.9  235.70  4995.2  236.20  5009.7  237.01  5026.4  241.16  5032.0  241.78
  5048.8  240.50  5054.4  240.59  5062.8  239.55  5071.2  239.67  5085.1  240.32
  5099.1  242.08  5144.7  245.04  5255.6  251.70  5322.7  256.41  5331.1  257.49
#Mann=6,-1,0
  4569.4    0.07       0  4603.9     0.1       0  4740.4    0.12       0
  4991.2    0.05       0  4995.2    0.12       0  5144.7    0.05       0
Bank Sta=4991.2,4995.2
Exp/Cntr=0.3,0.1

Type RM Length L Ch R = 1,8645,445,445,445
BEGIN DESCRIPTION:
Stream0777 13.0
END DESCRIPTION:
XS GIS Cut Line= 3
      2482925.03     13624524.97      2482625.00     13624825.00
      2482375.02     13625124.98
#Sta/Elev= 30
  4575.9  263.07  4604.2  260.46  4740.4  250.19  4816.4  243.43  4858.8  240.87
  4943.6  236.97  4971.9  234.10  4984.1  231.86  4984.3  231.36  4987.8  231.36
  4988.1  231.86  4996.7  232.65  5003.5  232.65  5013.9  234.50  5021.7  234.99
  5036.0  236.83  5067.6  237.96  5112.2  239.60  5170.1  242.37  5198.7  244.50
  5220.9  247.57  5248.2  248.70  5262.5  250.75  5270.3  250.68  5276.8  251.90
  5284.6  251.62  5299.0  253.79  5305.5  254.00  5319.8  256.26  5390.7  261.25
#Mann=6,-1,0
  4575.9    0.12       0  4740.4     0.1       0  4984.1    0.05       0
  4988.1     0.1       0  5067.6    0.05       0  5112.2    0.07       0
Bank Sta=4984.1,4988.1
Exp/Cntr=0.3,0.1

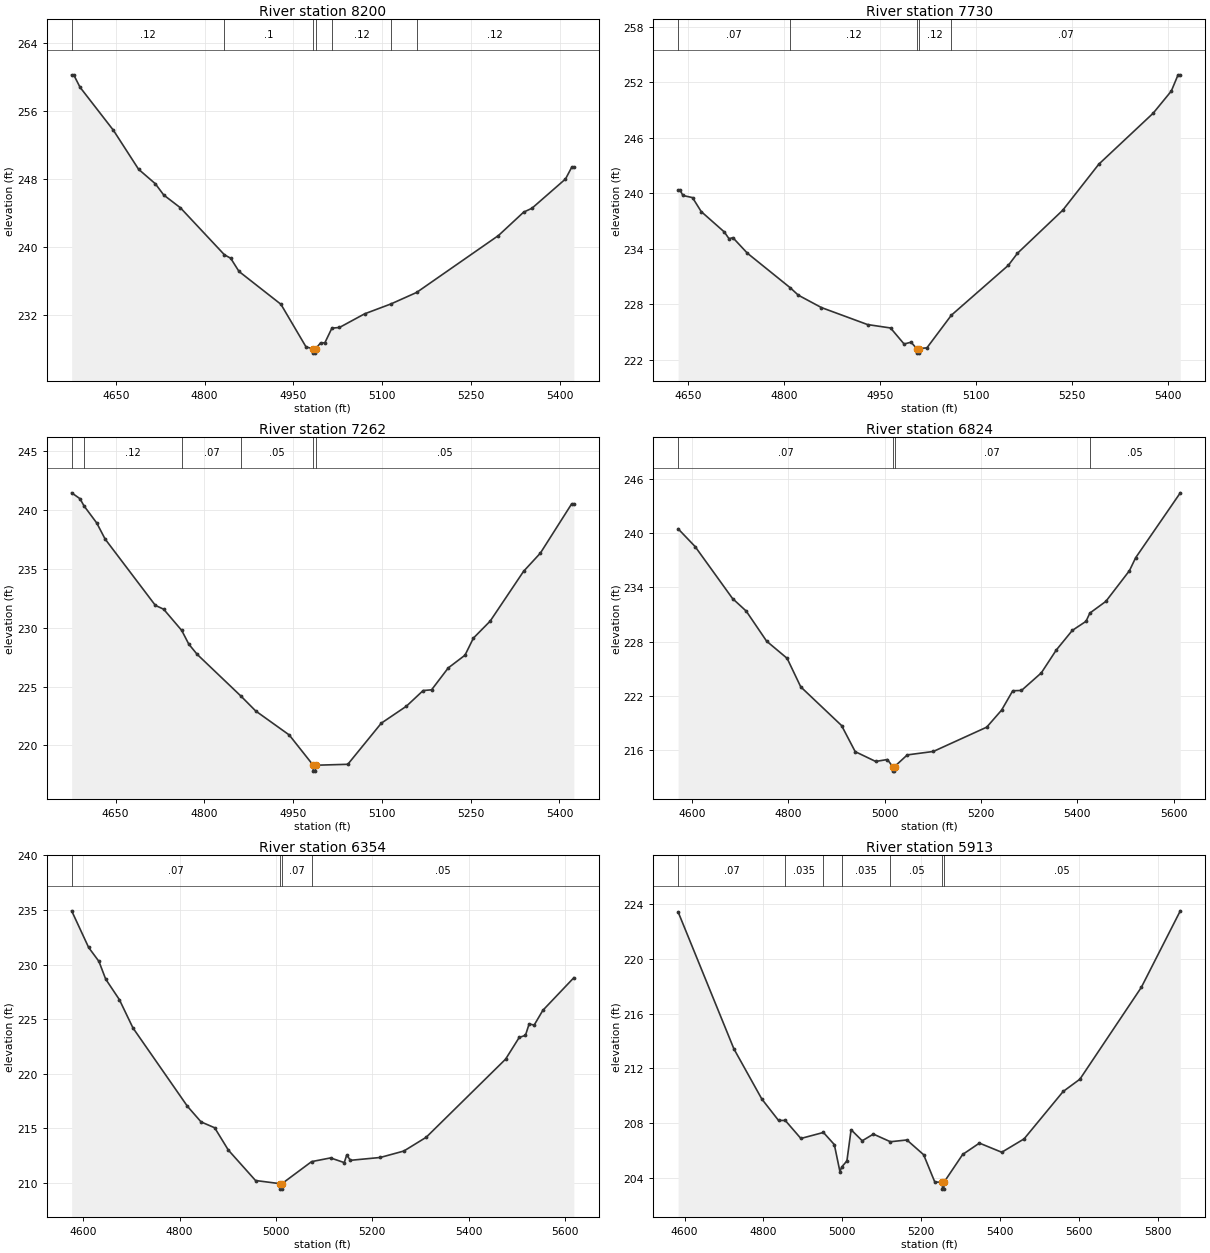
Type RM Length L Ch R = 1,8200,470,470,470
BEGIN DESCRIPTION:
Stream0777 12.0
END DESCRIPTION:
XS GIS Cut Line= 3
      2482625.00     13624225.00      2482325.00     13624525.00
      2482025.02     13624824.98
#Sta/Elev= 30
  4575.5  260.23  4579.0  260.23  4589.6  258.78  4646.2  253.71  4688.6  249.15
  4716.9  247.45  4731.1  246.13  4759.3  244.63  4833.6  239.12  4844.2  238.71
  4858.3  237.16  4929.1  233.31  4971.5  228.31  4983.6  228.08  4983.9  227.58
  4987.4  227.58  4987.6  228.08  4996.2  228.79  5003.3  228.79  5015.2  230.51
  5028.0  230.59  5070.5  232.19  5115.3  233.36  5158.4  234.70  5296.7  241.38
  5339.2  244.12  5353.3  244.58  5409.9  248.01  5420.5  249.40  5424.0  249.40
#Mann=7,-1,0
  4575.5    0.12       0  4833.6     0.1       0  4983.6    0.05       0
  4987.6     0.1       0  5015.2    0.12       0  5115.3    0.05       0
  5158.4    0.12       0
Bank Sta=4983.6,4987.6
Exp/Cntr=0.3,0.1

Type RM Length L Ch R = 1,7730,468,468,468
BEGIN DESCRIPTION:
Stream0777 11.0
END DESCRIPTION:
XS GIS Cut Line= 3
      2482275.01     13624025.00      2481975.00     13624225.00
      2481675.02     13624524.98
#Sta/Elev= 30
  4634.6  240.32  4637.6  240.32  4642.1  239.74  4657.1  239.51  4670.7  238.00
  4706.7  235.80  4714.2  235.06  4720.2  235.18  4742.8  233.50  4810.0  229.75
  4822.4  228.96  4858.5  227.62  4930.6  225.78  4966.6  225.41  4987.7  223.68
  4998.7  223.87  5007.3  223.19  5007.6  222.69  5011.1  222.69  5011.3  223.19
  5023.4  223.26  5061.6  226.79  5150.7  232.19  5164.9  233.49  5235.6  238.14
  5292.1  243.13  5377.0  248.64  5405.3  251.03  5415.9  252.79  5419.4  252.79
#Mann=5,-1,0
  4634.6    0.07       0  4810.0    0.12       0  5007.3    0.05       0
  5011.3    0.12       0  5061.6    0.07       0
Bank Sta=5007.3,5011.3
Exp/Cntr=0.3,0.1

Type RM Length L Ch R = 1,7262,438,438,438
BEGIN DESCRIPTION:
Stream0777 10.0
END DESCRIPTION:
XS GIS Cut Line= 3
      2482024.97     13623575.03      2481725.00     13623875.00
      2481424.99     13624175.01
#Sta/Elev= 30
  4575.8  241.44  4589.9  240.94  4596.7  240.33  4618.2  238.88  4632.3  237.52
  4717.2  231.89  4731.3  231.56  4761.8  229.76  4773.7  228.60  4787.9  227.73
  4861.8  224.19  4886.9  222.92  4943.4  220.89  4983.9  218.32  4984.1  217.82
  4987.6  217.82  4987.9  218.32  5042.4  218.40  5099.0  221.89  5141.4  223.33
  5169.7  224.66  5183.9  224.72  5212.1  226.58  5240.4  227.66  5254.6  229.11
  5282.9  230.55  5339.4  234.78  5367.7  236.32  5420.7  240.51  5424.3  240.51
#Mann=6,-1,0
  4575.8    0.07       0  4596.7    0.12       0  4761.8    0.07       0
  4861.8    0.05       0  4983.9    0.05       0  4987.9    0.05       0
Bank Sta=4983.9,4987.9
Exp/Cntr=0.3,0.1

Type RM Length L Ch R = 1,6824,470,470,470
BEGIN DESCRIPTION:
Stream0777 9.0
END DESCRIPTION:
XS GIS Cut Line= 3
      2481725.00     13623275.00      2481425.00     13623575.00
      2481275.01     13624174.98
#Sta/Elev= 30
  4571.4  240.45  4606.7  238.49  4684.5  232.75  4712.8  231.37  4755.2  228.05
  4797.7  226.16  4826.0  223.01  4910.8  218.74  4939.1  215.86  4981.5  214.78
  5006.0  214.99  5016.8  214.21  5017.1  213.71  5020.6  213.71  5020.8  214.21
  5047.2  215.50  5101.3  215.88  5212.1  218.56  5243.0  220.44  5266.2  222.58
  5284.3  222.61  5325.5  224.55  5356.4  227.06  5389.9  229.24  5418.3  230.24
  5426.3  231.15  5459.5  232.44  5508.5  235.83  5521.4  237.26  5614.1  244.42
#Mann=4,-1,0
  4571.4    0.07       0  5016.8    0.05       0  5020.8    0.07       0
  5426.3    0.05       0
Bank Sta=5016.8,5020.8
Exp/Cntr=0.3,0.1

Type RM Length L Ch R = 1,6354,441,441,441
BEGIN DESCRIPTION:
Stream0777 8.0
END DESCRIPTION:
XS GIS Cut Line= 3
      2481324.99     13623075.01      2481025.00     13623375.00
      2481175.00     13623974.98
#Sta/Elev= 30
  4575.7  234.93  4611.0  231.57  4632.3  230.30  4646.4  228.67  4674.7  226.80
  4703.0  224.20  4816.1  217.02  4844.4  215.59  4872.7  215.05  4901.0  213.01
  4957.5  210.22  5008.3  209.93  5008.5  209.43  5012.0  209.43  5012.3  209.93
  5073.9  211.95  5113.3  212.29  5141.7  211.86  5146.8  212.55  5154.6  212.07
  5216.4  212.33  5265.4  212.92  5311.8  214.18  5476.7  221.34  5505.0  223.33
  5517.9  223.52  5525.6  224.57  5536.0  224.46  5554.0  225.81  5618.4  228.80
#Mann=4,-1,0
  4575.7    0.07       0  5008.3    0.05       0  5012.3    0.07       0
  5073.9    0.05       0
Bank Sta=5008.3,5012.3
Exp/Cntr=0.3,0.1

Type RM Length L Ch R = 1,5913,478,478,478
BEGIN DESCRIPTION:
Stream0777 7.0
END DESCRIPTION:
XS GIS Cut Line= 3
      2480974.97     13622825.03      2480675.00     13623125.00
      2480075.03     13623724.97
#Sta/Elev= 30
  4583.7  223.45  4725.1  213.42  4795.8  209.75  4838.2  208.18  4855.2  208.18
  4894.8  206.86  4952.0  207.30  4979.6  206.41  4993.8  204.43  4998.4  204.77
  5011.5  205.22  5022.1  207.50  5050.3  206.69  5078.6  207.18  5121.7  206.62
  5163.5  206.75  5205.9  205.67  5234.2  203.67  5253.4  203.65  5253.7  203.15
  5257.2  203.15  5257.4  203.65  5304.9  205.69  5347.3  206.52  5403.9  205.85
  5460.5  206.83  5559.5  210.30  5601.9  211.20  5757.5  217.92  5856.4  223.53
#Mann=7,-1,0
  4583.7    0.07       0  4855.2   0.035       0  4952.0    0.07       0
  4998.4   0.035       0  5121.7    0.05       0  5253.4   0.035       0
  5257.4    0.05       0
Bank Sta=5253.4,5257.4
Exp/Cntr=0.3,0.1

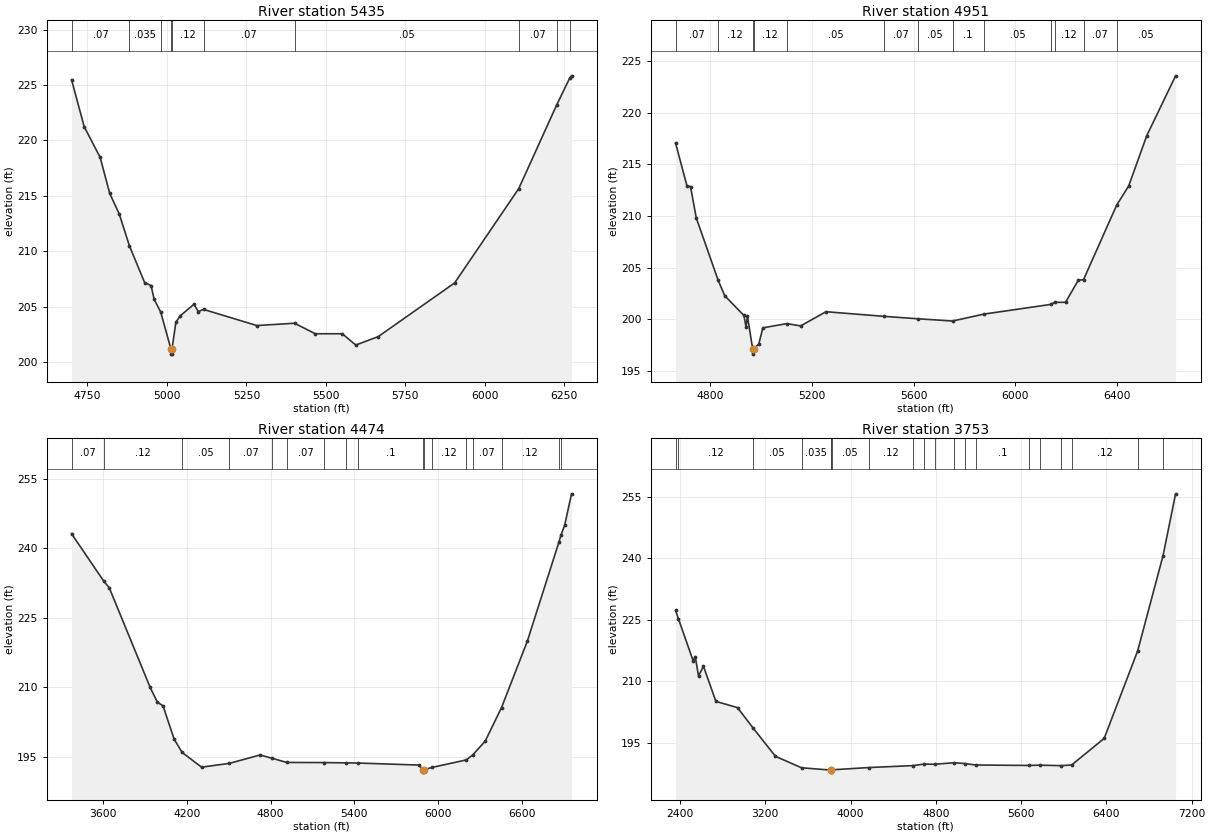
Type RM Length L Ch R = 1,5435,484,484,484
BEGIN DESCRIPTION:
Stream0777 6.0
END DESCRIPTION:
XS GIS Cut Line= 3
      2480975.02     13622675.00      2480675.00     13622675.00
      2479775.01     13623574.99
#Sta/Elev= 30
  4700.0  225.48  4740.0  221.22  4790.0  218.47  4820.0  215.22  4850.0  213.36
  4882.3  210.46  4930.0  207.16  4950.0  206.89  4960.0  205.65  4980.7  204.48
  5012.2  201.20  5012.4  200.70  5015.9  200.70  5016.2  201.20  5028.3  203.59
  5042.4  204.17  5084.9  205.20  5099.0  204.54  5115.1  204.74  5282.9  203.28
  5401.5  203.49  5466.7  202.54  5551.6  202.54  5594.0  201.52  5664.7  202.28
  5905.1  207.13  6106.8  215.65  6226.4  223.22  6267.0  225.62  6272.8  225.83
#Mann=10,-1,0
  4700.0    0.07       0  4882.3   0.035       0  4980.7    0.12       0
  5012.2    0.05       0  5016.2    0.12       0  5115.1    0.07       0
  5401.5    0.05       0  6106.8    0.07       0  6226.4    0.05       0
  6267.0    0.07       0
Bank Sta=5012.2,5016.2
Exp/Cntr=0.3,0.1

Type RM Length L Ch R = 1,4951,477,477,477
BEGIN DESCRIPTION:
Stream0777 5.0
END DESCRIPTION:
XS GIS Cut Line= 3
      2480975.00     13622375.00      2480675.00     13622225.00
      2479574.99     13623425.01
#Sta/Elev= 30
  4665.5  217.04  4710.2  212.91  4724.2  212.84  4746.6  209.82  4832.1  203.82
  4858.4  202.29  4933.8  200.38  4942.2  199.27  4947.8  200.30  4968.2  197.14
  4968.4  196.64  4972.2  197.14  4992.5  197.63  5008.0  199.18  5102.1  199.59
  5156.6  199.37  5255.9  200.74  5485.8  200.29  5616.0  200.06  5753.2  199.84
  5876.0  200.51  6139.7  201.45  6153.9  201.65  6196.8  201.65  6246.8  203.79
  6267.3  203.84  6397.6  211.05  6444.7  212.90  6515.6  217.76  6628.8  223.55
#Mann=13,-1,0
  4665.5    0.07       0  4832.1    0.12       0  4968.2    0.05       0
  4972.2    0.12       0  5102.1    0.05       0  5485.8    0.07       0
  5616.0    0.05       0  5753.2     0.1       0  5876.0    0.05       0
  6139.7    0.07       0  6153.9    0.12       0  6267.3    0.07       0
  6397.6    0.05       0
Bank Sta=4968.2,4972.2
Exp/Cntr=0.3,0.1

Type RM Length L Ch R = 1,4474,721,721,721
BEGIN DESCRIPTION:
XS7719
END DESCRIPTION:
XS GIS Cut Line= 3
      2481854.66     13622202.48      2480921.48     13621779.30
      2478448.73     13622451.71
#Sta/Elev= 30
  3371.4  243.10  3603.2  232.85  3641.9  231.45  3935.4  209.97  3987.1  206.79
  4027.7  205.99  4108.0  198.77  4165.0  195.93  4304.3  192.76  4504.0  193.58
  4724.0  195.39  4812.2  194.66  4915.0  193.78  5183.0  193.75  5341.4  193.69
  5428.5  193.65  5864.0  193.21  5893.1  192.19  5893.3  191.69  5897.1  192.19
  5957.0  192.70  6203.6  194.32  6250.7  195.43  6338.9  198.36  6456.2  205.60
  6641.2  219.91  6867.9  241.27  6883.4  242.85  6909.7  244.98  6958.6  251.71
#Mann=17,-1,0
  3371.4    0.07       0  3603.2    0.12       0  4165.0    0.05       0
  4504.0    0.07       0  4812.2    0.05       0  4915.0    0.07       0
  5183.0     0.1       0  5341.4    0.07       0  5428.5     0.1       0
  5893.1    0.05       0  5897.1     0.1       0  5957.0    0.12       0
  6203.6   0.035       0  6250.7    0.07       0  6456.2    0.12       0
  6867.9    0.07       0  6883.4    0.12       0
Bank Sta=5893.1,5897.1
Exp/Cntr=0.3,0.1

Type RM Length L Ch R = 1,3753,0,0,0
BEGIN DESCRIPTION:
XS7718
END DESCRIPTION:
XS GIS Cut Line= 3
      2482516.56     13621627.39      2480682.77     13621291.02
      2477894.14     13621746.74
#Sta/Elev= 30
  2358.6  227.28  2385.0  225.27  2522.9  215.03  2543.2  216.03  2573.7  211.33
  2620.4  213.66  2736.8  205.10  2939.7  203.58  3084.6  198.64  3295.5  191.70
  3540.4  188.91  3812.0  188.35  3812.3  187.85  3816.0  188.35  3822.9  188.41
  4171.5  188.97  4586.1  189.44  4685.0  189.80  4794.5  189.78  4972.4  190.14
  5072.6  189.94  5172.7  189.59  5673.5  189.48  5773.7  189.55  5974.0  189.43
  6074.1  189.60  6379.0  196.08  6693.1  217.43  6931.2  240.66  7048.6  255.72
#Mann=20,-1,0
  2358.6    0.07       0  2385.0    0.12       0  3084.6    0.05       0
  3540.4   0.035       0  3812.0    0.05       0  3816.0   0.035       0
  3822.9    0.05       0  4171.5    0.12       0  4586.1    0.07       0
  4685.0    0.12       0  4794.5    0.07       0  4972.4    0.05       0
  5072.6    0.12       0  5172.7     0.1       0  5673.5   0.035       0
  5773.7     0.1       0  5974.0   0.035       0  6074.1    0.12       0
  6693.1   0.035       0  6931.2    0.07       0
Bank Sta=3812,3816
Exp/Cntr=0.3,0.1

Chan Stop Cuts=-1