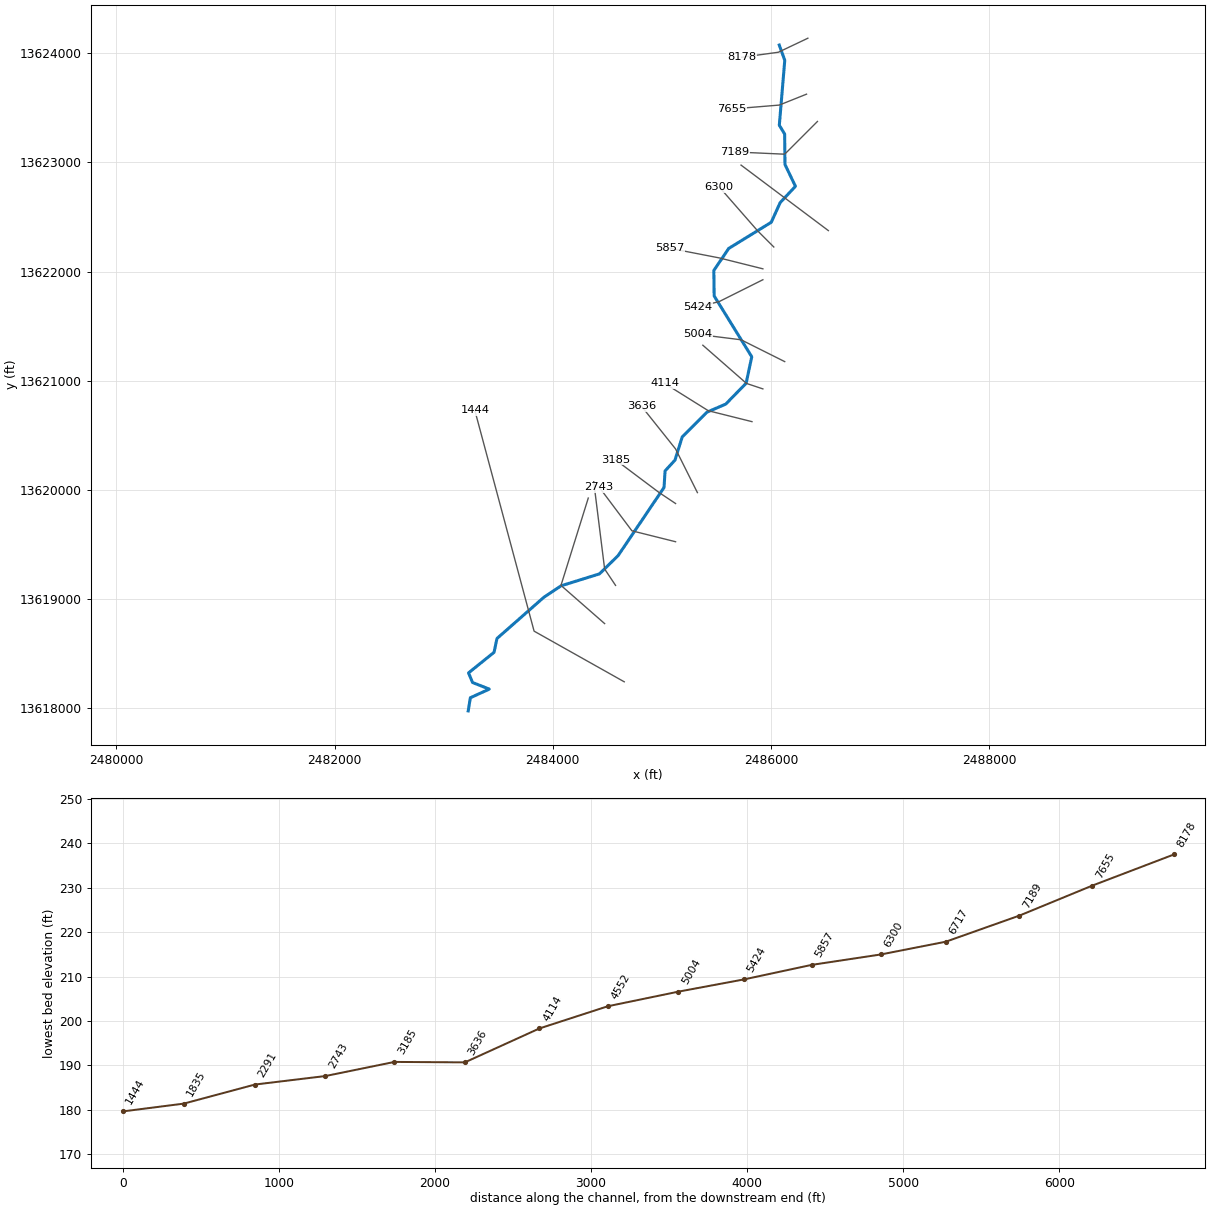
--- Stream0778.prj (project) ---

Proj Title=Stream0778 Base Level Engineering
Current Plan=p01
Default Exp/Contr=0.3,0.1
English Units
Geom File=g01
Flow File=f01
Plan File=p01
BEGIN DESCRIPTION:
Stream0778
END DESCRIPTION:

--- Stream0778.p01 (plan) ---

Plan Title=Multiple Run
Short Identifier=Multiple
Geom File=g01
Flow File=f01
Subcritical Flow
K Sum by GR= 0
Std Step Tol= 0.01
Critical Tol= 0.01
Num of Std Step Trials= 20
Max Error Tol= 0.3
Flow Tol Ratio= 0.001
Split Flow NTrial= 30
Split Flow Tol= 0.02
Split Flow Ratio= 0.02
Log Output Level= 0
Friction Slope Method= 1
Unsteady Friction Slope Method= 2
Unsteady Bridges Friction Slope Method= 1
Parabolic Critical Depth
Global Vel Dist=  1 , 1 , 1
Global Log Level= 0
CheckData=True
Encroach Param= -1, 0, 0, 0
BEGIN DESCRIPTION:
Multiple Run
END DESCRIPTION:

--- Stream0778.f01 (steady flow) ---

Flow Title=Multiple
Number of Profiles=7
Profile Names=10-year,25-year,50-year,1pct_min,100-year,1pct_plu,500-year
River Rch & RM= Stream0778,Reach-1,8178
     886    1463    1997    1321    2635    5258    4542
River Rch & RM= Stream0778,Reach-1,6300
    1066    1772    2430    1612    3217    6418    5583
Boundary for River Rch & Prof#=Stream0778,Reach-1,1
Up Type=0
Dn Type=3
Dn Slope=0.005
Boundary for River Rch & Prof#=Stream0778,Reach-1,2
Up Type=0
Dn Type=3
Dn Slope=0.005
Boundary for River Rch & Prof#=Stream0778,Reach-1,3
Up Type=0
Dn Type=3
Dn Slope=0.005
Boundary for River Rch & Prof#=Stream0778,Reach-1,4
Up Type=0
Dn Type=3
Dn Slope=0.005
Boundary for River Rch & Prof#=Stream0778,Reach-1,5
Up Type=0
Dn Type=3
Dn Slope=0.005
Boundary for River Rch & Prof#=Stream0778,Reach-1,6
Up Type=0
Dn Type=3
Dn Slope=0.005
Boundary for River Rch & Prof#=Stream0778,Reach-1,7
Up Type=0
Dn Type=3
Dn Slope=0.005

--- Stream0778.g01 (geometry) ---

Geom Title=Existing Conditions

River Reach=Stream0778,Reach-1
Reach XY= 30
      2486075.00     13624075.00      2486125.46     13623935.19
      2486075.52     13623340.22      2486124.48     13623259.78
      2486127.24     13622980.93      2486223.39     13622781.04
      2486083.14     13622631.06      2486002.01     13622451.48
      2485611.76     13622211.39      2485475.51     13622009.79
      2485478.55     13621776.47      2485823.03     13621219.11
      2485771.39     13620976.50      2485584.68     13620785.76
      2485411.79     13620711.38      2485185.76     13620484.68
      2485119.46     13620272.58      2485028.56     13620173.53
      2485019.52     13620022.56      2484598.72     13619398.12
      2484427.66     13619230.46      2484076.50     13619121.38
      2483918.95     13619016.84      2483488.40     13618638.30
      2483461.60     13618511.70      2483227.99     13618323.54
      2483264.78     13618235.39      2483418.13     13618175.00
      2483244.40     13618095.69      2483225.00     13617975.00

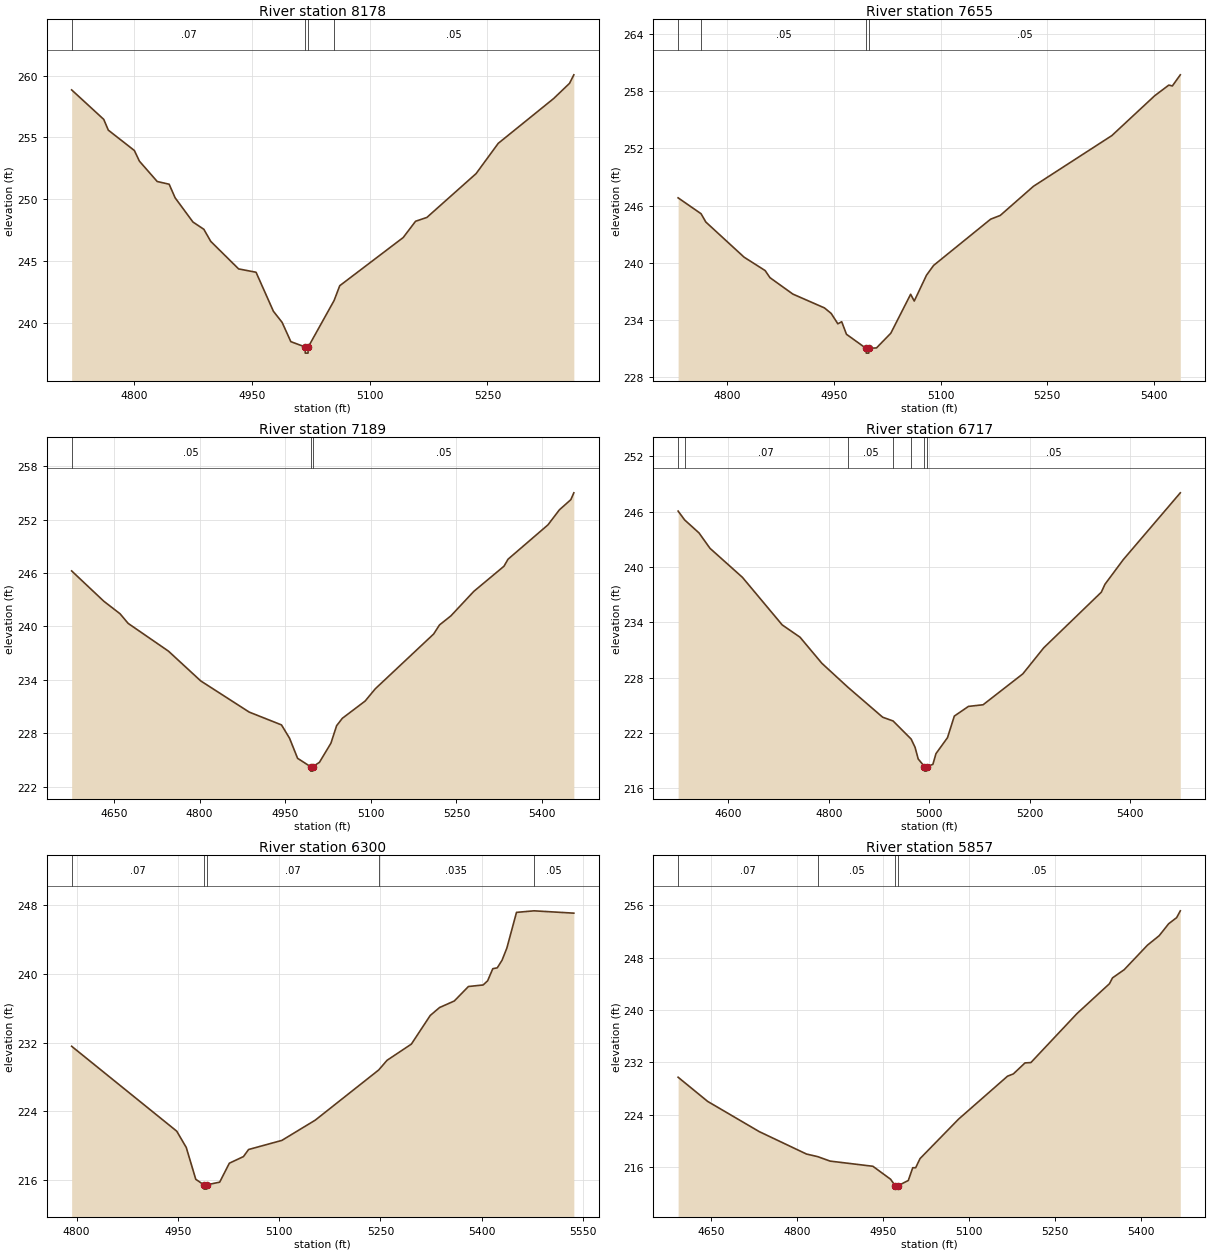
Type RM Length L Ch R = 1,8178,523,523,523
BEGIN DESCRIPTION:
Stream0778 18.0
END DESCRIPTION:
XS GIS Cut Line= 3
      2486337.15     13624137.43      2486066.73     13624008.94
      2485729.58     13623962.69
#Sta/Elev= 30
  4720.3  258.84  4761.2  256.45  4767.0  255.58  4800.2  253.93  4806.6  253.07
  4829.3  251.42  4844.5  251.20  4852.1  250.10  4874.8  248.14  4888.7  247.55
  4897.5  246.57  4933.0  244.34  4955.2  244.07  4977.3  240.91  4988.4  240.01
  4999.5  238.45  5017.7  238.02  5017.9  237.52  5021.4  237.52  5021.7  238.02
  5054.6  241.78  5061.8  242.98  5142.6  246.88  5158.4  248.20  5172.8  248.51
  5235.5  252.06  5263.7  254.51  5334.3  258.14  5354.5  259.37  5360.0  260.06
#Mann=4,-1,0
  4720.3    0.07       0  5017.7    0.05       0  5021.7    0.07       0
  5054.6    0.05       0
Bank Sta=5017.7,5021.7
Exp/Cntr=0.3,0.1

Type RM Length L Ch R = 1,7655,466,466,466
BEGIN DESCRIPTION:
Stream0778 17.0
END DESCRIPTION:
XS GIS Cut Line= 3
      2486324.96     13623624.98      2486075.00     13623525.00
      2485638.99     13623489.07
#Sta/Elev= 30
  4730.7  246.81  4763.0  245.14  4769.7  244.27  4823.5  240.58  4853.2  239.17
  4859.9  238.43  4892.2  236.70  4936.6  235.25  4946.1  234.67  4955.5  233.58
  4960.9  233.80  4967.6  232.48  4995.2  231.00  4995.5  230.50  4999.0  230.50
  4999.2  231.00  5009.9  231.05  5030.0  232.59  5057.9  236.68  5063.0  235.97
  5080.2  238.68  5090.2  239.71  5170.5  244.57  5184.0  244.96  5230.7  248.02
  5341.1  253.35  5401.3  257.53  5421.2  258.65  5426.2  258.56  5437.4  259.73
#Mann=4,-1,0
  4730.7    0.07       0  4763.0    0.05       0  4995.2    0.05       0
  4999.2    0.05       0
Bank Sta=4995.2,4999.2
Exp/Cntr=0.3,0.1

Type RM Length L Ch R = 1,7189,472,472,472
BEGIN DESCRIPTION:
Stream0778 16.0
END DESCRIPTION:
XS GIS Cut Line= 3
      2486424.97     13623374.97      2486125.00     13623075.00
      2485669.69     13623095.63
#Sta/Elev= 30
  4575.7  246.23  4632.2  242.82  4660.5  241.42  4674.7  240.34  4745.4  237.22
  4801.9  233.88  4886.8  230.38  4943.4  228.94  4957.5  227.45  4971.6  225.19
  4994.4  224.25  4994.6  223.75  4998.1  223.75  4998.4  224.25  5009.9  224.74
  5030.0  226.88  5040.0  228.85  5050.0  229.68  5090.0  231.62  5107.7  232.99
  5210.1  239.15  5220.2  240.16  5240.2  241.18  5280.2  243.92  5333.3  246.76
  5340.3  247.54  5410.3  251.40  5430.4  253.09  5450.4  254.23  5455.7  255.00
#Mann=3,-1,0
  4575.7    0.05       0  4994.4    0.05       0  4998.4    0.05       0
Bank Sta=4994.4,4998.4
Exp/Cntr=0.3,0.1

Type RM Length L Ch R = 1,6717,417,417,417
BEGIN DESCRIPTION:
Stream0778 15.0
END DESCRIPTION:
XS GIS Cut Line= 3
      2486524.98     13622375.02      2486125.00     13622675.00
      2485724.98     13622975.02
#Sta/Elev= 30
  4499.8  246.07  4512.8  245.11  4541.4  243.70  4563.3  242.03  4627.9  238.88
  4707.1  233.72  4742.5  232.39  4786.2  229.55  4837.5  226.98  4907.1  223.71
  4927.9  223.30  4963.8  221.34  4971.6  220.45  4977.9  219.18  4990.3  218.36
  4990.6  217.86  4994.3  217.86  4994.6  218.36  5007.1  218.59  5013.3  219.76
  5036.2  221.49  5049.8  223.83  5077.9  224.88  5107.1  225.06  5186.2  228.41
  5227.9  231.24  5342.5  237.27  5349.8  238.13  5386.2  240.80  5499.8  248.05
#Mann=7,-1,0
  4499.8    0.05       0  4512.8    0.07       0  4837.5    0.05       0
  4927.9    0.07       0  4963.8    0.05       0  4990.3    0.05       0
  4994.6    0.05       0
Bank Sta=4990.3,4994.6
Exp/Cntr=0.3,0.1

Type RM Length L Ch R = 1,6300,443,443,443
BEGIN DESCRIPTION:
Stream0778 14.0
END DESCRIPTION:
XS GIS Cut Line= 3
      2486024.99     13622225.01      2485875.00     13622375.00
      2485525.02     13622774.98
#Sta/Elev= 30
  4792.7  231.57  4948.3  221.71  4962.4  219.82  4976.5  216.12  4988.5  215.48
  4988.8  214.98  4992.5  214.98  4992.8  215.48  5011.9  215.79  5026.2  217.99
  5047.1  218.76  5054.7  219.58  5104.0  220.64  5153.4  222.99  5247.4  228.82
  5259.7  229.94  5295.7  231.82  5323.7  235.15  5337.5  236.07  5359.3  236.83
  5380.2  238.51  5402.0  238.69  5408.7  239.18  5416.3  240.58  5422.9  240.68
  5430.0  241.56  5437.1  242.97  5451.4  247.12  5477.4  247.30  5536.3  247.03
#Mann=5,-1,0
  4792.7    0.07       0  4988.5    0.05       0  4992.8    0.07       0
  5247.4   0.035       0  5477.4    0.05       0
Bank Sta=4988.5,4992.8
Exp/Cntr=0.3,0.1

Type RM Length L Ch R = 1,5857,433,433,433
BEGIN DESCRIPTION:
Stream0778 13.0
END DESCRIPTION:
XS GIS Cut Line= 3
      2485925.03     13622024.99      2485525.00     13622125.00
      2485068.77     13622213.61
#Sta/Elev= 30
  4592.0  229.72  4643.6  226.03  4733.8  221.41  4816.2  217.99  4835.9  217.59
  4857.5  216.91  4932.2  216.12  4963.1  214.14  4971.3  213.13  4971.5  212.63
  4975.3  212.63  4975.6  213.13  4994.0  213.95  5001.8  215.90  5006.9  215.90
  5014.5  217.29  5081.9  223.33  5167.3  229.88  5177.5  230.23  5197.9  231.91
  5208.1  231.96  5288.7  239.45  5345.4  244.01  5350.7  244.90  5371.1  246.15
  5411.8  249.90  5432.2  251.34  5448.8  253.17  5462.7  254.10  5469.1  255.14
#Mann=4,-1,0
  4592.0    0.07       0  4835.9    0.05       0  4971.3    0.05       0
  4975.6    0.05       0
Bank Sta=4971.3,4975.6
Exp/Cntr=0.3,0.1

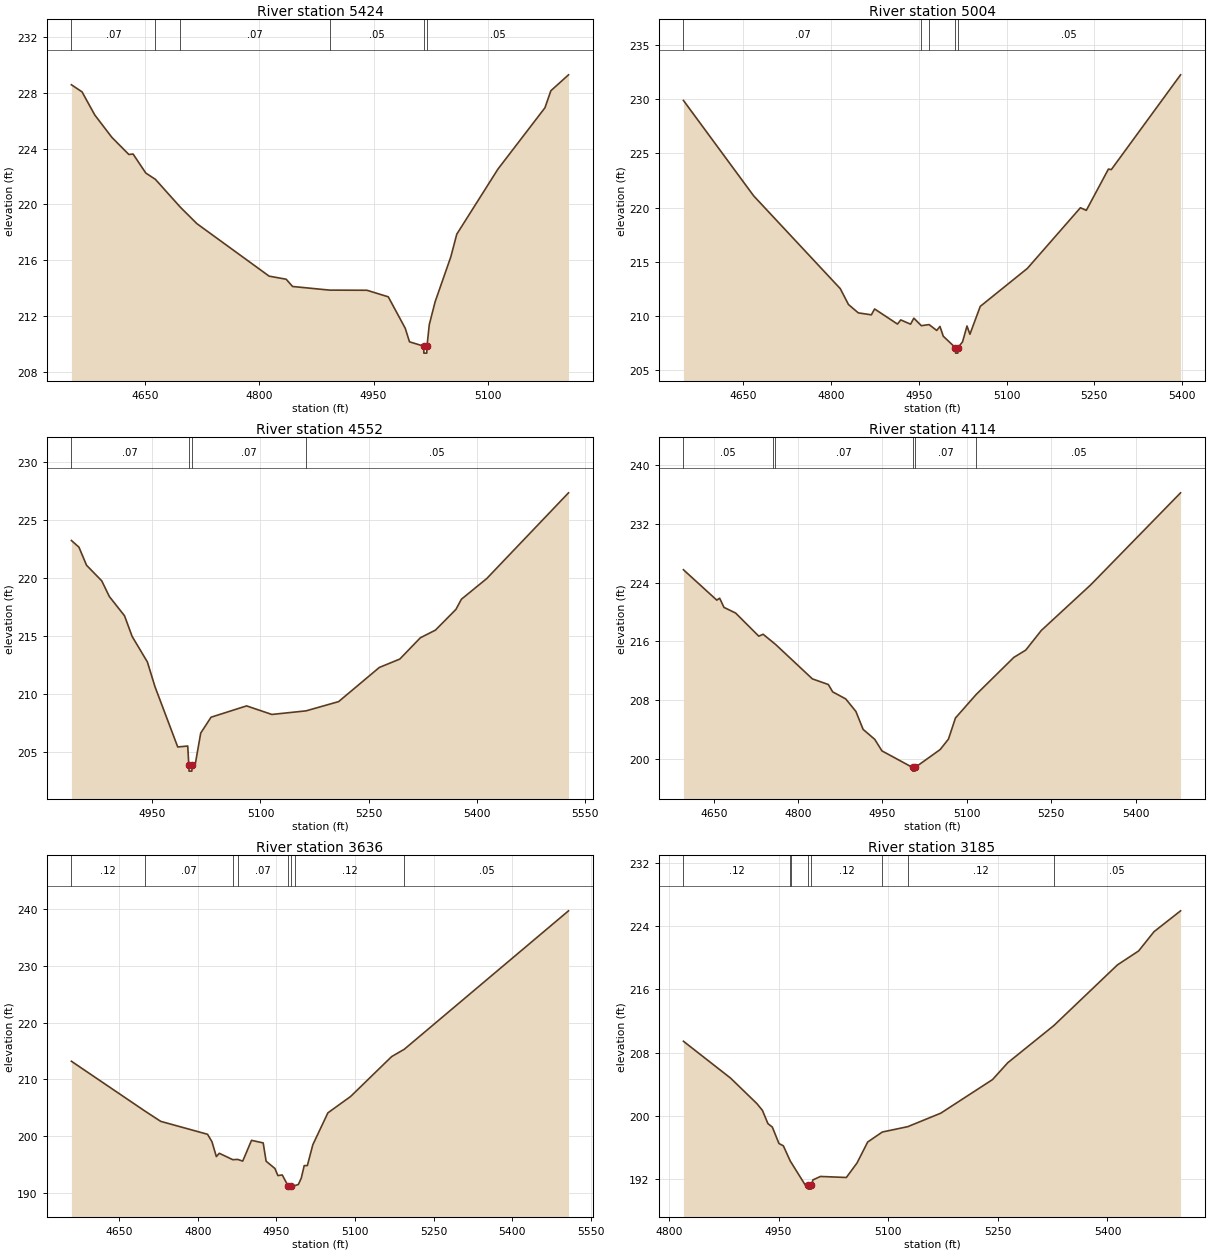
Type RM Length L Ch R = 1,5424,420,420,420
BEGIN DESCRIPTION:
Stream0778 12.0
END DESCRIPTION:
XS GIS Cut Line= 3
      2485924.99     13621925.00      2485525.00     13621725.00
      2485324.96     13621674.99
#Sta/Elev= 30
  4552.8  228.57  4566.8  228.06  4583.5  226.41  4605.9  224.81  4628.3  223.58
  4633.9  223.61  4650.6  222.25  4663.2  221.80  4696.1  219.80  4717.7  218.63
  4812.7  214.87  4835.1  214.65  4843.5  214.13  4892.2  213.87  4941.3  213.86
  4969.3  213.39  4991.6  211.14  4997.2  210.17  5015.8  209.86  5016.1  209.36
  5019.9  209.36  5020.2  209.86  5023.2  211.40  5030.9  213.04  5051.5  216.25
  5059.3  217.87  5113.4  222.53  5175.2  226.92  5183.0  228.14  5206.2  229.28
#Mann=6,-1,0
  4552.8    0.07       0  4663.2   0.035       0  4696.1    0.07       0
  4892.2    0.05       0  5015.8    0.05       0  5020.2    0.05       0
Bank Sta=5015.8,5020.2
Exp/Cntr=0.3,0.1

Type RM Length L Ch R = 1,5004,452,452,452
BEGIN DESCRIPTION:
Stream0778 11.0
END DESCRIPTION:
XS GIS Cut Line= 3
      2486124.98     13621175.01      2485725.00     13621375.00
      2485325.01     13621425.00
#Sta/Elev= 30
  4547.4  229.89  4667.6  221.09  4815.7  212.54  4829.7  211.08  4846.5  210.31
  4868.8  210.13  4874.4  210.67  4913.5  209.28  4919.1  209.66  4935.9  209.27
  4941.5  209.82  4954.3  209.13  4967.6  209.23  4980.6  208.69  4986.2  209.06
  4991.8  208.16  5012.6  207.10  5012.9  206.60  5016.7  206.60  5017.0  207.10
  5024.8  207.64  5032.4  209.10  5037.4  208.34  5055.1  210.91  5135.7  214.41
  5226.4  220.00  5236.5  219.76  5274.3  223.56  5279.3  223.52  5397.7  232.25
#Mann=5,-1,0
  4547.4    0.07       0  4954.3    0.12       0  4967.6    0.05       0
  5012.6    0.05       0  5017.0    0.05       0
Bank Sta=5012.6,5017
Exp/Cntr=0.3,0.1

Type RM Length L Ch R = 1,4552,438,438,438
BEGIN DESCRIPTION:
Stream0778 10.0
END DESCRIPTION:
XS GIS Cut Line= 3
      2485924.96     13620925.01      2485775.00     13620975.00
      2485374.98     13621325.01
#Sta/Elev= 30
  4837.7  223.25  4848.2  222.67  4858.7  221.11  4879.8  219.76  4890.4  218.40
  4911.4  216.74  4922.0  214.95  4943.1  212.75  4953.6  210.62  4985.2  205.40
  4999.1  205.48  5000.6  203.81  5000.9  203.31  5004.8  203.31  5005.2  203.81
  5009.5  203.90  5017.1  206.60  5031.4  207.97  5080.7  208.95  5115.8  208.21
  5163.2  208.52  5208.4  209.32  5264.8  212.27  5293.3  213.00  5321.8  214.84
  5342.7  215.50  5371.1  217.29  5378.7  218.17  5413.9  219.96  5527.3  227.37
#Mann=4,-1,0
  4837.7    0.07       0  5000.6    0.05       0  5005.2    0.07       0
  5163.2    0.05       0
Bank Sta=5000.6,5005.2
Exp/Cntr=0.3,0.1

Type RM Length L Ch R = 1,4114,478,478,478
BEGIN DESCRIPTION:
Stream0778 9.0
END DESCRIPTION:
XS GIS Cut Line= 3
      2485825.00     13620625.00      2485425.00     13620725.00
      2485025.00     13620975.00
#Sta/Elev= 30
  4596.1  225.75  4655.4  221.61  4660.5  221.87  4668.2  220.62  4688.9  219.85
  4730.1  216.70  4737.8  216.96  4755.2  215.87  4759.7  215.59  4825.4  210.88
  4853.8  210.11  4861.5  209.11  4884.7  208.15  4902.8  206.44  4915.6  204.00
  4936.3  202.64  4949.1  201.07  5003.5  198.81  5003.8  198.31  5007.8  198.31
  5008.1  198.81  5052.6  201.25  5067.4  202.68  5079.8  205.55  5116.6  208.75
  5183.5  213.80  5204.8  214.80  5232.5  217.48  5320.3  223.69  5480.1  236.23
#Mann=6,-1,0
  4596.1    0.05       0  4755.2    0.12       0  4759.7    0.07       0
  5003.5    0.05       0  5008.1    0.07       0  5116.6    0.05       0
Bank Sta=5003.5,5008.1
Exp/Cntr=0.3,0.1

Type RM Length L Ch R = 1,3636,451,451,451
BEGIN DESCRIPTION:
Stream0778 8.0
END DESCRIPTION:
XS GIS Cut Line= 3
      2485325.00     13619975.01      2485125.00     13620375.00
      2484811.96     13620767.05
#Sta/Elev= 30
  4558.6  213.21  4698.4  204.46  4729.1  202.61  4818.5  200.33  4826.9  199.02
  4835.3  196.40  4840.9  196.98  4866.7  195.85  4876.0  195.90  4885.6  195.60
  4902.4  199.26  4924.7  198.81  4930.3  195.58  4947.1  194.30  4952.7  193.05
  4961.1  193.16  4972.6  191.16  4973.0  190.66  4977.5  191.16  4984.8  191.27
  4991.8  191.48  4997.4  192.60  5003.0  194.81  5009.0  194.81  5019.4  198.48
  5048.2  204.11  5091.5  206.99  5169.9  214.03  5194.0  215.32  5507.5  239.73
#Mann=8,-1,0
  4558.6    0.12       0  4698.4    0.07       0  4866.7    0.12       0
  4876.0    0.07       0  4972.6    0.05       0  4977.5    0.07       0
  4984.8    0.12       0  5194.0    0.05       0
Bank Sta=4972.6,4977.5
Exp/Cntr=0.3,0.1

Type RM Length L Ch R = 1,3185,442,442,442
BEGIN DESCRIPTION:
Stream0778 7.0
END DESCRIPTION:
XS GIS Cut Line= 3
      2485124.96     13619875.03      2484975.00     13619975.00
      2484575.02     13620274.98
#Sta/Elev= 30
  4819.8  209.43  4884.4  204.77  4920.4  201.55  4927.9  200.70  4935.4  199.03
  4941.4  198.60  4950.5  196.52  4956.5  196.23  4966.1  194.28  4967.6  194.07
  4986.5  191.27  4990.0  191.26  4990.4  190.76  4994.7  190.76  4995.0  191.26
  4997.0  191.93  5007.3  192.36  5042.7  192.23  5057.3  194.06  5071.9  196.71
  5091.9  197.97  5126.8  198.65  5171.9  200.35  5242.7  204.59  5263.6  206.72
  5326.7  211.42  5413.6  219.07  5442.7  220.84  5463.6  223.26  5500.0  225.90
#Mann=8,-1,0
  4819.8    0.12       0  4966.1    0.07       0  4967.6    0.12       0
  4990.0    0.05       0  4995.0    0.12       0  5091.9    0.05       0
  5126.8    0.12       0  5326.7    0.05       0
Bank Sta=4990,4995
Exp/Cntr=0.3,0.1

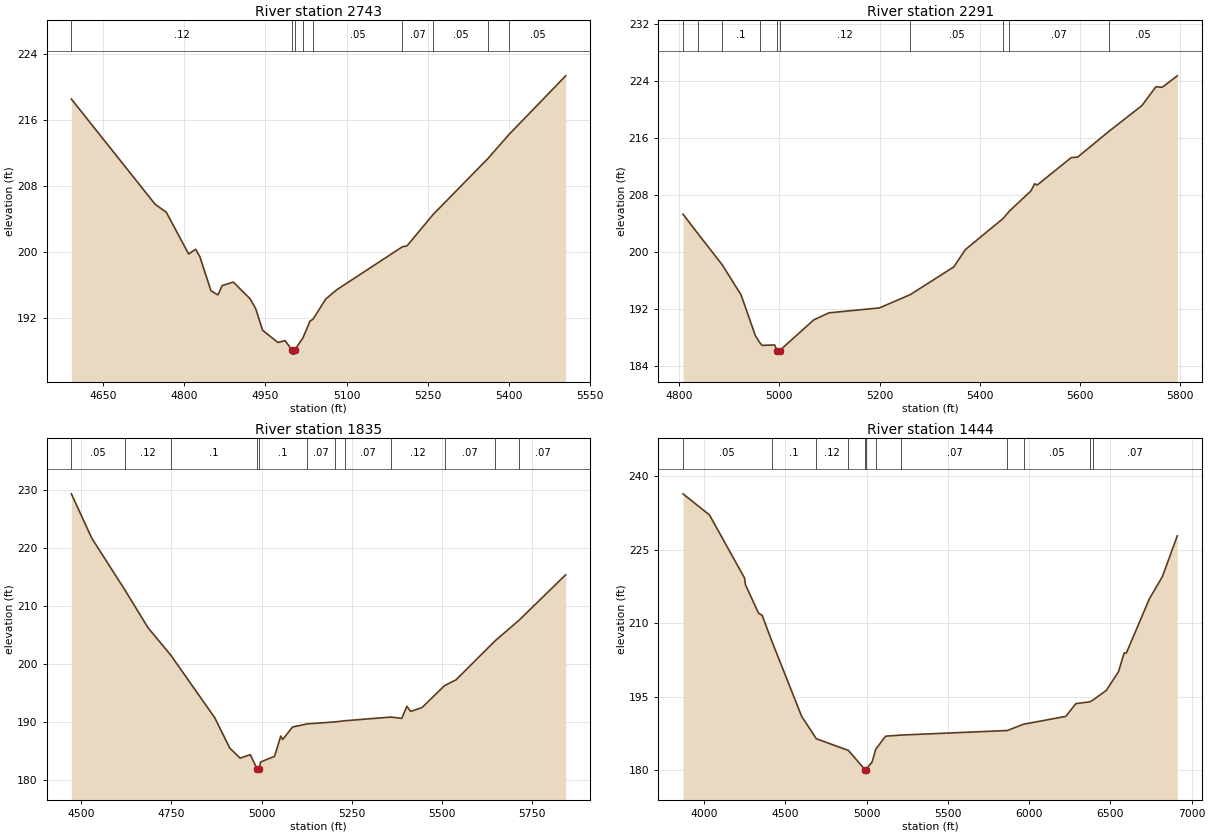
Type RM Length L Ch R = 1,2743,452,452,452
BEGIN DESCRIPTION:
Stream0778 6.0
END DESCRIPTION:
XS GIS Cut Line= 3
      2485124.99     13619525.00      2484725.00     13619625.00
      2484425.00     13620025.00
#Sta/Elev= 30
  4592.1  218.54  4746.7  205.77  4767.3  204.80  4808.5  199.74  4821.4  200.31
  4829.2  199.42  4849.8  195.26  4862.7  194.77  4870.4  195.90  4891.0  196.32
  4921.9  194.30  4932.2  193.12  4945.1  190.47  4973.5  188.99  4986.4  189.22
  4999.3  188.08  4999.7  187.58  5004.0  187.58  5004.4  188.08  5019.6  189.57
  5032.5  191.58  5038.3  191.84  5061.7  194.28  5082.5  195.42  5202.8  200.60
  5211.7  200.73  5259.5  204.51  5360.4  211.29  5400.1  214.26  5504.4  221.36
#Mann=9,-1,0
  4592.1    0.12       0  4999.3    0.05       0  5004.4    0.12       0
  5019.6    0.07       0  5038.3    0.05       0  5202.8    0.07       0
  5259.5    0.05       0  5360.4    0.07       0  5400.1    0.05       0
Bank Sta=4999.3,5004.4
Exp/Cntr=0.3,0.1

Type RM Length L Ch R = 1,2291,456,456,456
BEGIN DESCRIPTION:
Stream0778 5.0
END DESCRIPTION:
XS GIS Cut Line= 3
      2484575.02     13619124.97      2484475.00     13619275.00
      2484375.01     13620074.96
#Sta/Elev= 30
  4807.7  205.32  4836.6  202.66  4885.6  198.24  4923.4  194.01  4952.0  188.27
  4960.4  187.32  4965.5  186.89  4990.5  186.95  4995.5  186.16  4995.9  185.66
  5000.2  185.66  5000.6  186.16  5068.6  190.47  5098.9  191.46  5199.7  192.15
  5261.3  194.02  5348.3  197.92  5371.0  200.33  5446.7  204.72  5459.2  205.76
  5502.0  208.58  5509.5  209.59  5514.6  209.41  5582.6  213.27  5595.2  213.33
  5657.0  216.91  5723.7  220.58  5751.4  223.21  5764.0  223.14  5794.2  224.75
#Mann=10,-1,0
  4807.7    0.07       0  4836.6    0.12       0  4885.6     0.1       0
  4960.4    0.12       0  4995.5    0.05       0  5000.6    0.12       0
  5261.3    0.05       0  5446.7    0.12       0  5459.2    0.07       0
  5657.0    0.05       0
Bank Sta=4995.5,5000.6
Exp/Cntr=0.3,0.1

Type RM Length L Ch R = 1,1835,391,391,391
BEGIN DESCRIPTION:
Stream0778 4.0
END DESCRIPTION:
XS GIS Cut Line= 3
      2484475.02     13618774.98      2484075.00     13619125.00
      2484325.00     13619925.01
#Sta/Elev= 30
  4473.0  229.42  4529.5  221.76  4621.2  212.83  4685.6  206.28  4748.6  201.55
  4870.2  190.76  4912.0  185.51  4940.5  183.78  4968.9  184.37  4988.2  181.86
  4988.6  181.36  4993.3  181.86  4997.4  183.11  5036.0  184.09  5053.3  187.60
  5058.5  186.99  5085.7  189.15  5126.3  189.69  5204.7  190.04  5230.4  190.23
  5358.4  190.87  5388.5  190.64  5402.7  192.73  5413.1  191.84  5444.6  192.51
  5507.1  196.30  5538.9  197.30  5647.0  204.03  5713.3  207.58  5842.7  215.44
#Mann=12,-1,0
  4473.0    0.05       0  4621.2    0.12       0  4748.6     0.1       0
  4988.2    0.05       0  4993.3     0.1       0  5126.3    0.07       0
  5204.7    0.12       0  5230.4    0.07       0  5358.4    0.12       0
  5507.1    0.07       0  5647.0    0.12       0  5713.3    0.07       0
Bank Sta=4988.2,4993.3
Exp/Cntr=0.3,0.1

Type RM Length L Ch R = 1,1444,0,0,0
BEGIN DESCRIPTION:
XS7720
END DESCRIPTION:
XS GIS Cut Line= 3
      2484654.59     13618241.82      2483828.59     13618705.95
      2483285.79     13620727.69
#Sta/Elev= 30
  3871.0  236.43  4033.7  232.12  4249.1  219.27  4255.0  217.88  4335.9  212.04
  4357.6  211.64  4415.4  206.52  4600.5  191.02  4691.0  186.42  4888.3  184.03
  4990.9  180.10  4991.3  179.60  4996.1  180.10  5034.9  181.72  5056.5  184.27
  5117.1  186.94  5214.7  187.17  5866.4  188.10  5967.6  189.40  6225.6  190.98
  6287.8  193.59  6372.6  193.95  6393.5  194.33  6475.3  196.30  6550.1  200.12
  6585.0  203.95  6598.4  203.93  6739.7  214.97  6819.7  219.50  6911.8  227.85
#Mann=12,-1,0
  3871.0    0.05       0  4415.4     0.1       0  4691.0    0.12       0
  4888.3     0.1       0  4990.9    0.05       0  4996.1     0.1       0
  5056.5   0.035       0  5214.7    0.07       0  5866.4    0.12       0
  5967.6    0.05       0  6372.6    0.12       0  6393.5    0.07       0
Bank Sta=4990.9,4996.1
Exp/Cntr=0.3,0.1

Chan Stop Cuts=-1