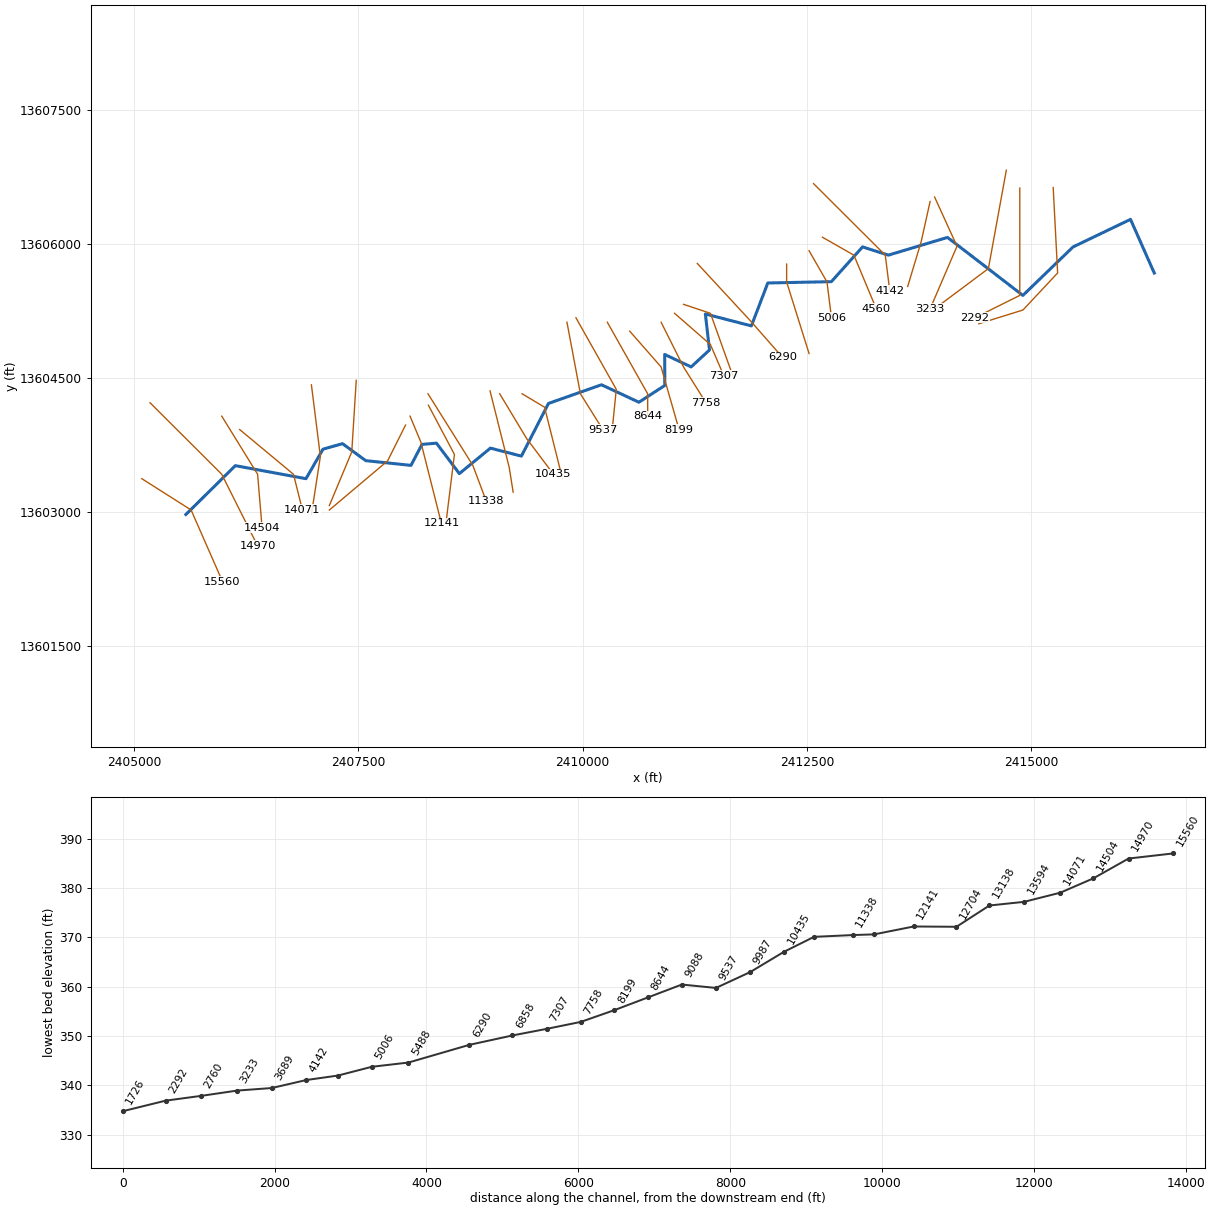
--- Stream0780.prj (project) ---

Proj Title=Stream0780 Base Level Engineering
Current Plan=p01
Default Exp/Contr=0.3,0.1
English Units
Geom File=g01
Flow File=f01
Plan File=p01
BEGIN DESCRIPTION:
Stream0780
END DESCRIPTION:

--- Stream0780.p01 (plan) ---

Plan Title=Multiple Run
Short Identifier=Multiple
Geom File=g01
Flow File=f01
Subcritical Flow
K Sum by GR= 0
Std Step Tol= 0.01
Critical Tol= 0.01
Num of Std Step Trials= 20
Max Error Tol= 0.3
Flow Tol Ratio= 0.001
Split Flow NTrial= 30
Split Flow Tol= 0.02
Split Flow Ratio= 0.02
Log Output Level= 0
Friction Slope Method= 1
Unsteady Friction Slope Method= 2
Unsteady Bridges Friction Slope Method= 1
Parabolic Critical Depth
Global Vel Dist=  1 , 1 , 1
Global Log Level= 0
CheckData=True
Encroach Param= -1, 0, 0, 0
BEGIN DESCRIPTION:
Multiple Run
END DESCRIPTION:

--- Stream0780.f01 (steady flow) ---

Flow Title=Multiple
Number of Profiles=7
Profile Names=10-year,25-year,50-year,1pct_min,100-year,1pct_plu,500-year
River Rch & RM= Stream0780,Reach-1,15560
     639    1039    1403     917    1830    3652    3088
River Rch & RM= Stream0780,Reach-1,14504
     927    1531    2086    1375    2743    5473    4702
River Rch & RM= Stream0780,Reach-1,5488
    1071    1767    2409    1586    3164    6314    5416
Boundary for River Rch & Prof#=Stream0780,Reach-1,1
Up Type=0
Dn Type=3
Dn Slope=0.005
Boundary for River Rch & Prof#=Stream0780,Reach-1,2
Up Type=0
Dn Type=3
Dn Slope=0.005
Boundary for River Rch & Prof#=Stream0780,Reach-1,3
Up Type=0
Dn Type=3
Dn Slope=0.005
Boundary for River Rch & Prof#=Stream0780,Reach-1,4
Up Type=0
Dn Type=3
Dn Slope=0.005
Boundary for River Rch & Prof#=Stream0780,Reach-1,5
Up Type=0
Dn Type=3
Dn Slope=0.005
Boundary for River Rch & Prof#=Stream0780,Reach-1,6
Up Type=0
Dn Type=3
Dn Slope=0.005
Boundary for River Rch & Prof#=Stream0780,Reach-1,7
Up Type=0
Dn Type=3
Dn Slope=0.005

--- Stream0780.g01 (geometry) ---

Geom Title=Existing Conditions

River Reach=Stream0780,Reach-1
Reach XY= 30
      2405575.00     13602975.00      2406126.56     13603521.26
      2406914.53     13603375.53      2407104.45     13603705.56
      2407321.79     13603767.13      2407580.93     13603577.24
      2408085.57     13603524.29      2408207.78     13603758.76
      2408369.14     13603772.95      2408624.90     13603432.28
      2408971.59     13603717.23      2409317.05     13603628.00
      2409618.94     13604216.86      2410209.94     13604425.71
      2410627.42     13604230.41      2410915.99     13604417.98
      2410914.88     13604764.74      2411209.91     13604625.18
      2411414.70     13604814.90      2411368.49     13605217.37
      2411881.67     13605083.96      2412064.92     13605563.91
      2412773.54     13605578.53      2413121.58     13605967.21
      2413409.78     13605875.25      2414068.97     13606073.38
      2414909.64     13605424.89      2415468.95     13605966.84
      2416109.80     13606275.11      2416375.00     13605675.00

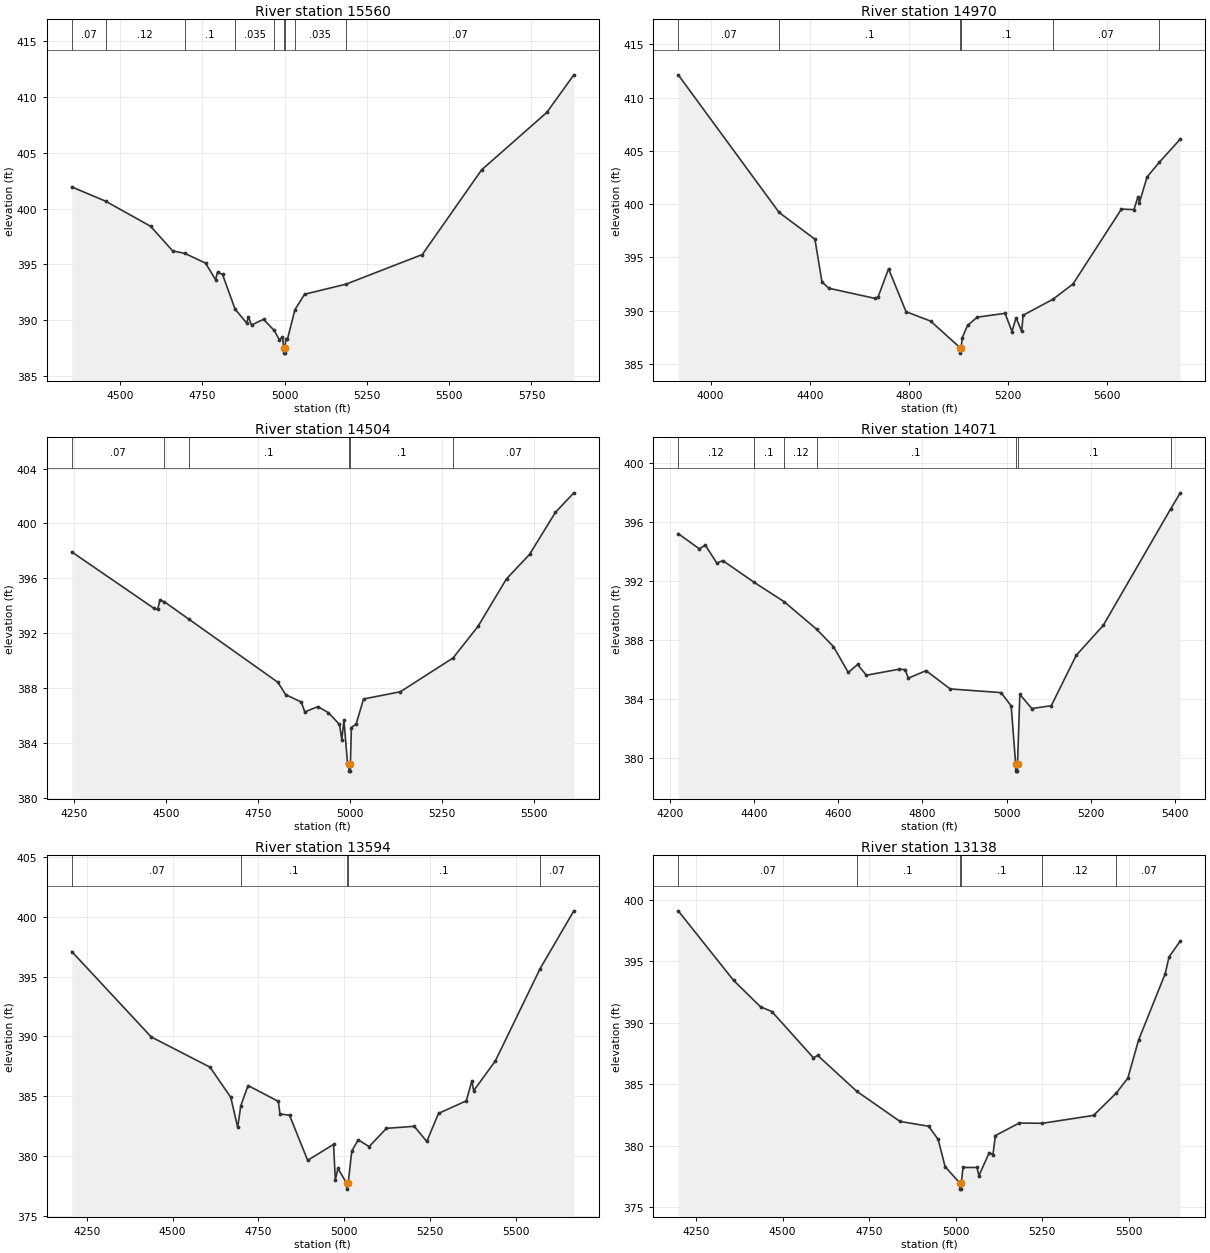
Type RM Length L Ch R = 1,15560,590,590,590
BEGIN DESCRIPTION:
Stream0780 29.0
END DESCRIPTION:
XS GIS Cut Line= 3
      2405083.38     13603375.69      2405633.35     13603025.71
      2405983.35     13602225.71
#Sta/Elev= 30
  4353.7  401.95  4456.7  400.67  4593.2  398.42  4660.1  396.22  4697.3  395.99
  4760.0  395.12  4790.5  393.64  4796.4  394.31  4811.7  394.10  4849.7  391.00
  4884.5  389.76  4890.4  390.29  4899.7  389.57  4936.1  390.08  4968.5  389.09
  4984.4  388.24  4993.7  388.49  4997.6  387.55  4997.9  387.05  5001.4  387.05
  5001.6  387.55  5003.6  388.28  5008.7  388.28  5031.5  390.94  5060.9  392.33
  5186.4  393.23  5418.5  395.89  5598.6  403.48  5796.7  408.63  5878.8  412.00
#Mann=9,-1,0
  4353.7    0.07       0  4456.7    0.12       0  4697.3     0.1       0
  4849.7   0.035       0  4968.5     0.1       0  4997.6    0.05       0
  5001.6     0.1       0  5031.5   0.035       0  5186.4    0.07       0
Bank Sta=4997.6,5001.6
Exp/Cntr=0.3,0.1

Type RM Length L Ch R = 1,14970,466,466,466
BEGIN DESCRIPTION:
Stream0780 28.0
END DESCRIPTION:
XS GIS Cut Line= 3
      2405174.97     13604225.03      2405975.00     13603425.00
      2406374.98     13602625.03
#Sta/Elev= 30
  3869.1  412.15  4276.2  399.22  4420.7  396.71  4449.0  392.70  4477.3  392.10
  4661.1  391.16  4675.2  391.27  4717.7  393.93  4788.4  389.90  4887.4  389.02
  5006.8  386.51  5007.1  386.01  5010.9  386.51  5014.5  387.43  5036.8  388.63
  5076.0  389.39  5187.8  389.75  5215.7  388.04  5232.5  389.34  5254.9  388.05
  5260.5  389.57  5380.3  391.06  5461.7  392.50  5657.4  399.54  5707.7  399.49
  5724.4  400.71  5730.0  400.15  5760.8  402.56  5810.6  403.95  5894.9  406.12
#Mann=6,-1,0
  3869.1    0.07       0  4276.2     0.1       0  5006.8    0.05       0
  5010.9     0.1       0  5380.3    0.07       0  5810.6   0.035       0
Bank Sta=5006.8,5010.9
Exp/Cntr=0.3,0.1

Type RM Length L Ch R = 1,14504,433,433,433
BEGIN DESCRIPTION:
Stream0780 27.0
END DESCRIPTION:
XS GIS Cut Line= 3
      2405974.97     13604075.04      2406375.00     13603425.00
      2406425.00     13602825.05
#Sta/Elev= 30
  4244.2  397.93  4468.4  393.81  4478.0  393.75  4483.9  394.44  4495.9  394.30
  4561.7  393.05  4804.6  388.44  4825.8  387.54  4868.4  387.00  4877.9  386.28
  4913.5  386.67  4941.8  386.23  4972.2  385.37  4978.5  384.26  4984.3  385.70
  4993.9  382.59  4997.6  382.47  4997.9  381.97  5001.7  381.97  5001.9  382.47
  5004.5  385.14  5017.5  385.40  5037.6  387.22  5137.9  387.75  5281.1  390.21
  5348.6  392.50  5426.4  395.97  5489.1  397.75  5559.4  400.81  5609.5  402.23
#Mann=6,-1,0
  4244.2    0.07       0  4495.9    0.12       0  4561.7     0.1       0
  4997.6    0.05       0  5001.9     0.1       0  5281.1    0.07       0
Bank Sta=4997.6,5001.9
Exp/Cntr=0.3,0.1

Type RM Length L Ch R = 1,14071,477,477,477
BEGIN DESCRIPTION:
Stream0780 26.0
END DESCRIPTION:
XS GIS Cut Line= 3
      2406175.03     13603924.97      2406775.00     13603425.00
      2406875.00     13603025.00
#Sta/Elev= 30
  4219.6  395.20  4269.7  394.17  4284.0  394.42  4311.3  393.20  4325.6  393.37
  4399.8  391.90  4471.3  390.58  4548.6  388.71  4588.6  387.53  4623.7  385.78
  4645.9  386.32  4666.7  385.59  4744.8  386.00  4759.1  385.97  4766.3  385.39
  4808.6  385.90  4865.9  384.66  4986.9  384.41  5010.9  383.51  5021.5  379.58
  5021.8  379.08  5025.7  379.08  5026.0  379.58  5031.5  384.29  5059.9  383.33
  5106.2  383.52  5165.5  386.94  5229.9  388.98  5389.6  396.86  5412.9  397.97
#Mann=7,-1,0
  4219.6    0.12       0  4399.8     0.1       0  4471.3    0.12       0
  4548.6     0.1       0  5021.5    0.05       0  5026.0     0.1       0
  5389.6    0.07       0
Bank Sta=5021.5,5026
Exp/Cntr=0.3,0.1

Type RM Length L Ch R = 1,13594,456,456,456
BEGIN DESCRIPTION:
Stream0780 25.0
END DESCRIPTION:
XS GIS Cut Line= 3
      2406975.00     13604425.00      2407075.00     13603625.00
      2406975.00     13602974.98
#Sta/Elev= 30
  4206.0  397.11  4437.8  389.96  4609.1  387.43  4669.6  384.91  4689.7  382.40
  4699.0  384.22  4720.0  385.89  4808.2  384.57  4813.2  383.51  4840.9  383.41
  4893.8  379.63  4969.4  380.97  4974.4  377.99  4982.0  378.95  5007.4  377.72
  5007.8  377.22  5012.0  377.72  5022.3  380.41  5041.3  381.35  5072.9  380.78
  5123.5  382.31  5204.5  382.48  5241.1  381.21  5275.3  383.56  5356.2  384.61
  5372.7  386.29  5377.7  385.46  5441.0  387.95  5571.0  395.65  5669.9  400.52
#Mann=5,-1,0
  4206.0    0.07       0  4699.0     0.1       0  5007.4    0.05       0
  5012.0     0.1       0  5571.0    0.07       0
Bank Sta=5007.4,5012
Exp/Cntr=0.3,0.1

Type RM Length L Ch R = 1,13138,434,434,434
BEGIN DESCRIPTION:
Stream0780 24.0
END DESCRIPTION:
XS GIS Cut Line= 3
      2407475.00     13604475.02      2407425.00     13603675.00
      2407174.99     13603074.99
#Sta/Elev= 30
  4198.2  399.09  4358.5  393.43  4436.2  391.29  4468.8  390.91  4589.0  387.15
  4601.5  387.34  4714.3  384.43  4839.5  381.98  4922.1  381.59  4949.7  380.52
  4969.7  378.31  5012.1  376.98  5012.4  376.48  5016.4  376.48  5016.7  376.98
  5021.5  378.24  5062.1  378.24  5067.5  377.57  5097.3  379.44  5108.1  379.29
  5115.2  380.83  5184.0  381.85  5251.2  381.83  5399.0  382.47  5465.2  384.30
  5498.1  385.50  5529.0  388.58  5605.9  393.97  5617.3  395.35  5649.8  396.64
#Mann=6,-1,0
  4198.2    0.07       0  4714.3     0.1       0  5012.1    0.05       0
  5016.7     0.1       0  5251.2    0.12       0  5465.2    0.07       0
Bank Sta=5012.1,5016.7
Exp/Cntr=0.3,0.1

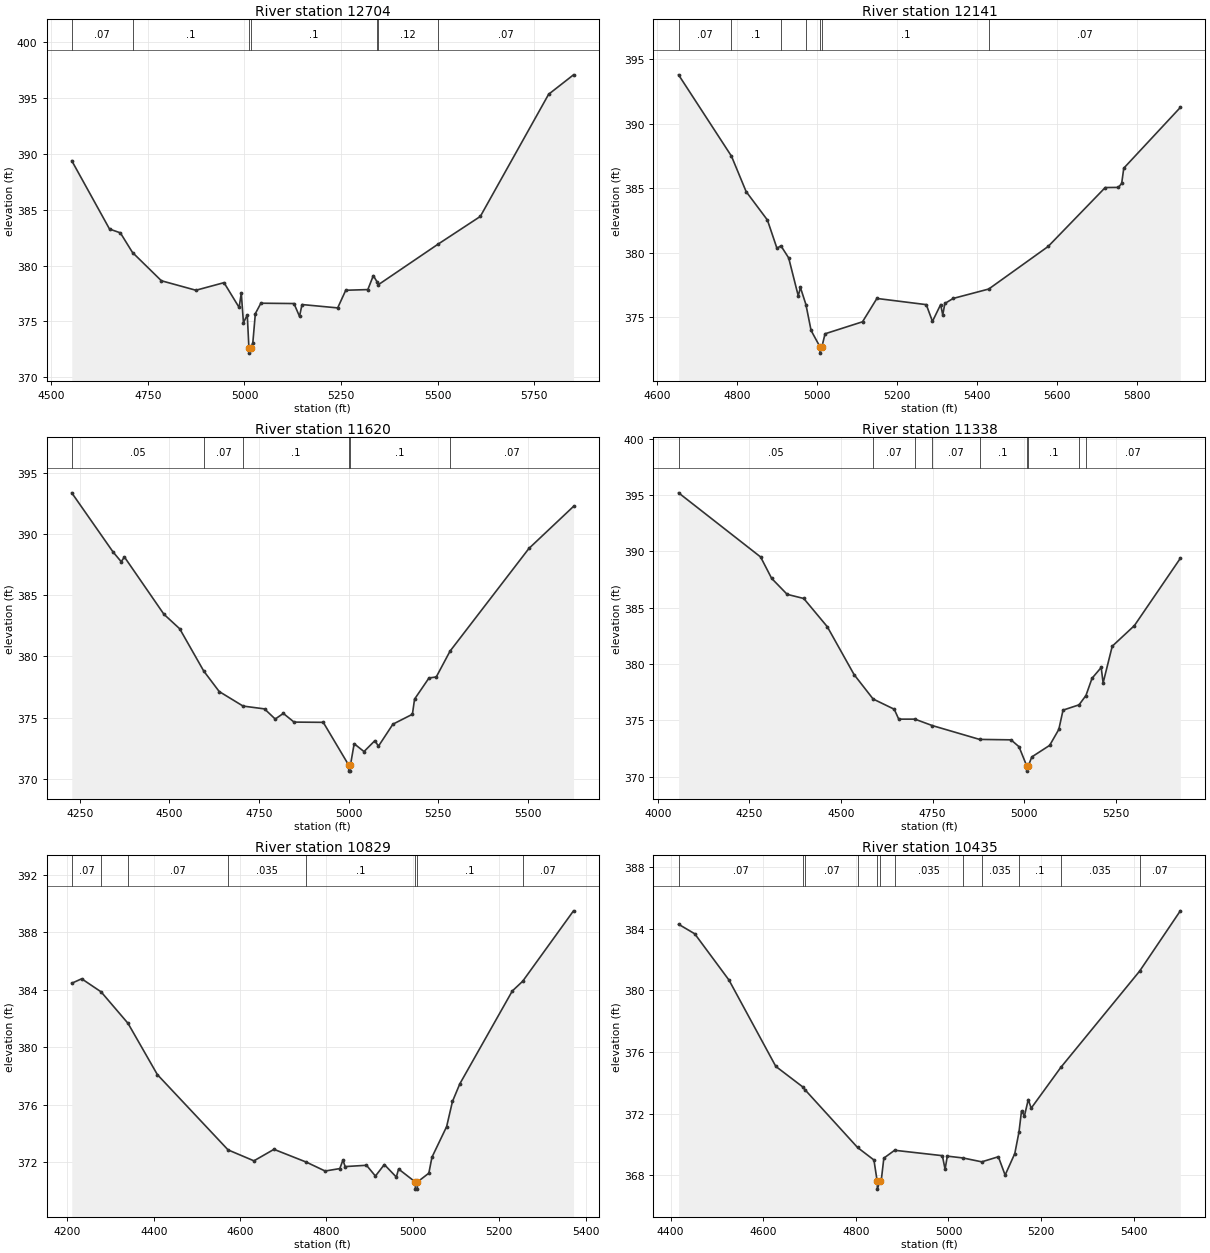
Type RM Length L Ch R = 1,12704,563,563,563
BEGIN DESCRIPTION:
Stream0780 23.0
END DESCRIPTION:
XS GIS Cut Line= 3
      2408024.99     13603974.97      2407825.00     13603575.00
      2407174.97     13603024.97
#Sta/Elev= 30
  4552.9  389.39  4650.7  383.27  4678.7  382.93  4710.2  381.17  4784.9  378.64
  4874.3  377.79  4947.0  378.47  4986.1  376.25  4991.7  377.53  4997.3  374.88
  5007.2  375.58  5011.4  372.66  5011.8  372.16  5016.1  372.66  5021.5  373.05
  5028.1  375.70  5042.4  376.63  5128.1  376.60  5142.4  375.45  5148.9  376.51
  5241.2  376.21  5262.1  377.79  5319.2  377.85  5333.5  379.10  5343.7  378.51
  5346.2  378.28  5501.6  381.93  5610.4  384.40  5787.2  395.34  5851.6  397.08
#Mann=7,-1,0
  4552.9    0.07       0  4710.2     0.1       0  5011.4    0.05       0
  5016.1     0.1       0  5343.7    0.07       0  5346.2    0.12       0
  5501.6    0.07       0
Bank Sta=5011.4,5016.1
Exp/Cntr=0.3,0.1

Type RM Length L Ch R = 1,12141,521,521,521
BEGIN DESCRIPTION:
Stream0780 22.0
END DESCRIPTION:
XS GIS Cut Line= 3
      2408074.99     13604075.04      2408195.75     13603784.49
      2408425.00     13602874.98
#Sta/Elev= 30
  4654.5  393.80  4786.6  387.49  4823.1  384.75  4876.3  382.54  4900.1  380.35
  4910.1  380.54  4929.4  379.60  4953.3  376.66  4958.7  377.31  4972.4  375.99
  4985.3  373.98  5007.3  372.72  5007.7  372.22  5012.4  372.72  5020.2  373.72
  5113.7  374.65  5149.6  376.46  5272.9  375.98  5288.3  374.68  5308.8  375.99
  5314.0  375.18  5319.3  376.07  5339.9  376.46  5428.8  377.19  5577.1  380.49
  5719.6  385.06  5752.4  385.07  5760.7  385.38  5765.9  386.56  5907.1  391.27
#Mann=7,-1,0
  4654.5    0.07       0  4786.6     0.1       0  4910.1    0.07       0
  4972.4     0.1       0  5007.3    0.05       0  5012.4     0.1       0
  5428.8    0.07       0
Bank Sta=5007.3,5012.4
Exp/Cntr=0.3,0.1

Type RM Length L Ch R = 1,11620,282,282,282
BEGIN DESCRIPTION:
Stream0780 21.0
END DESCRIPTION:
XS GIS Cut Line= 3
      2408279.75     13604196.95      2408570.00     13603647.01
      2408475.00     13602874.96
#Sta/Elev= 30
  4227.6  393.38  4342.9  388.54  4365.5  387.75  4374.6  388.13  4484.7  383.45
  4528.8  382.26  4595.7  378.81  4638.9  377.13  4705.5  375.94  4765.3  375.71
  4795.2  374.88  4817.8  375.34  4847.7  374.63  4929.2  374.61  5000.0  371.12
  5000.4  370.62  5004.8  370.62  5005.1  371.12  5015.4  372.86  5042.9  372.22
  5073.1  373.11  5083.2  372.66  5123.5  374.46  5177.9  375.27  5183.9  376.51
  5224.2  378.24  5244.4  378.32  5282.8  380.43  5502.9  388.83  5627.3  392.27
#Mann=6,-1,0
  4227.6    0.05       0  4595.7    0.07       0  4705.5     0.1       0
  5000.0    0.05       0  5005.1     0.1       0  5282.8    0.07       0
Bank Sta=5000,5005.1
Exp/Cntr=0.3,0.1

Type RM Length L Ch R = 1,11338,509,509,509
BEGIN DESCRIPTION:
Stream0780 20.0
END DESCRIPTION:
XS GIS Cut Line= 3
      2408274.98     13604325.03      2408775.00     13603525.00
      2408924.99     13603125.03
#Sta/Elev= 30
  4056.3  395.21  4280.4  389.51  4310.5  387.61  4352.9  386.19  4398.3  385.82
  4462.6  383.31  4535.7  379.06  4587.7  376.89  4645.4  375.98  4657.7  375.10
  4701.8  375.10  4749.2  374.53  4878.4  373.30  4964.4  373.26  4986.2  372.65
  5006.9  370.98  5007.3  370.48  5012.1  370.98  5021.1  371.74  5070.0  372.77
  5095.0  374.19  5106.5  375.90  5150.2  376.37  5169.1  377.20  5185.7  378.73
  5210.7  379.69  5216.0  378.32  5240.9  381.58  5301.4  383.41  5426.9  389.39
#Mann=9,-1,0
  4056.3    0.05       0  4587.7    0.07       0  4701.8     0.1       0
  4749.2    0.07       0  4878.4     0.1       0  5006.9    0.05       0
  5012.1     0.1       0  5150.2   0.035       0  5169.1    0.07       0
Bank Sta=5006.9,5012.1
Exp/Cntr=0.3,0.1

Type RM Length L Ch R = 1,10829,394,394,394
BEGIN DESCRIPTION:
Stream0780 19.0
END DESCRIPTION:
XS GIS Cut Line= 3
      2408967.16     13604357.36      2409181.02     13603501.89
      2409225.01     13603224.96
#Sta/Elev= 30
  4210.0  384.45  4233.0  384.76  4278.0  383.85  4340.3  381.66  4408.3  378.09
  4572.1  372.85  4632.0  372.09  4678.4  372.89  4753.3  372.00  4796.9  371.38
  4830.9  371.55  4838.1  372.14  4843.3  371.69  4892.7  371.78  4913.4  371.03
  4934.0  371.83  4961.8  370.96  4967.0  371.52  5005.6  370.62  5006.0  370.12
  5010.4  370.12  5010.8  370.62  5037.1  371.23  5044.3  372.34  5078.3  374.47
  5091.8  376.22  5108.9  377.45  5230.4  383.91  5254.5  384.59  5372.2  389.49
#Mann=8,-1,0
  4210.0    0.07       0  4278.0    0.05       0  4340.3    0.07       0
  4572.1   0.035       0  4753.3     0.1       0  5005.6    0.05       0
  5010.8     0.1       0  5254.5    0.07       0
Bank Sta=5005.6,5010.8
Exp/Cntr=0.3,0.1

Type RM Length L Ch R = 1,10435,448,448,448
BEGIN DESCRIPTION:
Stream0780 18.0
END DESCRIPTION:
XS GIS Cut Line= 3
      2409075.02     13604324.96      2409375.00     13603825.00
      2409675.03     13603424.96
#Sta/Elev= 30
  4417.4  384.28  4452.3  383.66  4526.2  380.66  4627.3  375.06  4685.0  373.74
  4690.8  373.53  4803.8  369.80  4839.1  368.99  4846.2  367.60  4846.6  367.10
  4851.4  367.60  4854.7  367.61  4860.5  369.11  4883.8  369.62  4986.8  369.27
  4992.7  368.39  4997.5  369.24  5031.6  369.12  5071.9  368.87  5107.7  369.20
  5122.3  368.01  5143.2  369.41  5152.2  370.80  5157.7  372.17  5164.0  371.85
  5172.3  372.91  5178.6  372.35  5242.4  374.99  5412.9  381.25  5500.5  385.15
#Mann=12,-1,0
  4417.4    0.07       0  4685.0   0.035       0  4690.8    0.07       0
  4803.8     0.1       0  4846.2   0.035       0  4851.4     0.1       0
  4883.8   0.035       0  5031.6     0.1       0  5071.9   0.035       0
  5152.2     0.1       0  5242.4   0.035       0  5412.9    0.07       0
Bank Sta=4846.2,4851.4
Exp/Cntr=0.3,0.1

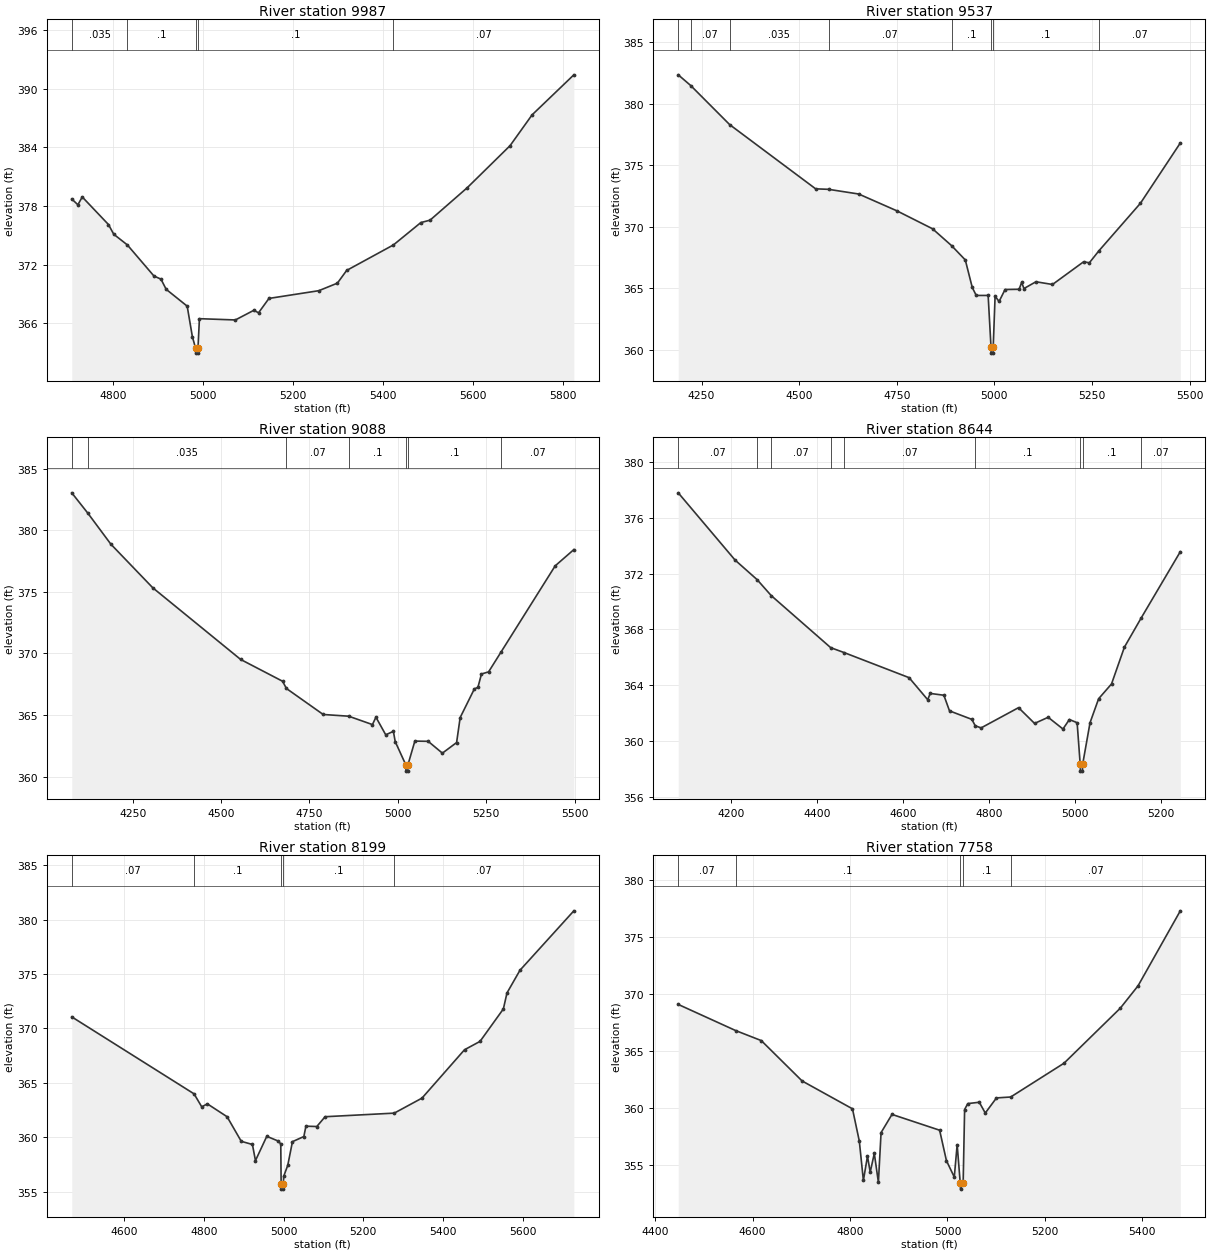
Type RM Length L Ch R = 1,9987,450,450,450
BEGIN DESCRIPTION:
Stream0780 17.0
END DESCRIPTION:
XS GIS Cut Line= 3
      2409325.00     13604325.00      2409575.00     13604175.00
      2409775.01     13603374.97
#Sta/Elev= 30
  4708.7  378.71  4722.3  378.12  4732.0  378.92  4790.3  376.10  4802.0  375.11
  4832.2  374.02  4891.4  370.84  4907.0  370.52  4918.6  369.48  4965.3  367.76
  4976.9  364.62  4984.0  363.46  4984.4  362.96  4988.9  362.96  4989.3  363.46
  4992.5  366.48  5072.4  366.35  5113.6  367.34  5123.9  367.08  5147.1  368.55
  5257.9  369.34  5299.2  370.11  5319.8  371.41  5423.9  374.02  5484.7  376.30
  5505.3  376.55  5587.8  379.86  5683.1  384.16  5732.1  387.31  5824.9  391.40
#Mann=5,-1,0
  4708.7   0.035       0  4832.2     0.1       0  4984.0    0.05       0
  4989.3     0.1       0  5423.9    0.07       0
Bank Sta=4984,4989.3
Exp/Cntr=0.3,0.1

Type RM Length L Ch R = 1,9537,449,449,449
BEGIN DESCRIPTION:
Stream0780 16.0
END DESCRIPTION:
XS GIS Cut Line= 3
      2409825.00     13605125.01      2409975.00     13604325.00
      2410225.03     13603924.96
#Sta/Elev= 30
  4190.3  382.33  4222.3  381.46  4322.0  378.29  4542.2  373.08  4575.1  373.04
  4652.4  372.66  4749.9  371.30  4841.5  369.84  4890.3  368.47  4925.4  367.31
  4943.2  365.08  4953.4  364.43  4983.9  364.43  4991.2  360.25  4991.7  359.75
  4996.5  359.75  4996.9  360.25  5001.7  364.37  5011.9  363.94  5027.2  364.91
  5063.2  364.93  5069.7  365.49  5075.6  364.99  5106.3  365.54  5148.7  365.32
  5228.3  367.16  5243.1  367.08  5267.5  368.05  5373.9  371.91  5476.0  376.80
#Mann=8,-1,0
  4190.3   0.035       0  4222.3    0.07       0  4322.0   0.035       0
  4575.1    0.07       0  4890.3     0.1       0  4991.2    0.05       0
  4996.9     0.1       0  5267.5    0.07       0
Bank Sta=4991.2,4996.9
Exp/Cntr=0.3,0.1

Type RM Length L Ch R = 1,9088,444,444,444
BEGIN DESCRIPTION:
Stream0780 15.0
END DESCRIPTION:
XS GIS Cut Line= 3
      2409925.01     13605174.99      2410375.00     13604375.00
      2410325.00     13603874.96
#Sta/Elev= 30
  4077.6  383.04  4123.0  381.39  4188.2  378.87  4306.7  375.33  4555.3  369.51
  4673.9  367.74  4684.9  367.15  4788.9  365.04  4861.1  364.90  4928.2  364.22
  4938.1  364.82  4965.8  363.39  4987.5  363.67  4992.6  362.84  5022.8  360.94
  5023.2  360.44  5028.0  360.44  5028.5  360.94  5048.2  362.88  5085.9  362.86
  5126.1  361.90  5166.3  362.76  5176.4  364.79  5216.6  367.12  5226.6  367.24
  5236.7  368.33  5256.8  368.50  5292.2  370.12  5445.2  377.11  5498.0  378.43
#Mann=7,-1,0
  4077.6    0.07       0  4123.0   0.035       0  4684.9    0.07       0
  4861.1     0.1       0  5022.8    0.05       0  5028.5     0.1       0
  5292.2    0.07       0
Bank Sta=5022.8,5028.5
Exp/Cntr=0.3,0.1

Type RM Length L Ch R = 1,8644,445,445,445
BEGIN DESCRIPTION:
Stream0780 14.0
END DESCRIPTION:
XS GIS Cut Line= 3
      2410275.01     13605124.98      2410725.00     13604325.00
      2410725.00     13604074.95
#Sta/Elev= 30
  4077.4  377.79  4209.6  372.97  4260.8  371.57  4293.8  370.42  4432.1  366.69
  4463.1  366.34  4614.4  364.54  4657.7  362.96  4663.5  363.41  4695.3  363.28
  4708.4  362.16  4760.4  361.55  4768.3  361.09  4782.0  360.94  4869.0  362.39
  4906.3  361.26  4937.9  361.70  4972.3  360.86  4987.3  361.54  5005.3  361.31
  5012.4  358.34  5012.9  357.84  5017.7  357.84  5018.2  358.34  5035.3  361.31
  5055.3  363.03  5085.3  364.09  5115.3  366.73  5154.3  368.82  5245.3  373.57
#Mann=9,-1,0
  4077.4    0.07       0  4260.8   0.035       0  4293.8    0.07       0
  4432.1   0.035       0  4463.1    0.07       0  4768.3     0.1       0
  5012.4    0.05       0  5018.2     0.1       0  5154.3    0.07       0
Bank Sta=5012.4,5018.2
Exp/Cntr=0.3,0.1

Type RM Length L Ch R = 1,8199,441,441,441
BEGIN DESCRIPTION:
Stream0780 13.0
END DESCRIPTION:
XS GIS Cut Line= 3
      2410525.03     13605024.97      2410875.00     13604625.00
      2411075.01     13603924.98
#Sta/Elev= 30
  4468.7  371.06  4775.5  363.99  4794.7  362.80  4808.9  363.07  4858.3  361.89
  4893.9  359.63  4921.9  359.34  4929.5  357.86  4957.9  360.09  4986.4  359.66
  4993.0  359.39  4993.9  355.74  4994.4  355.24  4999.3  355.24  4999.7  355.74
  5000.2  356.40  5010.6  357.44  5022.3  359.60  5050.9  360.07  5056.1  361.02
  5083.4  360.99  5104.2  361.89  5277.7  362.22  5347.3  363.60  5453.9  368.04
  5492.9  368.81  5551.4  371.79  5560.5  373.26  5593.0  375.34  5728.2  380.80
#Mann=5,-1,0
  4468.7    0.07       0  4775.5     0.1       0  4993.9    0.05       0
  4999.7     0.1       0  5277.7    0.07       0
Bank Sta=4993.9,4999.7
Exp/Cntr=0.3,0.1

Type RM Length L Ch R = 1,7758,451,451,451
BEGIN DESCRIPTION:
Stream0780 12.0
END DESCRIPTION:
XS GIS Cut Line= 3
      2410875.01     13605124.98      2411125.00     13604625.00
      2411375.00     13604224.99
#Sta/Elev= 30
  4447.3  369.10  4565.3  366.80  4617.8  365.92  4701.6  362.37  4805.0  359.92
  4819.0  357.09  4827.4  353.62  4835.8  355.76  4841.4  354.35  4849.8  356.00
  4858.2  353.46  4863.7  357.83  4886.1  359.43  4983.9  358.04  4997.9  355.36
  5014.0  353.92  5019.9  356.77  5026.3  353.36  5026.8  352.86  5032.2  353.36
  5035.2  359.86  5041.7  360.38  5065.3  360.50  5077.6  359.55  5100.6  360.88
  5129.8  360.96  5239.2  363.93  5354.8  368.77  5391.3  370.74  5478.0  377.33
#Mann=5,-1,0
  4447.3    0.07       0  4565.3     0.1       0  5026.3    0.05       0
  5032.2     0.1       0  5129.8    0.07       0
Bank Sta=5026.3,5032.2
Exp/Cntr=0.3,0.1

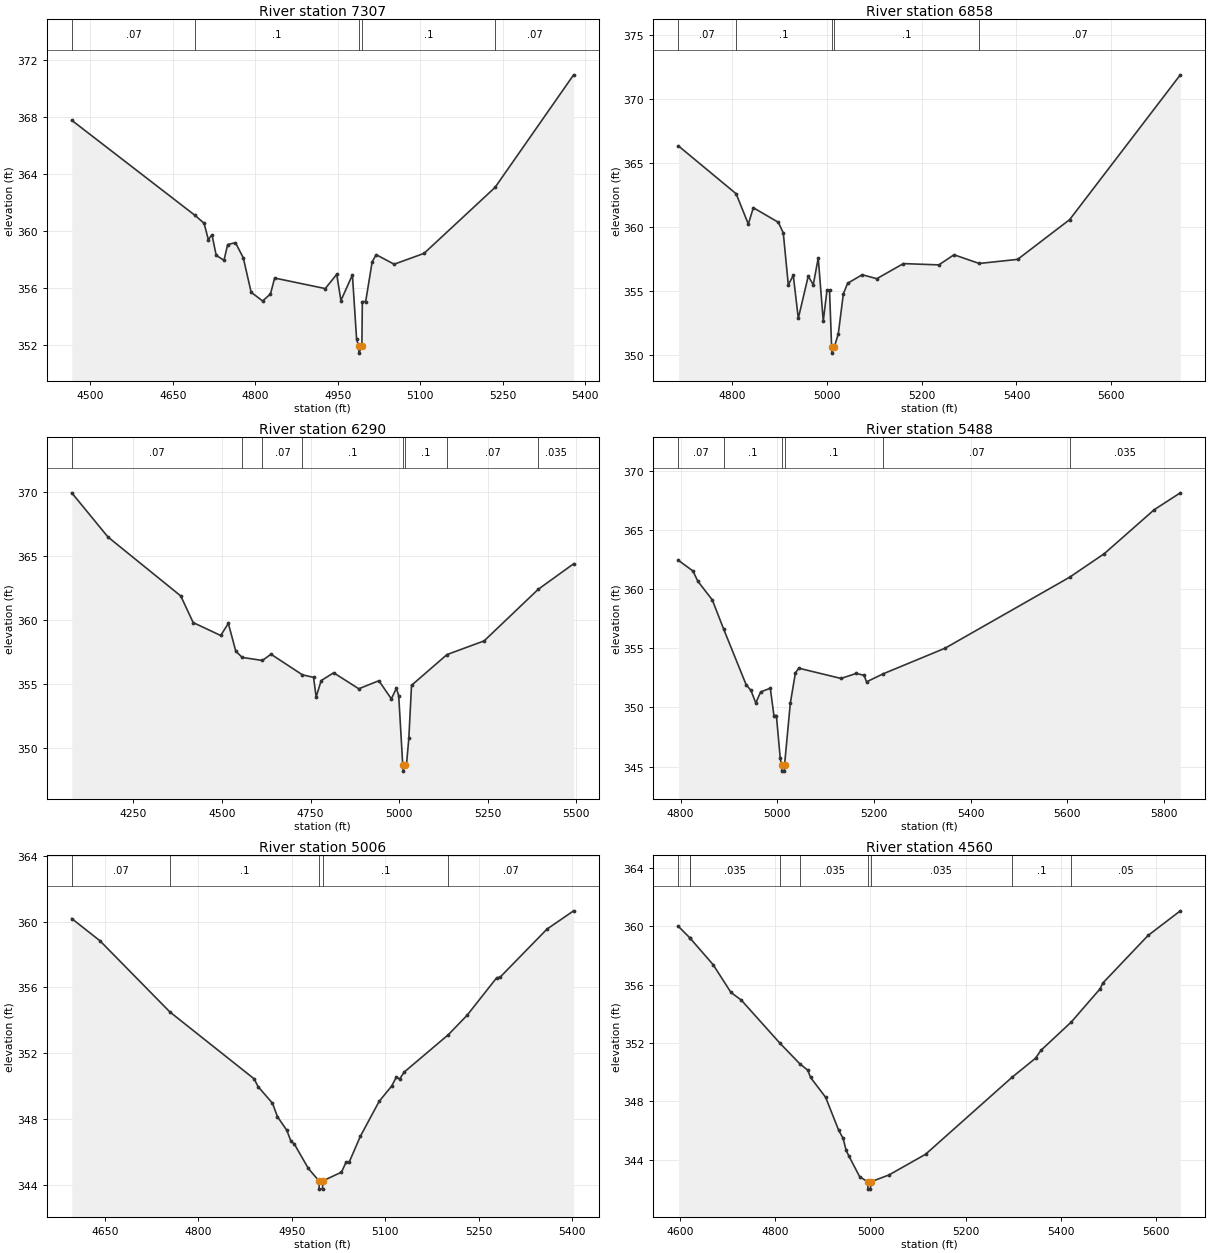
Type RM Length L Ch R = 1,7307,449,449,449
BEGIN DESCRIPTION:
Stream0780 11.0
END DESCRIPTION:
XS GIS Cut Line= 3
      2411024.96     13605225.03      2411425.00     13604875.00
      2411574.98     13604525.04
#Sta/Elev= 30
  4466.3  367.78  4690.6  361.10  4706.9  360.55  4714.5  359.41  4721.2  359.75
  4728.8  358.31  4743.0  357.95  4749.7  359.06  4763.9  359.19  4778.1  358.13
  4792.4  355.71  4813.3  355.10  4827.5  355.59  4835.1  356.71  4927.1  355.97
  4948.0  356.97  4955.6  355.13  4976.5  356.93  4984.1  352.41  4987.8  351.94
  4988.3  351.44  4993.7  351.94  4994.5  355.06  5000.6  355.06  5012.4  357.85
  5019.6  358.35  5052.3  357.68  5106.7  358.44  5235.8  363.07  5378.6  370.97
#Mann=5,-1,0
  4466.3    0.07       0  4690.6     0.1       0  4987.8    0.05       0
  4993.7     0.1       0  5235.8    0.07       0
Bank Sta=4987.8,4993.7
Exp/Cntr=0.3,0.1

Type RM Length L Ch R = 1,6858,568,568,568
BEGIN DESCRIPTION:
Stream0780 10.0
END DESCRIPTION:
XS GIS Cut Line= 3
      2411125.02     13605324.99      2411425.00     13605225.00
      2411675.00     13604525.00
#Sta/Elev= 30
  4686.4  366.31  4808.2  362.57  4833.9  360.20  4844.5  361.48  4897.2  360.34
  4907.7  359.51  4918.3  355.44  4928.8  356.20  4939.4  352.83  4960.4  356.13
  4971.0  355.46  4981.5  357.55  4992.1  352.60  5000.0  355.05  5005.3  355.05
  5009.7  350.61  5010.2  350.11  5015.6  350.61  5023.8  351.61  5034.5  354.74
  5043.5  355.57  5074.3  356.24  5105.1  355.93  5161.3  357.11  5236.2  357.01
  5268.1  357.80  5321.3  357.12  5402.4  357.44  5512.3  360.55  5745.9  371.87
#Mann=5,-1,0
  4686.4    0.07       0  4808.2     0.1       0  5009.7    0.05       0
  5015.6     0.1       0  5321.3    0.07       0
Bank Sta=5009.7,5015.6
Exp/Cntr=0.3,0.1

Type RM Length L Ch R = 1,6290,802,802,802
BEGIN DESCRIPTION:
Stream0780 9.0
END DESCRIPTION:
XS GIS Cut Line= 3
      2411278.45     13605782.65      2411878.46     13605132.64
      2412228.45     13604732.65
#Sta/Elev= 30
  4076.3  369.93  4178.5  366.48  4383.8  361.88  4418.9  359.80  4496.6  358.79
  4518.1  359.74  4539.1  357.57  4557.1  357.08  4614.3  356.84  4638.4  357.33
  4727.1  355.72  4758.6  355.52  4765.9  353.99  4780.1  355.27  4815.3  355.88
  4886.2  354.63  4942.9  355.26  4978.1  353.84  4992.3  354.67  4998.9  354.08
  5010.2  348.70  5010.7  348.20  5016.2  348.70  5020.8  348.72  5027.4  350.76
  5035.0  354.90  5135.0  357.30  5240.0  358.37  5392.6  362.40  5492.4  364.39
#Mann=8,-1,0
  4076.3    0.07       0  4557.1     0.1       0  4614.3    0.07       0
  4727.1     0.1       0  5010.2    0.05       0  5016.2     0.1       0
  5135.0    0.07       0  5392.6   0.035       0
Bank Sta=5010.2,5016.2
Exp/Cntr=0.3,0.1

Type RM Length L Ch R = 1,5488,482,482,482
BEGIN DESCRIPTION:
Stream0780 8.0
END DESCRIPTION:
XS GIS Cut Line= 3
      2412275.00     13605775.02      2412275.00     13605575.00
      2412525.01     13604774.97
#Sta/Elev= 30
  4795.4  362.46  4825.4  361.56  4835.4  360.70  4865.4  359.11  4888.7  356.66
  4935.4  351.93  4945.4  351.44  4955.4  350.38  4965.4  351.32  4985.4  351.63
  4992.9  349.32  4998.0  349.32  5005.9  345.72  5008.6  345.11  5009.1  344.61
  5014.3  344.61  5014.8  345.11  5026.8  350.36  5037.3  352.92  5044.1  353.33
  5131.6  352.46  5163.0  352.88  5179.3  352.73  5184.5  352.17  5219.4  352.86
  5346.9  355.02  5604.5  361.03  5676.4  363.03  5779.6  366.75  5833.6  368.18
#Mann=6,-1,0
  4795.4    0.07       0  4888.7     0.1       0  5008.6    0.05       0
  5014.8     0.1       0  5219.4    0.07       0  5604.5   0.035       0
Bank Sta=5008.6,5014.8
Exp/Cntr=0.3,0.1

Type RM Length L Ch R = 1,5006,446,446,446
BEGIN DESCRIPTION:
Stream0780 7.0
END DESCRIPTION:
XS GIS Cut Line= 3
      2412525.02     13605924.96      2412725.00     13605575.00
      2412775.00     13605174.98
#Sta/Elev= 30
  4596.5  360.18  4641.8  358.83  4754.1  354.51  4889.4  350.45  4895.9  349.97
  4918.9  348.97  4926.9  348.15  4942.0  347.32  4948.5  346.67  4954.2  346.48
  4976.5  345.01  4993.6  344.25  4994.1  343.75  4999.3  343.75  4999.8  344.25
  5029.8  344.78  5037.4  345.41  5042.4  345.41  5060.0  346.95  5090.3  349.08
  5110.4  350.01  5118.0  350.56  5123.0  350.43  5130.6  350.86  5201.2  353.12
  5231.4  354.30  5279.2  356.59  5284.3  356.61  5359.9  359.54  5402.7  360.65
#Mann=5,-1,0
  4596.5    0.07       0  4754.1     0.1       0  4993.6    0.05       0
  4999.8     0.1       0  5201.2    0.07       0
Bank Sta=4993.6,4999.8
Exp/Cntr=0.3,0.1

Type RM Length L Ch R = 1,4560,418,418,418
BEGIN DESCRIPTION:
Stream0780 6.0
END DESCRIPTION:
XS GIS Cut Line= 3
      2412674.98     13606075.01      2413025.00     13605875.00
      2413274.99     13605275.03
#Sta/Elev= 30
  4597.1  359.99  4620.9  359.21  4621.9  359.17  4669.8  357.37  4707.3  355.46
  4728.9  354.94  4810.3  351.97  4852.3  350.55  4868.5  350.13  4874.3  349.63
  4905.9  348.27  4933.3  346.01  4942.6  345.45  4949.1  344.62  4954.9  344.23
  4977.2  342.83  4994.2  342.47  4994.7  341.97  5000.0  341.97  5000.5  342.47
  5038.7  342.94  5115.6  344.36  5297.0  349.64  5346.4  350.95  5357.7  351.49
  5421.6  353.44  5481.8  355.71  5487.7  356.11  5582.5  359.37  5650.2  361.06
#Mann=9,-1,0
  4597.1   0.035       0  4620.9    0.07       0  4621.9   0.035       0
  4810.3    0.07       0  4852.3   0.035       0  4994.2   0.035       0
  5000.5   0.035       0  5297.0     0.1       0  5421.6    0.05       0
Bank Sta=4994.2,5000.5
Exp/Cntr=0.3,0.1

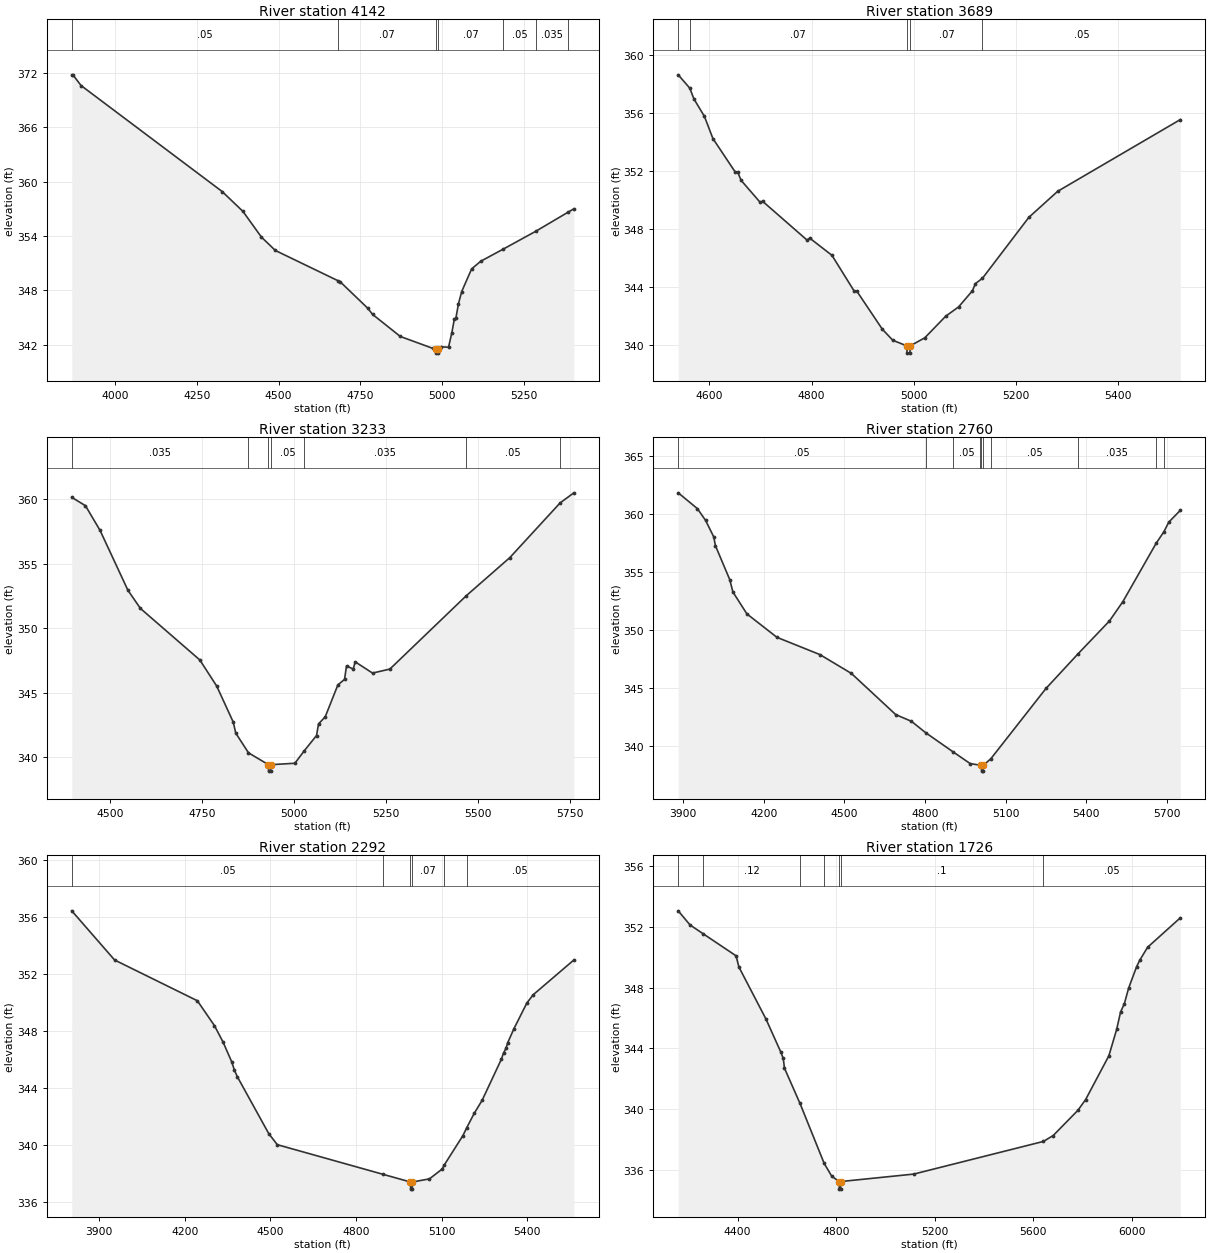
Type RM Length L Ch R = 1,4142,453,453,453
BEGIN DESCRIPTION:
Stream0780 5.0
END DESCRIPTION:
XS GIS Cut Line= 3
      2412575.00     13606675.00      2413375.00     13605875.00
      2413425.00     13605474.99
#Sta/Elev= 30
  3867.8  371.78  3871.3  371.78  3896.1  370.60  4327.4  358.90  4391.1  356.70
  4447.6  353.86  4490.1  352.39  4680.5  349.07  4688.1  348.94  4772.9  346.00
  4787.0  345.34  4871.9  342.90  4970.9  341.59  4981.8  341.56  4982.3  341.06
  4987.8  341.06  4988.3  341.56  4995.6  341.76  5019.3  341.71  5029.4  343.31
  5037.0  344.80  5042.0  344.96  5049.6  346.50  5059.6  347.86  5089.9  350.36
  5117.6  351.20  5186.4  352.54  5285.4  354.50  5384.3  356.61  5402.3  356.99
#Mann=7,-1,0
  3867.8    0.05       0  4680.5    0.07       0  4981.8    0.05       0
  4988.3    0.07       0  5186.4    0.05       0  5285.4   0.035       0
  5384.3    0.05       0
Bank Sta=4981.8,4988.3
Exp/Cntr=0.3,0.1

Type RM Length L Ch R = 1,3689,456,456,456
BEGIN DESCRIPTION:
Stream0780 4.0
END DESCRIPTION:
XS GIS Cut Line= 3
      2413875.01     13606475.04      2413775.00     13606025.00
      2413625.01     13605525.03
#Sta/Elev= 30
  4539.0  358.65  4561.6  357.73  4569.8  356.98  4590.3  355.78  4606.9  354.25
  4650.4  351.95  4655.6  351.92  4662.0  351.37  4699.1  349.86  4704.2  349.92
  4791.3  347.24  4796.4  347.38  4840.0  346.19  4883.5  343.72  4888.6  343.72
  4938.6  341.09  4959.0  340.33  4986.5  339.94  4987.0  339.44  4992.6  339.44
  4993.1  339.94  5021.8  340.50  5062.7  341.99  5087.9  342.63  5114.9  343.74
  5120.9  344.24  5134.7  344.61  5225.4  348.81  5281.9  350.61  5522.0  355.56
#Mann=5,-1,0
  4539.0   0.035       0  4561.6    0.07       0  4986.5    0.05       0
  4993.1    0.07       0  5134.7    0.05       0
Bank Sta=4986.5,4993.1
Exp/Cntr=0.3,0.1

Type RM Length L Ch R = 1,3233,473,473,473
BEGIN DESCRIPTION:
Stream0780 3.0
END DESCRIPTION:
XS GIS Cut Line= 3
      2413925.01     13606524.99      2414175.00     13605975.00
      2413875.01     13605275.02
#Sta/Elev= 30
  4395.6  360.14  4432.9  359.49  4472.5  357.58  4548.3  352.94  4582.3  351.53
  4743.8  347.54  4789.9  345.51  4835.0  342.71  4841.6  341.87  4876.3  340.34
  4930.5  339.42  4931.0  338.92  4936.6  338.92  4937.1  339.42  5002.5  339.53
  5028.1  340.50  5061.4  341.68  5066.8  342.58  5085.0  343.13  5119.4  345.60
  5137.5  346.03  5143.0  347.08  5161.1  346.83  5166.6  347.39  5213.7  346.52
  5260.9  346.83  5468.5  352.51  5587.2  355.47  5724.0  359.71  5761.3  360.49
#Mann=7,-1,0
  4395.6   0.035       0  4876.3    0.05       0  4930.5    0.05       0
  4937.1    0.05       0  5028.1   0.035       0  5468.5    0.05       0
  5724.0   0.035       0
Bank Sta=4930.5,4937.1
Exp/Cntr=0.3,0.1

Type RM Length L Ch R = 1,2760,468,468,468
BEGIN DESCRIPTION:
Stream0780 2.0
END DESCRIPTION:
XS GIS Cut Line= 3
      2414725.01     13606825.04      2414525.00     13605725.00
      2413924.98     13605274.99
#Sta/Elev= 30
  3881.7  361.83  3952.9  360.47  3983.4  359.46  4013.9  358.03  4020.2  357.27
  4073.6  354.34  4085.0  353.29  4137.1  351.40  4248.9  349.38  4409.0  347.89
  4525.9  346.27  4691.0  342.72  4749.5  342.14  4801.8  341.17  4902.5  339.54
  4968.0  338.50  5005.5  338.36  5010.0  338.35  5010.5  337.85  5016.2  337.85
  5016.7  338.35  5044.6  338.91  5249.8  344.97  5370.2  347.98  5486.2  350.79
  5536.2  352.46  5660.3  357.50  5688.6  358.47  5707.1  359.31  5749.8  360.32
#Mann=10,-1,0
  3881.7    0.05       0  4801.8    0.07       0  4902.5    0.05       0
  5005.5     0.1       0  5010.0    0.05       0  5016.7     0.1       0
  5044.6    0.05       0  5370.2   0.035       0  5660.3    0.05       0
  5688.6   0.035       0
Bank Sta=5010,5016.7
Exp/Cntr=0.3,0.1

Type RM Length L Ch R = 1,2292,566,566,566
BEGIN DESCRIPTION:
Stream0780 1.0
END DESCRIPTION:
XS GIS Cut Line= 3
      2414875.00     13606625.02      2414875.00     13605425.00
      2414375.03     13605175.02
#Sta/Elev= 30
  3803.9  356.41  3953.9  352.96  4243.9  350.10  4303.9  348.35  4333.9  347.20
  4363.9  345.83  4373.9  345.22  4383.9  344.77  4493.9  340.78  4523.9  340.00
  4894.2  337.92  4990.6  337.38  4991.1  336.88  4996.8  336.88  4997.3  337.38
  5057.0  337.60  5101.7  338.29  5107.8  338.54  5174.4  340.64  5186.9  341.16
  5213.6  342.19  5241.5  343.11  5308.6  345.98  5317.0  346.45  5325.4  346.77
  5330.9  347.14  5353.3  348.15  5398.0  349.93  5420.4  350.52  5562.9  352.96
#Mann=6,-1,0
  3803.9    0.05       0  4894.2    0.07       0  4990.6    0.05       0
  4997.3    0.07       0  5107.8    0.07       0  5186.9    0.05       0
Bank Sta=4990.6,4997.3
Exp/Cntr=0.3,0.1

Type RM Length L Ch R = 1,1726,0,0,0
BEGIN DESCRIPTION:
H21048
END DESCRIPTION:
XS GIS Cut Line= 4
      2415247.69     13606631.06      2415297.15     13605675.90
      2414910.77     13605261.70      2414418.14     13605107.76
#Sta/Elev= 30
  4159.0  353.05  4206.9  352.12  4259.3  351.55  4393.7  350.09  4405.4  349.35
  4515.5  345.92  4575.6  343.75  4585.5  343.33  4590.5  342.69  4653.3  340.38
  4751.8  336.42  4782.4  335.58  4812.6  335.23  4813.1  334.73  4818.8  334.73
  4819.3  335.23  5115.4  335.72  5642.0  337.87  5681.9  338.26  5782.2  339.92
  5813.6  340.63  5907.9  343.51  5939.4  345.24  5955.4  346.39  5970.8  346.94
  5987.9  347.95  6020.4  349.37  6033.7  349.81  6065.1  350.65  6198.0  352.59
#Mann=7,-1,0
  4159.0   0.035       0  4259.3    0.12       0  4653.3    0.07       0
  4751.8     0.1       0  4812.6    0.05       0  4819.3     0.1       0
  5642.0    0.05       0
Bank Sta=4812.6,4819.3
Exp/Cntr=0.3,0.1

Chan Stop Cuts=-1