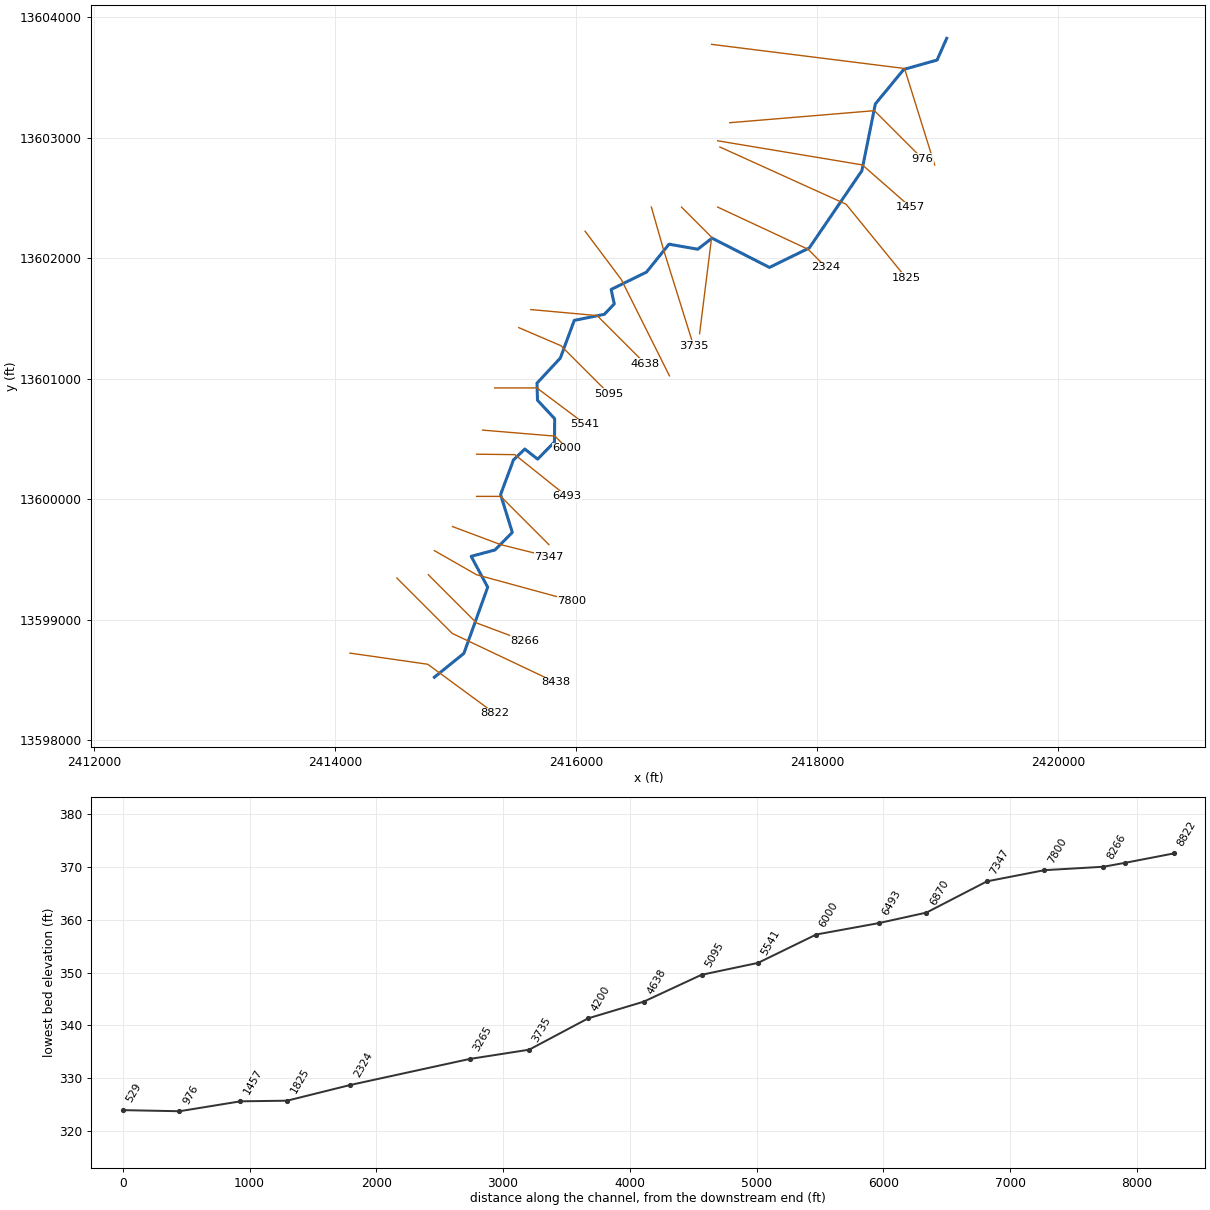
--- Stream0781.prj (project) ---

Proj Title=Stream0781 Base Level Engineering
Current Plan=p01
Default Exp/Contr=0.3,0.1
English Units
Geom File=g01
Flow File=f01
Plan File=p01
BEGIN DESCRIPTION:
Stream0781
END DESCRIPTION:

--- Stream0781.p01 (plan) ---

Plan Title=Multiple Run
Short Identifier=Multiple
Geom File=g01
Flow File=f01
Subcritical Flow
K Sum by GR= 0
Std Step Tol= 0.01
Critical Tol= 0.01
Num of Std Step Trials= 20
Max Error Tol= 0.3
Flow Tol Ratio= 0.001
Split Flow NTrial= 30
Split Flow Tol= 0.02
Split Flow Ratio= 0.02
Log Output Level= 0
Friction Slope Method= 1
Unsteady Friction Slope Method= 2
Unsteady Bridges Friction Slope Method= 1
Parabolic Critical Depth
Global Vel Dist=  1 , 1 , 1
Global Log Level= 0
CheckData=True
Encroach Param= -1, 0, 0, 0
BEGIN DESCRIPTION:
Multiple Run
END DESCRIPTION:

--- Stream0781.f01 (steady flow) ---

Flow Title=Multiple
Number of Profiles=7
Profile Names=10-year,25-year,50-year,1pct_min,100-year,1pct_plu,500-year
River Rch & RM= Stream0781,Reach-1,8822
     806    1338    1832    1216    2426    4840    4215
River Rch & RM= Stream0781,Reach-1,8438
    1045    1745    2399    1596    3184    6353    5559
Boundary for River Rch & Prof#=Stream0781,Reach-1,1
Up Type=0
Dn Type=3
Dn Slope=0.005
Boundary for River Rch & Prof#=Stream0781,Reach-1,2
Up Type=0
Dn Type=3
Dn Slope=0.005
Boundary for River Rch & Prof#=Stream0781,Reach-1,3
Up Type=0
Dn Type=3
Dn Slope=0.005
Boundary for River Rch & Prof#=Stream0781,Reach-1,4
Up Type=0
Dn Type=3
Dn Slope=0.005
Boundary for River Rch & Prof#=Stream0781,Reach-1,5
Up Type=0
Dn Type=3
Dn Slope=0.005
Boundary for River Rch & Prof#=Stream0781,Reach-1,6
Up Type=0
Dn Type=3
Dn Slope=0.005
Boundary for River Rch & Prof#=Stream0781,Reach-1,7
Up Type=0
Dn Type=3
Dn Slope=0.005

--- Stream0781.g01 (geometry) ---

Geom Title=Existing Conditions

River Reach=Stream0781,Reach-1
Reach XY= 30
      2414825.00     13598525.00      2415069.48     13598722.56
      2415267.16     13599271.77      2415130.28     13599527.71
      2415327.45     13599580.47      2415471.47     13599726.47
      2415374.27     13600040.06      2415480.83     13600327.33
      2415574.99     13600417.91      2415681.59     13600334.23
      2415821.26     13600476.52      2415822.94     13600669.15
      2415680.45     13600822.55      2415676.19     13600964.50
      2415869.58     13601172.33      2415985.36     13601485.16
      2416234.85     13601535.48      2416317.19     13601621.58
      2416291.21     13601741.71      2416584.68     13601885.76
      2416771.33     13602117.31      2417009.84     13602075.39
      2417128.33     13602167.39      2417604.84     13601924.54
      2417934.68     13602085.78      2418371.24     13602726.56
      2418483.16     13603281.05      2418718.81     13603567.18
      2418995.18     13603644.78      2419075.00     13603825.00

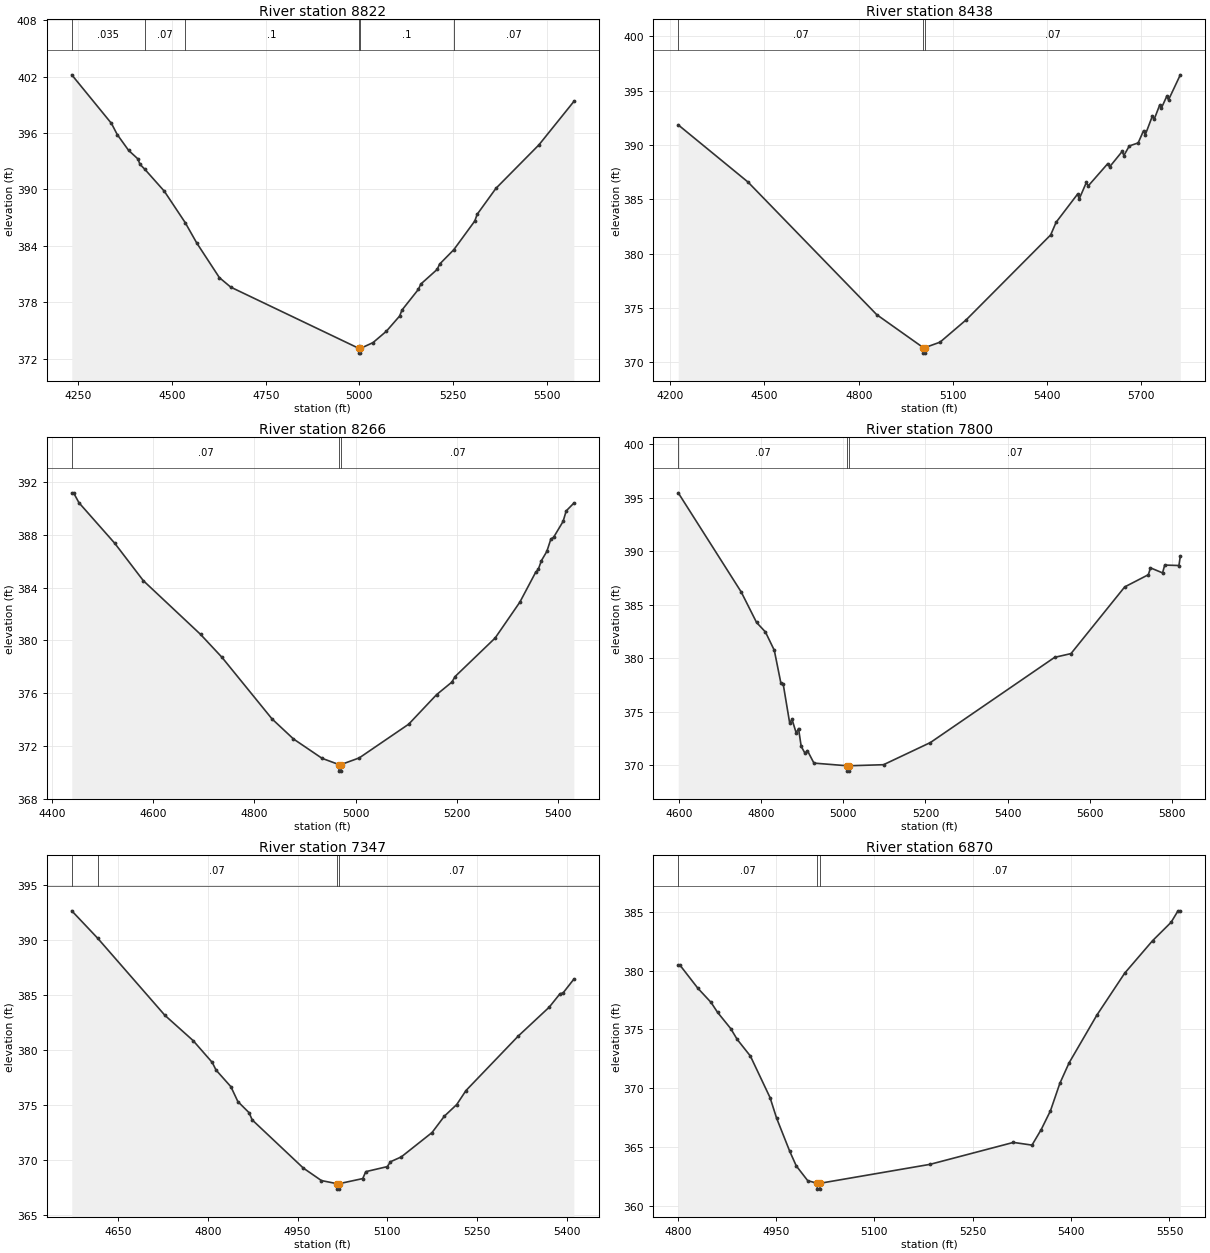
Type RM Length L Ch R = 1,8822,384,384,384
BEGIN DESCRIPTION:
Stream0781 18.0
END DESCRIPTION:
XS GIS Cut Line= 3
      2414124.98     13598725.00      2414769.69     13598632.52
      2415324.99     13598225.01
#Sta/Elev= 30
  4232.4  402.18  4338.3  397.02  4353.7  395.84  4384.0  394.16  4408.9  393.25
  4414.3  392.68  4427.6  392.14  4479.4  389.82  4535.2  386.48  4565.8  384.33
  4626.4  380.64  4656.7  379.63  4999.0  373.12  4999.3  372.62  5002.8  372.62
  5003.0  373.12  5036.5  373.74  5072.0  374.94  5107.5  376.56  5113.7  377.19
  5157.7  379.40  5163.9  379.95  5207.9  381.52  5214.1  382.07  5252.2  383.61
  5308.2  386.66  5314.4  387.36  5364.5  390.12  5479.5  394.75  5572.5  399.35
#Mann=6,-1,0
  4232.4   0.035       0  4427.6    0.07       0  4535.2     0.1       0
  4999.0    0.05       0  5003.0     0.1       0  5252.2    0.07       0
Bank Sta=4999,5003
Exp/Cntr=0.3,0.1

Type RM Length L Ch R = 1,8438,172,172,172
BEGIN DESCRIPTION:
XS7721
END DESCRIPTION:
XS GIS Cut Line= 3
      2414513.78     13599347.63      2414972.94     13598888.47
      2415830.54     13598482.24
#Sta/Elev= 30
  4225.5  391.86  4447.4  386.60  4857.5  374.38  5005.8  371.34  5006.1  370.84
  5009.8  370.84  5010.1  371.34  5058.9  371.85  5142.7  373.92  5411.2  381.73
  5428.4  382.89  5496.6  385.48  5502.1  385.05  5524.9  386.57  5530.4  386.23
  5593.1  388.30  5598.7  387.99  5638.6  389.41  5644.2  389.04  5661.4  389.92
  5689.6  390.20  5706.9  391.33  5712.4  390.96  5735.1  392.69  5740.7  392.38
  5757.9  393.67  5763.4  393.40  5780.6  394.49  5786.2  394.16  5823.8  396.47
#Mann=3,-1,0
  4225.5    0.07       0  5005.8    0.05       0  5010.1    0.07       0
Bank Sta=5005.8,5010.1
Exp/Cntr=0.3,0.1

Type RM Length L Ch R = 1,8266,466,466,466
BEGIN DESCRIPTION:
Stream0781 17.0
END DESCRIPTION:
XS GIS Cut Line= 3
      2414774.98     13599375.02      2415175.00     13598975.00
      2415574.99     13598825.01
#Sta/Elev= 30
  4438.8  391.19  4442.4  391.19  4453.0  390.44  4523.7  387.37  4580.3  384.53
  4693.4  380.46  4735.8  378.72  4834.8  374.05  4877.2  372.53  4933.8  371.06
  4967.0  370.59  4967.3  370.09  4971.0  370.09  4971.3  370.59  5007.2  371.09
  5105.1  373.65  5160.3  375.89  5190.5  376.84  5196.8  377.26  5276.0  380.18
  5324.9  382.90  5356.1  385.16  5361.4  385.39  5367.6  386.05  5378.3  386.75
  5386.3  387.69  5391.7  387.82  5410.4  389.02  5416.6  389.82  5431.7  390.41
#Mann=3,-1,0
  4438.8    0.07       0  4967.0    0.05       0  4971.3    0.07       0
Bank Sta=4967,4971.3
Exp/Cntr=0.3,0.1

Type RM Length L Ch R = 1,7800,453,453,453
BEGIN DESCRIPTION:
Stream0781 16.0
END DESCRIPTION:
XS GIS Cut Line= 3
      2414825.04     13599574.98      2415175.00     13599375.00
      2415965.65     13599159.73
#Sta/Elev= 30
  4598.0  395.44  4751.3  386.18  4788.7  383.33  4810.3  382.44  4831.9  380.73
  4847.7  377.71  4853.5  377.59  4869.3  373.95  4875.1  374.27  4885.2  373.01
  4890.9  373.42  4897.4  371.75  4906.8  371.10  4912.5  371.36  4928.4  370.19
  5009.2  369.94  5009.5  369.44  5013.3  369.44  5013.6  369.94  5097.9  370.04
  5212.0  372.11  5514.5  380.07  5554.3  380.42  5685.1  386.65  5742.7  387.79
  5747.9  388.43  5777.3  387.96  5782.5  388.69  5817.1  388.65  5820.5  389.52
#Mann=3,-1,0
  4598.0    0.07       0  5009.2    0.05       0  5013.6    0.07       0
Bank Sta=5009.2,5013.6
Exp/Cntr=0.3,0.1

Type RM Length L Ch R = 1,7347,477,477,477
BEGIN DESCRIPTION:
Stream0781 15.0
END DESCRIPTION:
XS GIS Cut Line= 3
      2414975.01     13599775.00      2415375.00     13599625.00
      2415775.00     13599525.00
#Sta/Elev= 30
  4572.5  392.65  4615.6  390.17  4728.2  383.14  4775.4  380.84  4807.4  378.85
  4813.7  378.16  4838.6  376.64  4850.2  375.29  4868.9  374.28  4874.2  373.62
  4959.6  369.24  4989.9  368.10  5015.5  367.82  5015.8  367.32  5019.6  367.32
  5019.9  367.82  5059.0  368.28  5064.1  368.91  5100.2  369.37  5105.3  369.81
  5123.4  370.25  5174.9  372.47  5195.5  373.96  5216.2  375.02  5231.6  376.29
  5319.2  381.26  5370.8  383.88  5388.8  385.10  5394.0  385.18  5412.0  386.43
#Mann=4,-1,0
  4572.5    0.12       0  4615.6    0.07       0  5015.5    0.05       0
  5019.9    0.07       0
Bank Sta=5015.5,5019.9
Exp/Cntr=0.3,0.1

Type RM Length L Ch R = 1,6870,377,377,377
BEGIN DESCRIPTION:
Stream0781 14.0
END DESCRIPTION:
XS GIS Cut Line= 3
      2415174.95     13600025.00      2415375.00     13600025.00
      2415774.98     13599625.02
#Sta/Elev= 30
  4800.8  380.49  4803.3  380.49  4830.8  378.51  4850.8  377.31  4860.8  376.46
  4880.8  375.08  4890.8  374.15  4910.8  372.74  4940.8  369.20  4950.8  367.45
  4970.8  364.63  4980.8  363.38  4998.3  362.12  5012.8  361.90  5013.1  361.40
  5016.9  361.40  5017.2  361.90  5184.7  363.51  5312.0  365.38  5340.3  365.15
  5354.4  366.48  5368.5  368.08  5382.7  370.40  5396.8  372.15  5439.3  376.23
  5481.7  379.80  5524.1  382.56  5552.4  384.13  5563.0  385.11  5566.5  385.11
#Mann=3,-1,0
  4800.8    0.07       0  5012.8    0.05       0  5017.2    0.07       0
Bank Sta=5012.8,5017.2
Exp/Cntr=0.3,0.1

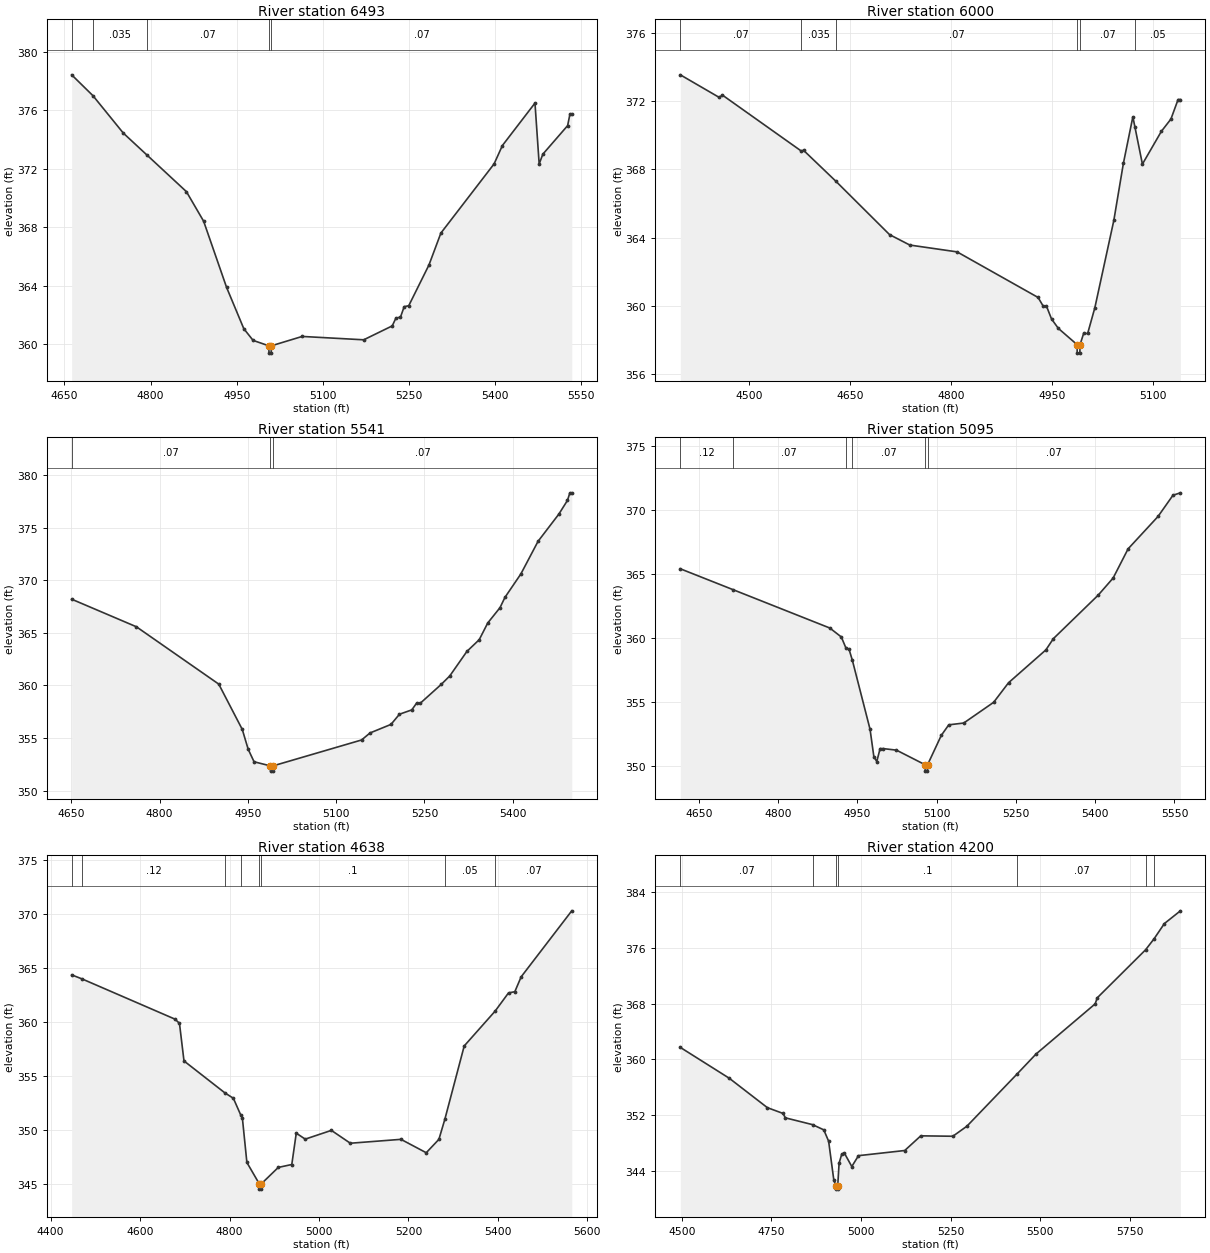
Type RM Length L Ch R = 1,6493,493,493,493
BEGIN DESCRIPTION:
Stream0781 13.0
END DESCRIPTION:
XS GIS Cut Line= 3
      2415175.04     13600375.00      2415492.35     13600371.43
      2415925.01     13600024.99
#Sta/Elev= 30
  4662.5  378.41  4699.7  376.98  4752.5  374.43  4793.2  372.95  4862.5  370.43
  4892.5  368.41  4932.5  363.89  4962.5  361.07  4978.7  360.27  5006.1  359.90
  5006.4  359.40  5010.2  359.40  5010.5  359.90  5064.3  360.54  5171.5  360.31
  5221.2  361.26  5227.6  361.79  5235.6  361.86  5242.0  362.57  5250.0  362.64
  5285.2  365.42  5306.0  367.60  5398.8  372.33  5413.2  373.58  5470.0  376.48
  5477.3  372.32  5483.7  372.99  5526.9  374.94  5530.9  375.72  5534.1  375.72
#Mann=5,-1,0
  4662.5    0.07       0  4699.7   0.035       0  4793.2    0.07       0
  5006.1    0.05       0  5010.5    0.07       0
Bank Sta=5006.1,5010.5
Exp/Cntr=0.3,0.1

Type RM Length L Ch R = 1,6000,459,459,459
BEGIN DESCRIPTION:
Stream0781 12.0
END DESCRIPTION:
XS GIS Cut Line= 3
      2415224.97     13600575.00      2415825.00     13600525.00
      2415924.98     13600425.02
#Sta/Elev= 30
  4397.3  373.54  4455.0  372.22  4460.0  372.35  4577.0  369.08  4580.5  369.12
  4628.5  367.31  4708.4  364.18  4738.5  363.57  4808.8  363.17  4929.2  360.50
  4936.7  360.00  4941.7  359.99  4949.2  359.24  4959.3  358.69  4987.1  357.74
  4987.4  357.24  4991.3  357.24  4991.6  357.74  4996.9  358.39  5002.9  358.39
  5013.6  359.90  5041.8  365.01  5056.0  368.35  5070.1  371.08  5073.3  370.46
  5084.3  368.31  5112.5  370.23  5126.7  370.95  5137.3  372.09  5140.8  372.09
#Mann=6,-1,0
  4397.3    0.07       0  4577.0   0.035       0  4628.5    0.07       0
  4987.1    0.05       0  4991.6    0.07       0  5073.3    0.05       0
Bank Sta=4987.1,4991.6
Exp/Cntr=0.3,0.1

Type RM Length L Ch R = 1,5541,446,446,446
BEGIN DESCRIPTION:
Stream0781 11.0
END DESCRIPTION:
XS GIS Cut Line= 3
      2415325.05     13600925.00      2415675.00     13600925.00
      2416075.04     13600624.97
#Sta/Elev= 30
  4650.5  368.20  4760.5  365.58  4900.5  360.13  4940.5  355.82  4950.5  353.94
  4960.5  352.75  4988.1  352.36  4988.5  351.86  4992.5  351.86  4992.8  352.36
  5143.2  354.82  5157.7  355.49  5193.2  356.30  5207.7  357.27  5228.6  357.68
  5236.9  358.33  5243.2  358.32  5278.6  360.10  5293.2  360.91  5322.3  363.24
  5343.2  364.35  5357.7  365.94  5378.6  367.40  5386.9  368.37  5414.0  370.60
  5443.2  373.70  5478.6  376.29  5493.2  377.59  5497.3  378.31  5500.5  378.31
#Mann=3,-1,0
  4650.5    0.07       0  4988.1    0.05       0  4992.8    0.07       0
Bank Sta=4988.1,4992.8
Exp/Cntr=0.3,0.1

Type RM Length L Ch R = 1,5095,457,457,457
BEGIN DESCRIPTION:
Stream0781 10.0
END DESCRIPTION:
XS GIS Cut Line= 3
      2415524.97     13601425.01      2415875.00     13601275.00
      2416275.00     13600875.00
#Sta/Elev= 30
  4614.8  365.42  4713.9  363.80  4897.7  360.79  4919.5  360.09  4928.2  359.23
  4934.0  359.14  4940.4  358.27  4973.9  352.87  4981.1  350.73  4986.6  350.35
  4992.9  351.36  4999.2  351.36  5023.9  351.24  5078.1  350.10  5078.4  349.60
  5082.5  349.60  5082.8  350.10  5108.8  352.40  5122.9  353.22  5151.2  353.36
  5207.8  354.98  5236.0  356.51  5306.7  359.08  5320.9  359.96  5405.7  363.36
  5434.0  364.70  5462.3  366.98  5518.9  369.51  5547.2  371.17  5561.3  371.36
#Mann=6,-1,0
  4614.8    0.12       0  4713.9    0.07       0  4928.2    0.12       0
  4940.4    0.07       0  5078.1    0.05       0  5082.8    0.07       0
Bank Sta=5078.1,5082.8
Exp/Cntr=0.3,0.1

Type RM Length L Ch R = 1,4638,438,438,438
BEGIN DESCRIPTION:
Stream0781 9.0
END DESCRIPTION:
XS GIS Cut Line= 3
      2415624.95     13601575.00      2416175.00     13601525.00
      2416575.00     13601125.00
#Sta/Elev= 30
  4447.1  364.34  4470.6  363.96  4678.1  360.24  4688.1  359.85  4698.2  356.37
  4789.4  353.42  4808.6  352.91  4824.8  351.39  4828.7  351.10  4838.8  346.97
  4866.4  345.00  4866.8  344.50  4871.0  344.50  4871.3  345.00  4909.0  346.51
  4939.2  346.78  4949.2  349.68  4969.3  349.13  5027.7  349.94  5070.1  348.75
  5183.3  349.11  5239.8  347.87  5268.1  349.11  5281.4  350.97  5324.7  357.76
  5393.7  360.98  5423.7  362.67  5437.8  362.78  5452.0  364.16  5565.1  370.27
#Mann=8,-1,0
  4447.1    0.07       0  4470.6    0.12       0  4789.4    0.07       0
  4824.8     0.1       0  4866.4    0.05       0  4871.3     0.1       0
  5281.4    0.05       0  5393.7    0.07       0
Bank Sta=4866.4,4871.3
Exp/Cntr=0.3,0.1

Type RM Length L Ch R = 1,4200,465,465,465
BEGIN DESCRIPTION:
Stream0781 8.0
END DESCRIPTION:
XS GIS Cut Line= 3
      2416075.02     13602224.98      2416375.00     13601825.00
      2416775.00     13601025.00
#Sta/Elev= 30
  4496.1  361.71  4632.5  357.28  4738.8  353.05  4782.5  352.22  4788.8  351.59
  4864.7  350.61  4896.1  349.86  4909.6  348.23  4924.2  342.60  4930.0  341.84
  4930.4  341.34  4934.6  341.34  4935.0  341.84  4938.8  345.07  4946.1  346.35
  4953.4  346.53  4974.2  344.59  4992.9  346.15  5121.8  346.89  5166.6  349.00
  5256.0  348.94  5295.1  350.38  5435.5  357.91  5488.0  360.76  5652.9  367.97
  5658.5  368.83  5793.2  375.73  5816.8  377.30  5845.8  379.51  5890.5  381.34
#Mann=7,-1,0
  4496.1    0.07       0  4864.7     0.1       0  4930.0    0.05       0
  4935.0     0.1       0  5435.5    0.07       0  5793.2    0.05       0
  5816.8    0.07       0
Bank Sta=4930,4935
Exp/Cntr=0.3,0.1

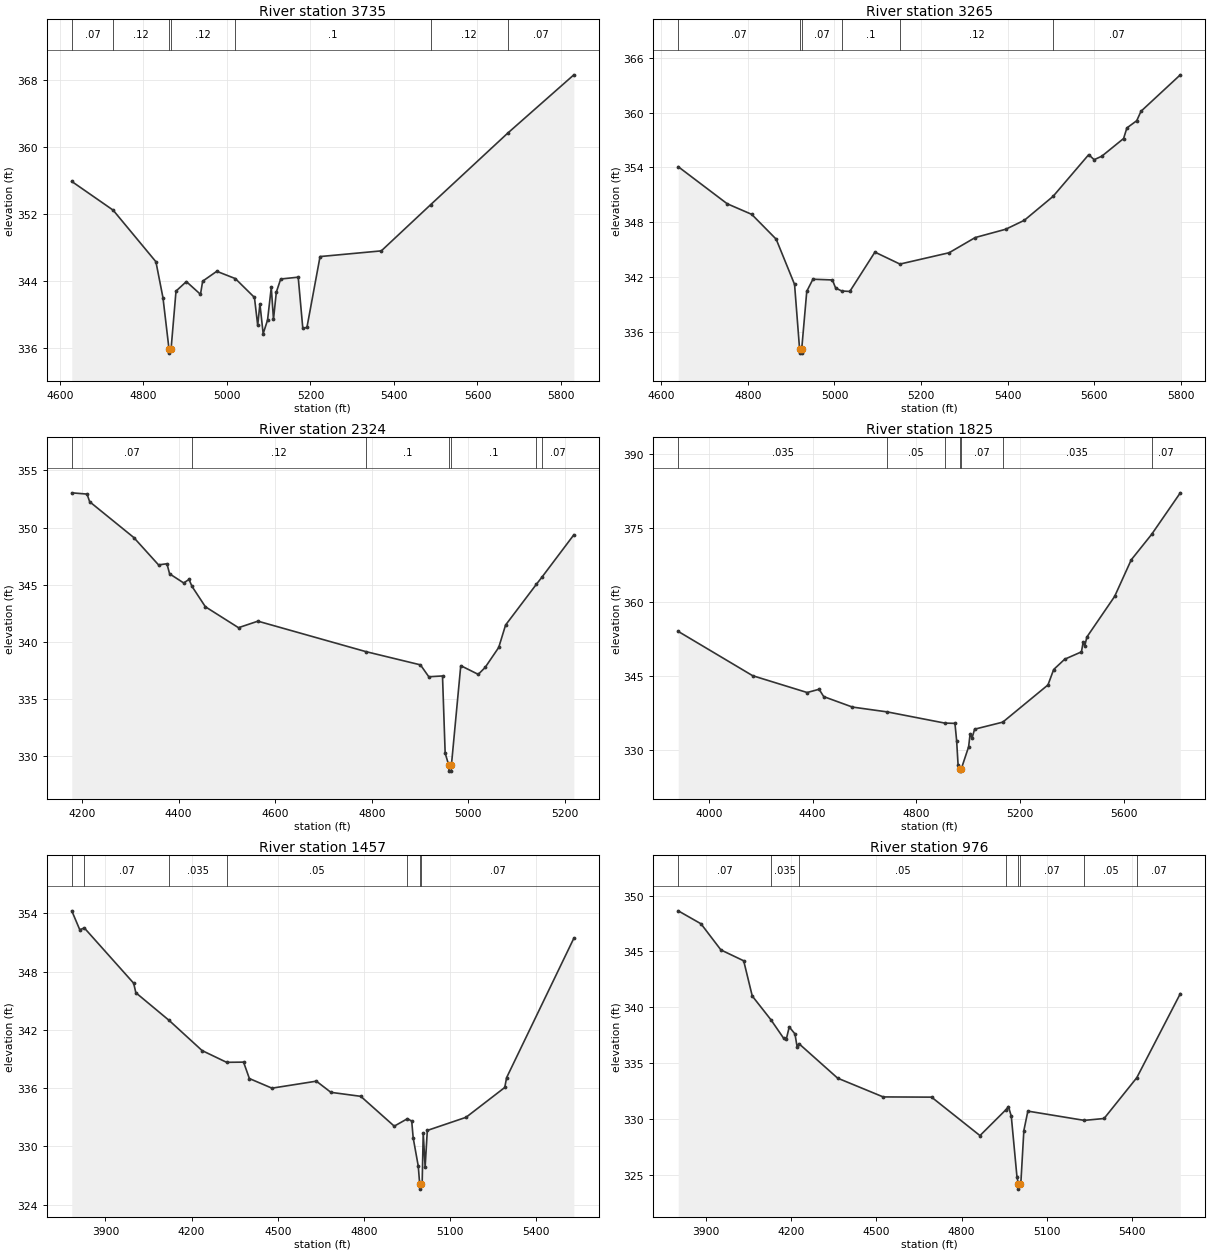
Type RM Length L Ch R = 1,3735,470,470,470
BEGIN DESCRIPTION:
Stream0781 7.0
END DESCRIPTION:
XS GIS Cut Line= 3
      2416624.99     13602425.04      2416725.00     13602075.00
      2416975.00     13601275.00
#Sta/Elev= 30
  4628.5  355.90  4727.6  352.47  4830.0  346.31  4846.9  342.01  4861.3  335.90
  4861.7  335.40  4866.3  335.90  4878.1  342.81  4902.9  343.94  4936.7  342.42
  4941.9  343.99  4975.7  345.17  5020.1  344.30  5065.9  342.05  5073.7  338.72
  5079.0  341.28  5086.8  337.72  5097.3  339.35  5106.2  343.25  5111.5  339.44
  5118.3  342.68  5128.8  344.25  5170.7  344.47  5181.7  338.36  5191.6  338.47
  5223.0  346.93  5369.7  347.61  5487.7  353.12  5672.2  361.66  5830.7  368.63
#Mann=7,-1,0
  4628.5    0.07       0  4727.6    0.12       0  4861.3    0.05       0
  4866.3    0.12       0  5020.1     0.1       0  5487.7    0.12       0
  5672.2    0.07       0
Bank Sta=4861.3,4866.3
Exp/Cntr=0.3,0.1

Type RM Length L Ch R = 1,3265,941,941,941
BEGIN DESCRIPTION:
Stream0781 6.0
END DESCRIPTION:
XS GIS Cut Line= 3
      2416875.03     13602424.97      2417125.00     13602175.00
      2417025.00     13601375.03
#Sta/Elev= 30
  4639.2  354.07  4752.3  350.01  4808.9  348.85  4865.4  346.13  4907.9  341.17
  4919.4  334.14  4919.8  333.64  4924.1  333.64  4924.5  334.14  4936.1  340.42
  4950.3  341.74  4995.2  341.66  5002.8  340.77  5016.9  340.45  5035.5  340.40
  5093.5  344.71  5151.3  343.40  5264.8  344.64  5325.3  346.31  5395.8  347.22
  5438.7  348.20  5505.0  350.82  5587.3  355.39  5599.9  354.84  5617.5  355.22
  5667.9  357.16  5675.5  358.32  5698.2  359.11  5708.2  360.15  5798.9  364.14
#Mann=6,-1,0
  4639.2    0.07       0  4919.4    0.05       0  4924.5    0.07       0
  5016.9     0.1       0  5151.3    0.12       0  5505.0    0.07       0
Bank Sta=4919.4,4924.5
Exp/Cntr=0.3,0.1

Type RM Length L Ch R = 1,2324,499,499,499
BEGIN DESCRIPTION:
Stream0781 5.0
END DESCRIPTION:
XS GIS Cut Line= 3
      2417174.97     13602425.01      2417925.00     13602075.00
      2418075.00     13601925.00
#Sta/Elev= 30
  4178.6  353.04  4210.2  352.93  4215.7  352.26  4307.1  349.13  4358.3  346.74
  4375.7  346.84  4381.2  345.96  4410.4  345.16  4421.4  345.47  4427.6  344.86
  4455.3  343.08  4523.9  341.25  4564.1  341.82  4787.5  339.16  4900.7  338.00
  4918.0  336.96  4946.4  337.03  4951.9  330.28  4959.5  329.21  4959.9  328.71
  4964.3  328.71  4964.8  329.21  4984.2  337.93  5020.4  337.17  5034.6  337.77
  5062.8  339.52  5077.0  341.48  5140.9  345.05  5152.2  345.66  5218.4  349.37
#Mann=7,-1,0
  4178.6    0.07       0  4427.6    0.12       0  4787.5     0.1       0
  4959.5    0.05       0  4964.8     0.1       0  5140.9    0.12       0
  5152.2    0.07       0
Bank Sta=4959.5,4964.8
Exp/Cntr=0.3,0.1

Type RM Length L Ch R = 1,1825,368,368,368
BEGIN DESCRIPTION:
Stream0781 4.0
END DESCRIPTION:
XS GIS Cut Line= 3
      2417193.67     13602923.32      2418239.98     13602449.09
      2418736.56     13601839.65
#Sta/Elev= 30
  3882.5  354.08  4169.4  345.09  4379.3  341.68  4425.4  342.34  4443.1  340.85
  4553.7  338.73  4688.7  337.74  4909.5  335.48  4948.9  335.42  4955.4  331.91
  4960.9  327.05  4968.3  326.23  4968.7  325.73  4973.6  326.23  5001.6  330.67
  5007.1  333.18  5014.8  332.45  5024.7  334.24  5133.2  335.67  5307.4  343.22
  5329.4  346.35  5371.9  348.44  5436.4  349.93  5442.9  351.88  5449.3  351.14
  5457.3  352.94  5564.3  361.18  5628.2  368.60  5706.7  373.76  5817.4  382.20
#Mann=7,-1,0
  3882.5   0.035       0  4688.7    0.05       0  4909.5    0.07       0
  4968.3    0.05       0  4973.6    0.07       0  5133.2   0.035       0
  5706.7    0.07       0
Bank Sta=4968.3,4973.6
Exp/Cntr=0.3,0.1

Type RM Length L Ch R = 1,1457,481,481,481
BEGIN DESCRIPTION:
Stream0781 3.0
END DESCRIPTION:
XS GIS Cut Line= 3
      2417174.98     13602975.00      2418375.00     13602775.00
      2418775.01     13602424.99
#Sta/Elev= 30
  3783.0  354.25  3810.9  352.30  3826.7  352.49  3998.5  346.80  4006.1  345.82
  4121.7  342.98  4236.7  339.87  4322.1  338.66  4381.2  338.68  4401.4  336.99
  4480.0  336.00  4634.6  336.72  4685.3  335.57  4789.2  335.16  4905.8  332.09
  4951.9  332.86  4966.6  332.61  4971.7  330.89  4989.4  327.98  4994.4  326.11
  4994.8  325.61  4999.7  326.11  5002.9  326.11  5006.7  331.41  5013.3  327.88
  5020.9  331.65  5155.7  333.00  5290.5  336.07  5297.1  337.09  5531.1  351.43
#Mann=7,-1,0
  3783.0   0.035       0  3826.7    0.07       0  4121.7   0.035       0
  4322.1    0.05       0  4951.9    0.07       0  4994.4    0.05       0
  4999.7    0.07       0
Bank Sta=4994.4,4999.7
Exp/Cntr=0.3,0.1

Type RM Length L Ch R = 1,976,447,447,447
BEGIN DESCRIPTION:
Stream0781 2.0
END DESCRIPTION:
XS GIS Cut Line= 3
      2417275.05     13603125.00      2418475.00     13603225.00
      2418875.00     13602825.00
#Sta/Elev= 30
  3801.2  348.63  3881.4  347.47  3951.7  345.13  4031.9  344.16  4062.1  341.01
  4128.0  338.88  4172.4  337.24  4182.5  337.19  4192.5  338.24  4212.6  337.62
  4220.1  336.49  4226.5  336.75  4363.1  333.66  4523.6  331.98  4694.2  331.96
  4864.8  328.52  4956.9  330.85  4965.2  331.12  4975.2  330.25  4995.3  324.80
  5000.1  324.23  5000.6  323.73  5005.5  324.23  5008.8  324.23  5019.5  328.97
  5033.6  330.71  5232.7  329.88  5302.3  330.05  5417.6  333.70  5571.0  341.22
#Mann=8,-1,0
  3801.2    0.07       0  4128.0   0.035       0  4226.5    0.05       0
  4956.9    0.07       0  5000.1    0.05       0  5005.5    0.07       0
  5232.7    0.05       0  5417.6    0.07       0
Bank Sta=5000.1,5005.5
Exp/Cntr=0.3,0.1

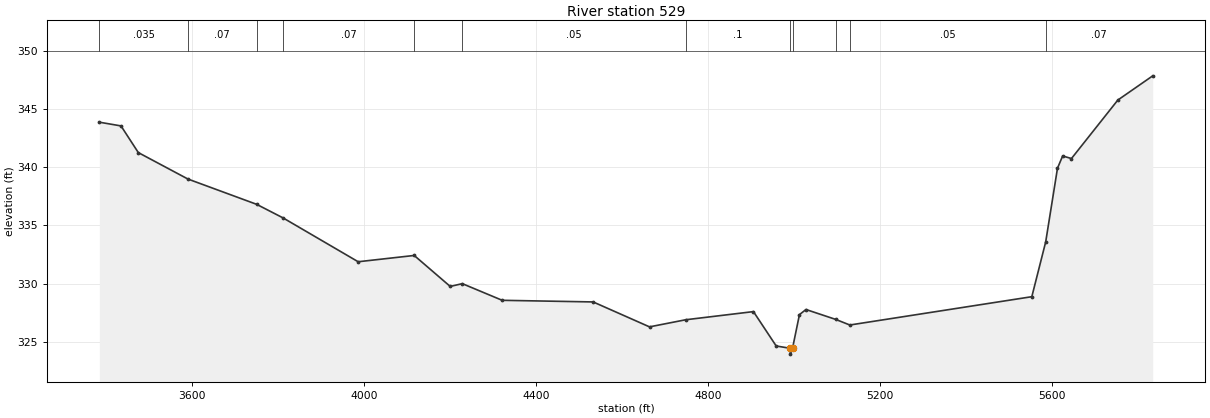
Type RM Length L Ch R = 1,529,0,0,0
BEGIN DESCRIPTION:
Stream0781 1.0
END DESCRIPTION:
XS GIS Cut Line= 3
      2417125.02     13603775.00      2418725.00     13603575.00
      2418975.01     13602774.98
#Sta/Elev= 30
  3383.7  343.85  3434.1  343.53  3474.4  341.24  3589.8  338.97  3749.6  336.80
  3811.3  335.63  3985.8  331.87  4116.2  332.41  4200.0  329.75  4228.1  329.99
  4320.9  328.56  4532.5  328.42  4663.6  326.28  4747.7  326.89  4905.4  327.59
  4958.3  324.64  4990.9  324.44  4991.3  323.94  4996.3  324.44  5012.4  327.33
  5027.6  327.77  5096.8  326.92  5129.6  326.44  5553.0  328.87  5585.3  333.58
  5612.7  339.90  5624.7  340.95  5645.2  340.73  5753.1  345.75  5834.3  347.83
#Mann=12,-1,0
  3383.7   0.035       0  3589.8    0.07       0  3749.6   0.035       0
  3811.3    0.07       0  4116.2   0.035       0  4228.1    0.05       0
  4747.7     0.1       0  4990.9    0.05       0  4996.3     0.1       0
  5096.8    0.07       0  5129.6    0.05       0  5585.3    0.07       0
Bank Sta=4990.9,4996.3
Exp/Cntr=0.3,0.1

Chan Stop Cuts=-1