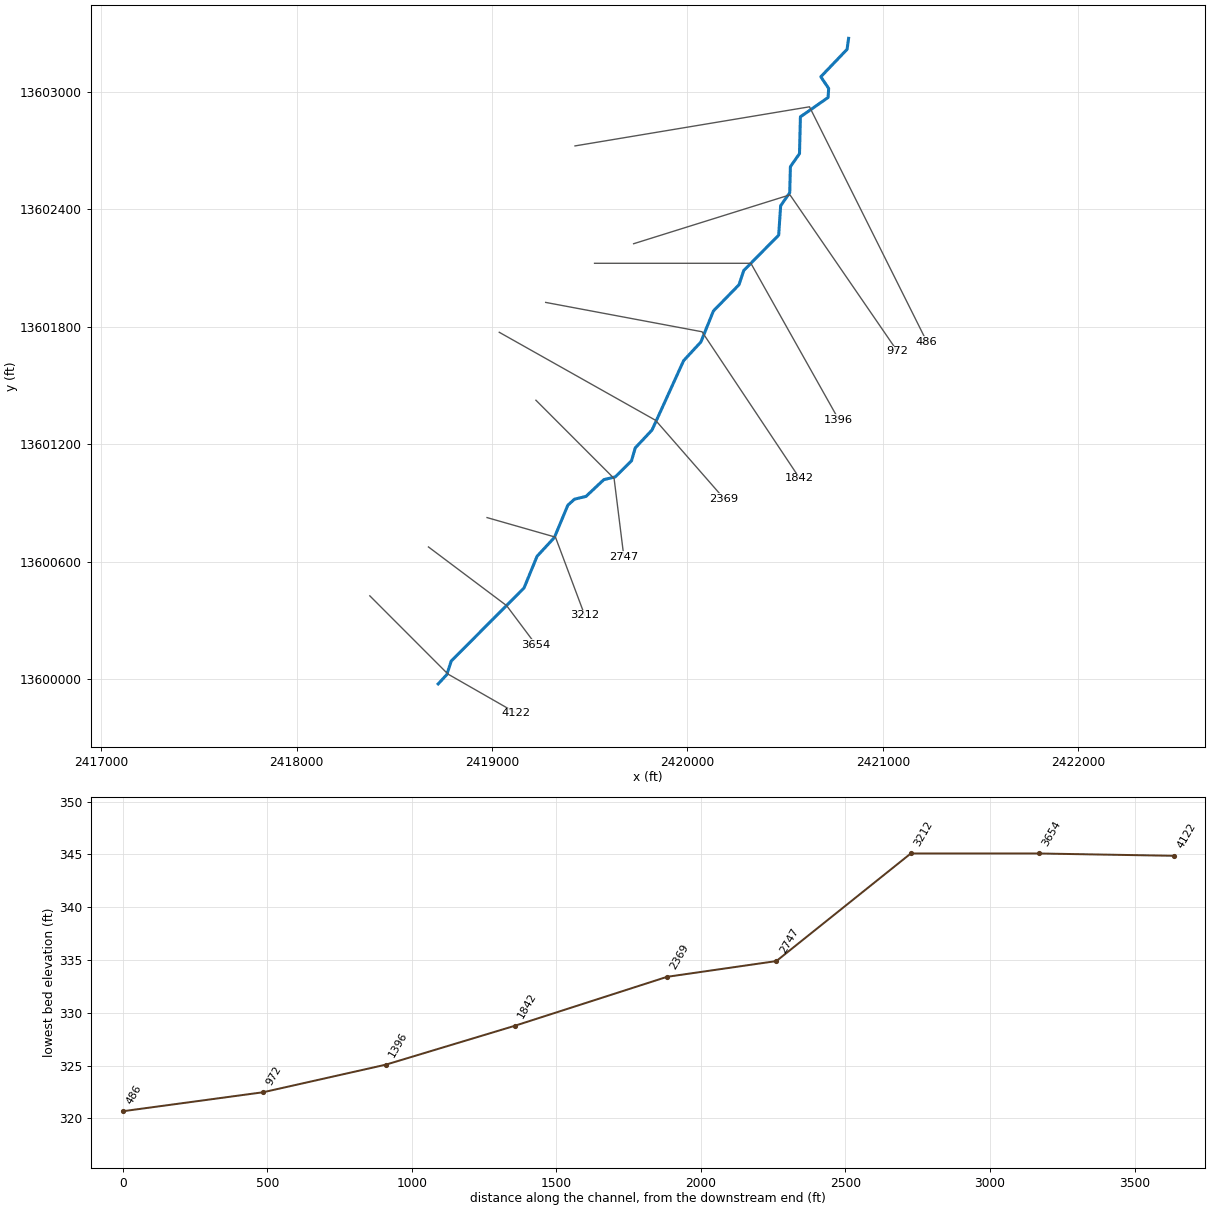
--- Stream0782.prj (project) ---

Proj Title=Stream0782 Base Level Engineering
Current Plan=p01
Default Exp/Contr=0.3,0.1
English Units
Geom File=g01
Flow File=f01
Plan File=p01
BEGIN DESCRIPTION:
Stream0782
END DESCRIPTION:

--- Stream0782.p01 (plan) ---

Plan Title=Multiple Run
Short Identifier=Multiple
Geom File=g01
Flow File=f01
Subcritical Flow
K Sum by GR= 0
Std Step Tol= 0.01
Critical Tol= 0.01
Num of Std Step Trials= 20
Max Error Tol= 0.3
Flow Tol Ratio= 0.001
Split Flow NTrial= 30
Split Flow Tol= 0.02
Split Flow Ratio= 0.02
Log Output Level= 0
Friction Slope Method= 1
Unsteady Friction Slope Method= 2
Unsteady Bridges Friction Slope Method= 1
Parabolic Critical Depth
Global Vel Dist=  1 , 1 , 1
Global Log Level= 0
CheckData=True
Encroach Param= -1, 0, 0, 0
BEGIN DESCRIPTION:
Multiple Run
END DESCRIPTION:

--- Stream0782.f01 (steady flow) ---

Flow Title=Multiple
Number of Profiles=7
Profile Names=10-year,25-year,50-year,1pct_min,100-year,1pct_plu,500-year
River Rch & RM= Stream0782,Reach-1,4122
     859    1423    1946    1289    2571    5130    4448
Boundary for River Rch & Prof#=Stream0782,Reach-1,1
Up Type=0
Dn Type=3
Dn Slope=0.005
Boundary for River Rch & Prof#=Stream0782,Reach-1,2
Up Type=0
Dn Type=3
Dn Slope=0.005
Boundary for River Rch & Prof#=Stream0782,Reach-1,3
Up Type=0
Dn Type=3
Dn Slope=0.005
Boundary for River Rch & Prof#=Stream0782,Reach-1,4
Up Type=0
Dn Type=3
Dn Slope=0.005
Boundary for River Rch & Prof#=Stream0782,Reach-1,5
Up Type=0
Dn Type=3
Dn Slope=0.005
Boundary for River Rch & Prof#=Stream0782,Reach-1,6
Up Type=0
Dn Type=3
Dn Slope=0.005
Boundary for River Rch & Prof#=Stream0782,Reach-1,7
Up Type=0
Dn Type=3
Dn Slope=0.005

--- Stream0782.g01 (geometry) ---

Geom Title=Existing Conditions

River Reach=Stream0782,Reach-1
Reach XY= 30
      2418725.00     13599975.00      2418769.29     13600022.65
      2418791.61     13600091.69      2419164.24     13600465.32
      2419230.85     13600627.29      2419319.15     13600722.71
      2419388.47     13600888.57      2419422.46     13600919.25
      2419481.02     13600933.18      2419572.72     13601019.13
      2419631.07     13601033.15      2419714.23     13601115.30
      2419733.18     13601181.04      2419819.15     13601272.71
      2419980.85     13601627.29      2420069.15     13601722.71
      2420133.14     13601881.06      2420264.22     13602015.32
      2420288.63     13602088.21      2420467.18     13602268.81
      2420477.27     13602419.06      2420523.77     13602485.51
      2420527.27     13602619.06      2420573.78     13602685.51
      2420578.45     13602873.75      2420719.99     13602972.46
      2420723.03     13603018.91      2420682.82     13603078.41
      2420817.24     13603218.79      2420825.00     13603275.00

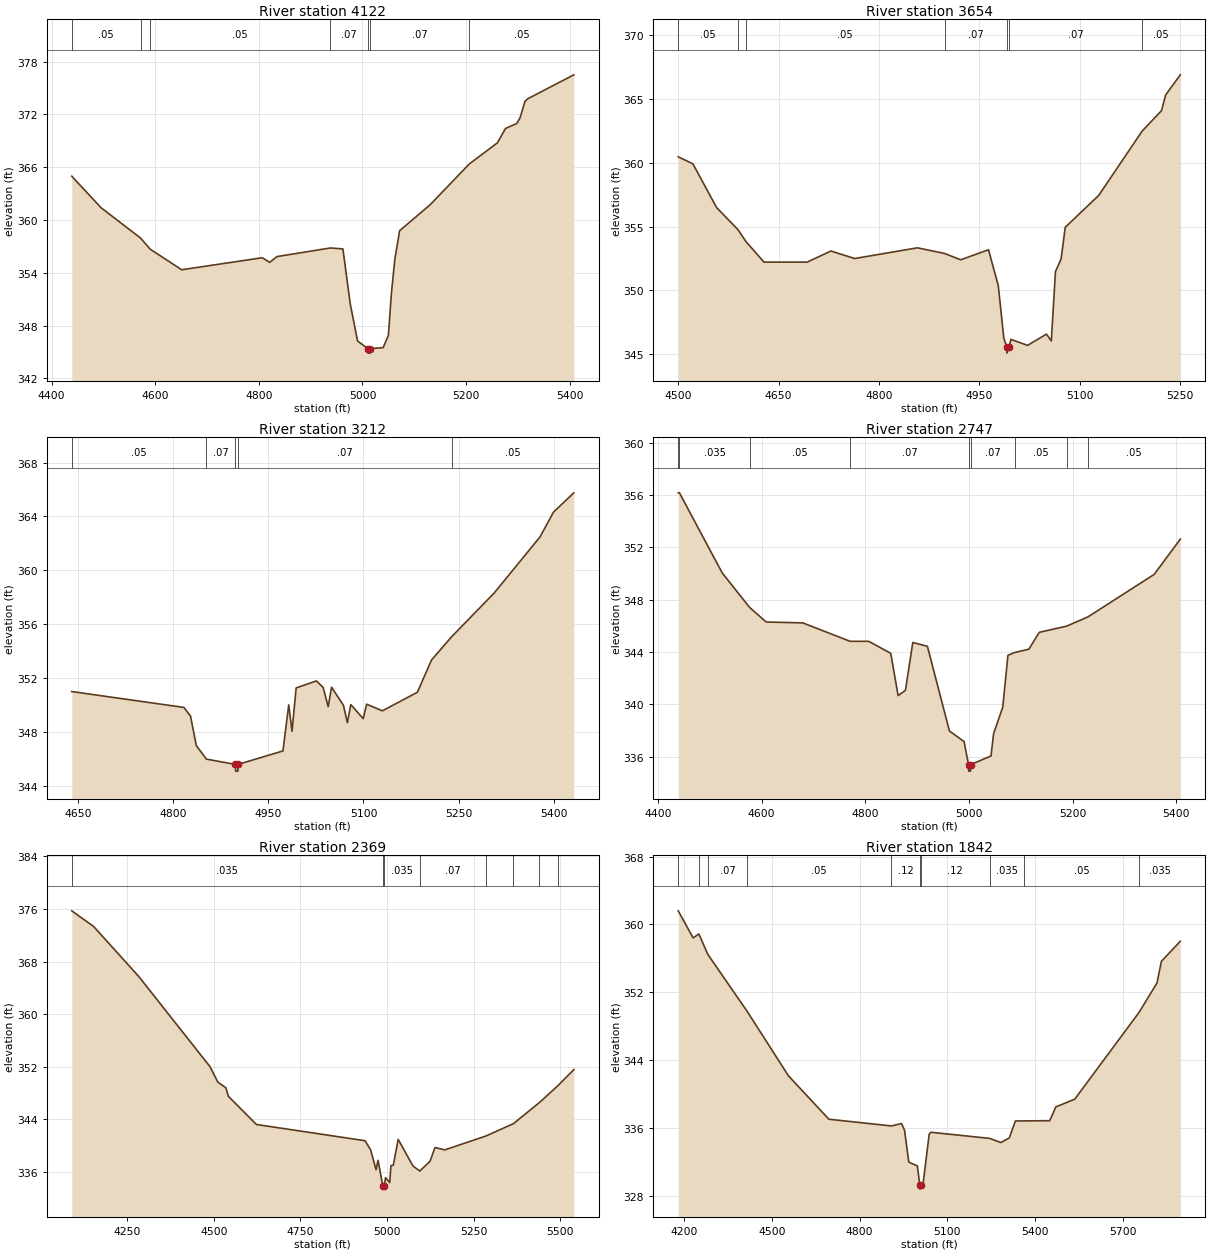
Type RM Length L Ch R = 1,4122,468,468,468
BEGIN DESCRIPTION:
Stream0782 9.0
END DESCRIPTION:
XS GIS Cut Line= 3
      2418375.01     13600424.99      2418775.00     13600025.00
      2419125.01     13599824.99
#Sta/Elev= 30
  4439.1  364.98  4495.7  361.39  4571.8  357.95  4590.3  356.69  4651.2  354.34
  4806.8  355.71  4820.9  355.18  4835.1  355.84  4938.3  356.82  4962.3  356.71
  4976.5  350.44  4990.6  346.24  5010.7  345.36  5010.9  344.86  5014.4  344.86
  5014.7  345.36  5040.0  345.49  5050.1  346.90  5055.9  351.69  5062.4  355.49
  5071.7  358.78  5130.7  361.74  5206.3  366.38  5260.3  368.77  5276.2  370.42
  5297.7  370.97  5304.2  371.63  5313.6  373.50  5319.3  373.80  5407.9  376.51
#Mann=7,-1,0
  4439.1    0.05       0  4571.8   0.035       0  4590.3    0.05       0
  4938.3    0.07       0  5010.7    0.05       0  5014.7    0.07       0
  5206.3    0.05       0
Bank Sta=5010.7,5014.7
Exp/Cntr=0.3,0.1

Type RM Length L Ch R = 1,3654,442,442,442
BEGIN DESCRIPTION:
Stream0782 8.0
END DESCRIPTION:
XS GIS Cut Line= 3
      2418675.02     13600674.99      2419075.00     13600375.00
      2419225.01     13600174.98
#Sta/Elev= 30
  4500.0  360.48  4521.9  359.93  4557.3  356.50  4589.5  354.75  4601.0  353.84
  4628.1  352.22  4692.7  352.22  4728.1  353.09  4763.5  352.50  4857.3  353.34
  4897.8  352.90  4921.9  352.40  4963.5  353.19  4978.1  350.37  4986.4  346.24
  4990.7  345.58  4990.9  345.08  4994.7  345.58  4996.9  346.16  5021.9  345.69
  5050.0  346.57  5057.3  346.04  5063.5  351.47  5071.9  352.46  5078.1  354.95
  5128.1  357.45  5192.9  362.49  5221.9  364.10  5228.1  365.33  5250.0  366.91
#Mann=7,-1,0
  4500.0    0.05       0  4589.5   0.035       0  4601.0    0.05       0
  4897.8    0.07       0  4990.7    0.05       0  4994.7    0.07       0
  5192.9    0.05       0
Bank Sta=4990.7,4994.7
Exp/Cntr=0.3,0.1

Type RM Length L Ch R = 1,3212,465,465,465
BEGIN DESCRIPTION:
Stream0782 7.0
END DESCRIPTION:
XS GIS Cut Line= 3
      2418974.97     13600825.01      2419325.00     13600725.00
      2419474.99     13600325.04
#Sta/Elev= 30
  4640.3  350.99  4817.1  349.81  4827.5  349.16  4836.6  346.97  4852.6  345.97
  4898.3  345.58  4898.6  345.08  4902.1  345.08  4902.4  345.58  4973.1  346.58
  4982.2  350.00  4987.4  348.04  4993.9  351.26  5025.7  351.78  5036.4  351.30
  5044.4  349.87  5049.7  351.31  5068.4  349.97  5074.6  348.68  5080.0  350.02
  5099.6  348.98  5104.9  350.05  5129.8  349.56  5185.0  350.94  5207.3  353.34
  5239.3  355.08  5306.0  358.31  5378.1  362.47  5399.5  364.32  5431.5  365.75
#Mann=5,-1,0
  4640.3    0.05       0  4852.6    0.07       0  4898.3    0.05       0
  4902.4    0.07       0  5239.3    0.05       0
Bank Sta=4898.3,4902.4
Exp/Cntr=0.3,0.1

Type RM Length L Ch R = 1,2747,378,378,378
BEGIN DESCRIPTION:
Stream0782 6.0
END DESCRIPTION:
XS GIS Cut Line= 3
      2419224.99     13601425.01      2419625.00     13601025.00
      2419675.00     13600625.01
#Sta/Elev= 30
  4439.1  356.18  4441.4  356.18  4524.0  350.05  4576.9  347.41  4608.8  346.30
  4679.5  346.23  4770.9  344.82  4806.8  344.82  4849.2  343.90  4863.4  340.67
  4877.5  341.07  4891.7  344.73  4919.9  344.44  4962.4  337.96  4990.7  337.15
  4999.2  335.39  4999.5  334.89  5003.1  334.89  5003.4  335.39  5042.6  336.05
  5047.6  337.75  5065.3  339.79  5075.3  343.75  5088.0  343.96  5115.7  344.22
  5135.8  345.51  5188.6  345.98  5229.7  346.69  5357.5  349.94  5407.9  352.64
#Mann=9,-1,0
  4439.1    0.05       0  4441.4   0.035       0  4576.9    0.05       0
  4770.9    0.07       0  4999.2    0.05       0  5003.4    0.07       0
  5088.0    0.05       0  5188.6    0.07       0  5229.7    0.05       0
Bank Sta=4999.2,5003.4
Exp/Cntr=0.3,0.1

Type RM Length L Ch R = 1,2369,527,527,527
BEGIN DESCRIPTION:
Stream0782 5.0
END DESCRIPTION:
XS GIS Cut Line= 3
      2419037.36     13601772.31      2419837.36     13601322.31
      2420187.37     13600922.29
#Sta/Elev= 30
  4089.9  375.71  4153.0  373.33  4283.1  365.74  4488.8  352.03  4511.7  349.66
  4534.7  348.82  4541.9  347.52  4622.8  343.23  4936.4  340.76  4952.4  339.41
  4968.3  336.36  4974.0  337.78  4987.8  333.90  4988.1  333.40  4992.1  333.90
  4995.7  335.14  5007.8  334.40  5011.3  336.98  5018.0  337.02  5032.2  340.96
  5074.9  336.92  5094.7  336.15  5124.3  337.65  5138.5  339.72  5167.0  339.37
  5285.7  341.48  5364.8  343.35  5440.1  346.57  5492.5  349.09  5539.3  351.57
#Mann=8,-1,0
  4089.9   0.035       0  4987.8   0.035       0  4992.1   0.035       0
  5094.7    0.07       0  5285.7    0.05       0  5364.8    0.07       0
  5440.1    0.05       0  5492.5    0.07       0
Bank Sta=4987.8,4992.1
Exp/Cntr=0.3,0.1

Type RM Length L Ch R = 1,1842,446,446,446
BEGIN DESCRIPTION:
Stream0782 4.0
END DESCRIPTION:
XS GIS Cut Line= 3
      2419274.96     13601925.01      2420075.00     13601775.00
      2420575.02     13601024.97
#Sta/Elev= 30
  4180.3  361.61  4231.2  358.41  4250.8  358.88  4281.4  356.47  4415.7  349.75
  4556.8  342.14  4695.0  337.01  4908.8  336.22  4943.4  336.50  4953.6  335.70
  4968.0  331.95  4997.3  331.50  5005.7  329.26  5005.9  328.76  5010.0  329.26
  5016.8  329.39  5037.8  335.26  5043.9  335.47  5244.1  334.75  5282.7  334.26
  5311.3  334.80  5332.3  336.81  5361.0  336.81  5449.5  336.84  5470.5  338.47
  5535.1  339.38  5754.7  349.62  5816.0  353.09  5831.1  355.65  5895.7  358.02
#Mann=10,-1,0
  4180.3    0.07       0  4250.8    0.05       0  4281.4    0.07       0
  4415.7    0.05       0  4908.8    0.12       0  5005.7    0.05       0
  5010.0    0.12       0  5244.1   0.035       0  5361.0    0.05       0
  5754.7   0.035       0
Bank Sta=5005.7,5010
Exp/Cntr=0.3,0.1

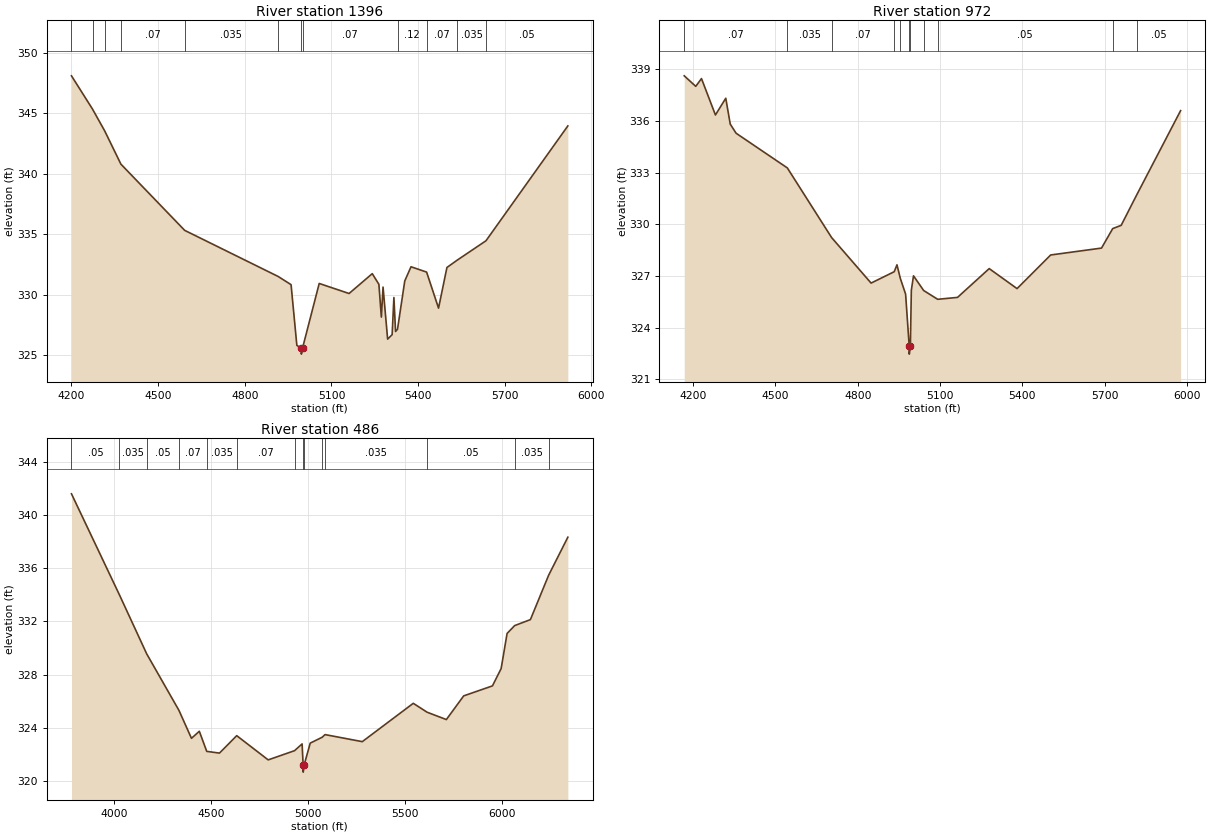
Type RM Length L Ch R = 1,1396,424,424,424
BEGIN DESCRIPTION:
Stream0782 3.0
END DESCRIPTION:
XS GIS Cut Line= 3
      2419524.98     13602125.00      2420325.00     13602125.00
      2420775.00     13601325.00
#Sta/Elev= 30
  4200.3  348.08  4273.1  345.33  4315.2  343.53  4371.4  340.78  4592.0  335.31
  4915.4  331.50  4960.3  330.82  4980.3  325.80  4995.6  325.58  4995.9  325.08
  5000.0  325.58  5057.7  330.92  5161.0  330.09  5241.3  331.73  5264.2  330.85
  5272.8  328.14  5278.6  330.62  5294.5  326.32  5310.1  326.69  5316.2  329.76
  5321.9  326.95  5328.7  327.14  5353.8  331.13  5375.4  332.30  5429.4  331.86
  5470.7  328.88  5499.7  332.24  5534.3  332.83  5634.9  334.45  5918.2  343.94
#Mann=12,-1,0
  4200.3   0.035       0  4273.1    0.07       0  4315.2    0.05       0
  4371.4    0.07       0  4592.0   0.035       0  4915.4    0.07       0
  4995.6    0.05       0  5000.0    0.07       0  5328.7    0.12       0
  5429.4    0.07       0  5534.3   0.035       0  5634.9    0.05       0
Bank Sta=4995.6,5000
Exp/Cntr=0.3,0.1

Type RM Length L Ch R = 1,972,486,486,486
BEGIN DESCRIPTION:
Stream0782 2.0
END DESCRIPTION:
XS GIS Cut Line= 3
      2419724.96     13602224.99      2420525.00     13602475.00
      2421074.99     13601675.01
#Sta/Elev= 30
  4167.5  338.61  4209.4  338.00  4230.4  338.45  4281.2  336.34  4318.9  337.31
  4335.2  335.81  4356.6  335.28  4543.2  333.27  4704.6  329.23  4848.5  326.59
  4932.9  327.25  4942.8  327.65  4955.1  326.86  4974.3  325.95  4987.3  322.97
  4987.6  322.47  4991.7  322.97  4995.2  326.18  5003.1  327.01  5040.1  326.16
  5091.2  325.65  5163.5  325.76  5279.0  327.43  5380.5  326.27  5503.0  328.22
  5688.3  328.62  5729.1  329.75  5760.0  329.94  5816.1  331.69  5976.5  336.59
#Mann=11,-1,0
  4167.5    0.07       0  4543.2   0.035       0  4704.6    0.07       0
  4932.9   0.035       0  4955.1    0.07       0  4987.3    0.05       0
  4991.7    0.07       0  5040.1   0.035       0  5091.2    0.05       0
  5729.1    0.07       0  5816.1    0.05       0
Bank Sta=4987.3,4991.7
Exp/Cntr=0.3,0.1

Type RM Length L Ch R = 1,486,0,0,0
BEGIN DESCRIPTION:
Stream0782 1.0
END DESCRIPTION:
XS GIS Cut Line= 3
      2419425.04     13602725.01      2420625.00     13602925.00
      2421225.02     13601724.96
#Sta/Elev= 30
  3779.3  341.58  4026.1  334.00  4167.2  329.55  4333.2  325.31  4397.7  323.21
  4438.2  323.74  4476.4  322.23  4542.1  322.10  4630.9  323.41  4793.1  321.59
  4928.7  322.28  4967.9  322.79  4973.3  321.17  4973.6  320.67  4977.7  321.17
  5009.8  322.85  5071.4  323.29  5086.1  323.49  5278.1  322.96  5540.9  325.84
  5612.3  325.17  5711.4  324.62  5800.8  326.40  5948.9  327.15  5993.7  328.45
  6024.4  331.09  6063.5  331.68  6144.6  332.13  6238.4  335.46  6337.5  338.32
#Mann=14,-1,0
  3779.3    0.05       0  4026.1   0.035       0  4167.2    0.05       0
  4333.2    0.07       0  4476.4   0.035       0  4630.9    0.07       0
  4928.7     0.1       0  4973.3    0.05       0  4977.7     0.1       0
  5071.4    0.12       0  5086.1   0.035       0  5612.3    0.05       0
  6063.5   0.035       0  6238.4    0.05       0
Bank Sta=4973.3,4977.7
Exp/Cntr=0.3,0.1

Chan Stop Cuts=-1