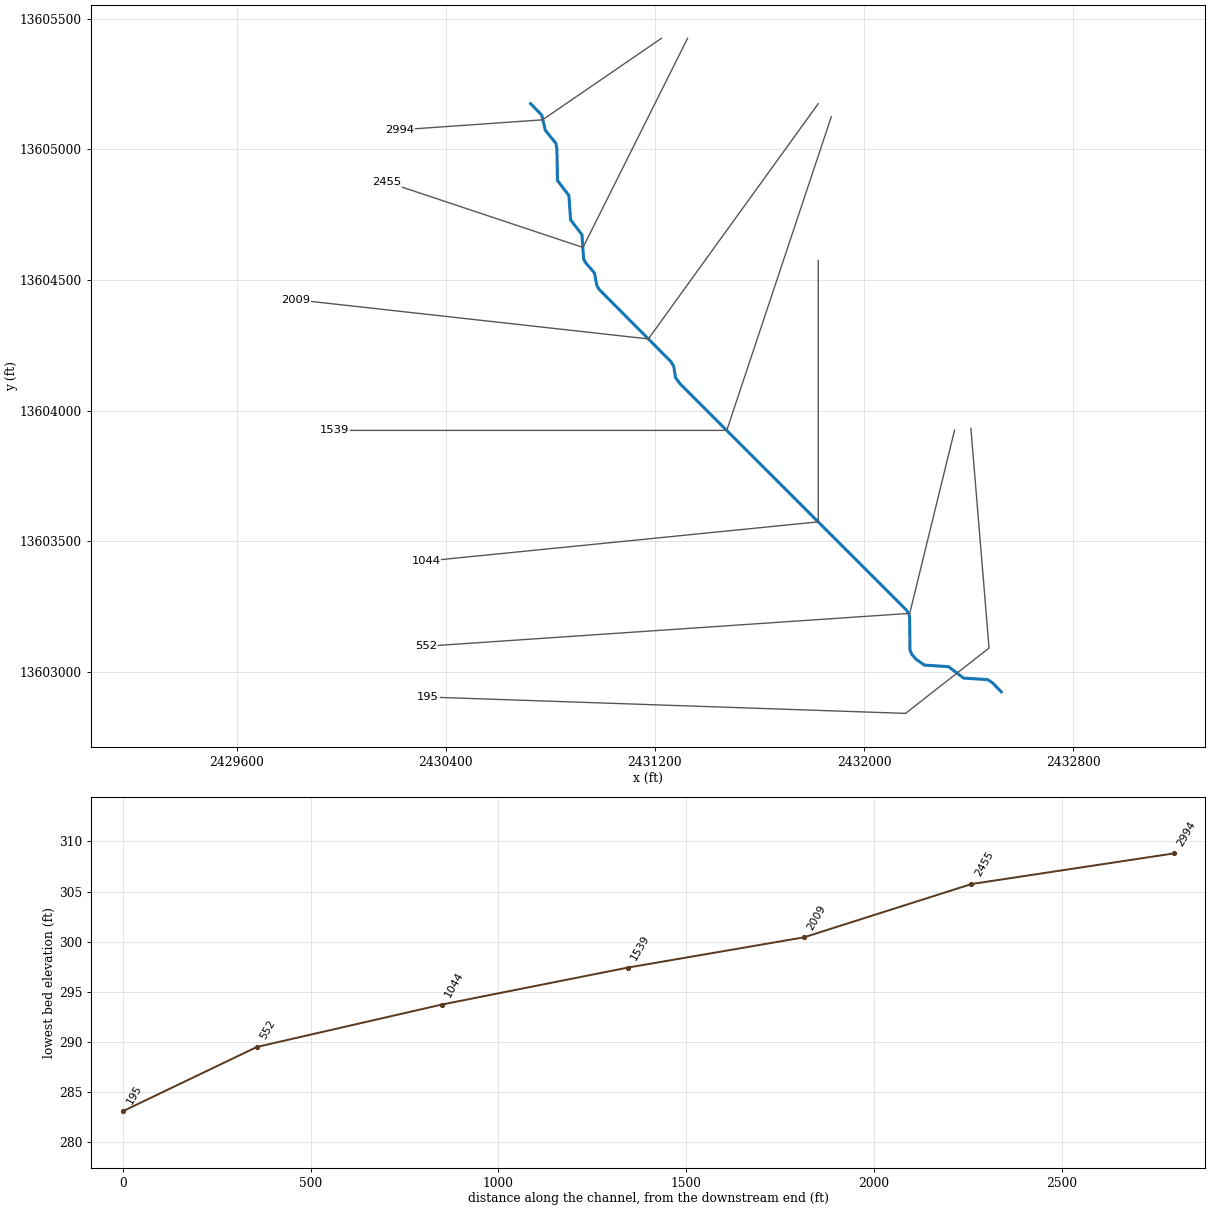
--- Stream0783.prj (project) ---

Proj Title=Stream0783 Base Level Engineering
Current Plan=p01
Default Exp/Contr=0.3,0.1
English Units
Geom File=g01
Flow File=f01
Plan File=p01
BEGIN DESCRIPTION:
Stream0783
END DESCRIPTION:

--- Stream0783.p01 (plan) ---

Plan Title=Multiple Run
Short Identifier=Multiple
Geom File=g01
Flow File=f01
Subcritical Flow
K Sum by GR= 0
Std Step Tol= 0.01
Critical Tol= 0.01
Num of Std Step Trials= 20
Max Error Tol= 0.3
Flow Tol Ratio= 0.001
Split Flow NTrial= 30
Split Flow Tol= 0.02
Split Flow Ratio= 0.02
Log Output Level= 0
Friction Slope Method= 1
Unsteady Friction Slope Method= 2
Unsteady Bridges Friction Slope Method= 1
Parabolic Critical Depth
Global Vel Dist=  1 , 1 , 1
Global Log Level= 0
CheckData=True
Encroach Param= -1, 0, 0, 0
BEGIN DESCRIPTION:
Multiple Run
END DESCRIPTION:

--- Stream0783.f01 (steady flow) ---

Flow Title=Multiple
Number of Profiles=7
Profile Names=10-year,25-year,50-year,1pct_min,100-year,1pct_plu,500-year
River Rch & RM= Stream0783,Reach-1,2994
     383     601     791     506    1009    2014    1625
Boundary for River Rch & Prof#=Stream0783,Reach-1,1
Up Type=0
Dn Type=3
Dn Slope=0.005
Boundary for River Rch & Prof#=Stream0783,Reach-1,2
Up Type=0
Dn Type=3
Dn Slope=0.005
Boundary for River Rch & Prof#=Stream0783,Reach-1,3
Up Type=0
Dn Type=3
Dn Slope=0.005
Boundary for River Rch & Prof#=Stream0783,Reach-1,4
Up Type=0
Dn Type=3
Dn Slope=0.005
Boundary for River Rch & Prof#=Stream0783,Reach-1,5
Up Type=0
Dn Type=3
Dn Slope=0.005
Boundary for River Rch & Prof#=Stream0783,Reach-1,6
Up Type=0
Dn Type=3
Dn Slope=0.005
Boundary for River Rch & Prof#=Stream0783,Reach-1,7
Up Type=0
Dn Type=3
Dn Slope=0.005

--- Stream0783.g01 (geometry) ---

Geom Title=Existing Conditions

River Reach=Stream0783,Reach-1
Reach XY= 30
      2430725.00     13605175.00      2430767.09     13605131.15
      2430781.03     13605072.78      2430821.25     13605023.45
      2430825.19     13605000.08      2430827.27     13604880.94
      2430871.14     13604823.40      2430877.35     13604730.97
      2430921.15     13604673.40      2430927.33     13604580.97
      2430935.84     13604565.35      2430968.86     13604527.17
      2430977.50     13604481.03      2430985.76     13604465.32
      2431261.37     13604188.21      2431272.47     13604168.95
      2431278.98     13604126.65      2431298.02     13604101.53
      2432161.63     13603238.32      2432171.46     13603223.53
      2432174.60     13603209.83      2432175.99     13603085.27
      2432182.68     13603068.48      2432197.66     13603050.98
      2432230.68     13603027.06      2432323.40     13603021.14
      2432380.96     13602977.32      2432473.60     13602971.61
      2432492.05     13602958.88      2432525.00     13602925.00

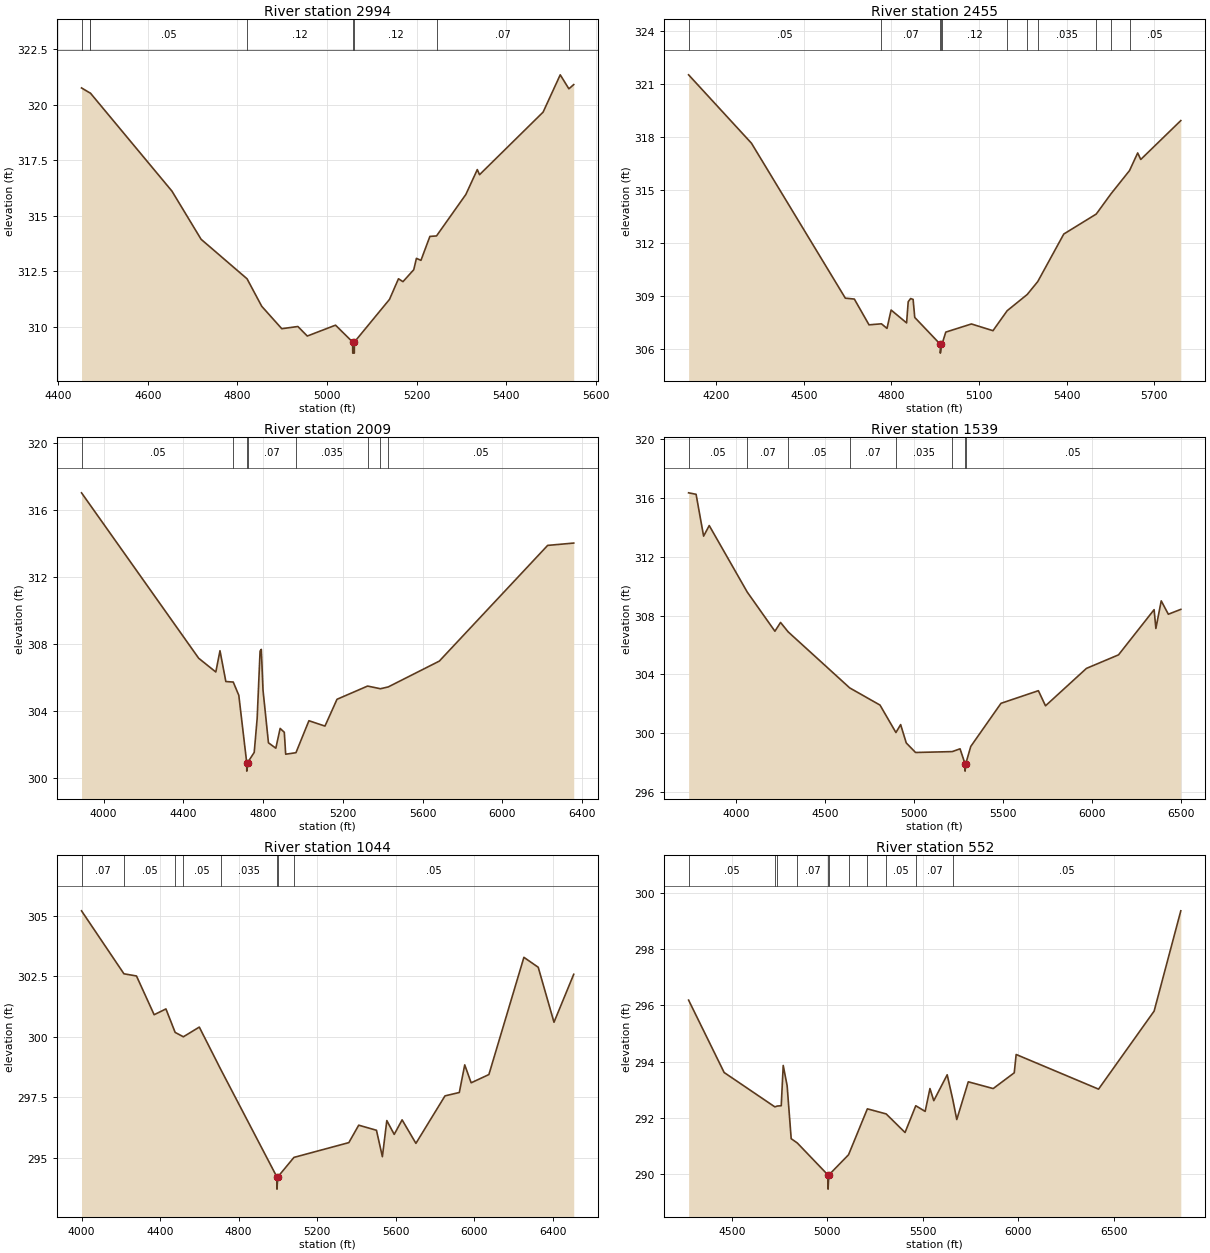
Type RM Length L Ch R = 1,2994,539,539,539
BEGIN DESCRIPTION:
Stream0783 6.0
END DESCRIPTION:
XS GIS Cut Line= 3
      2431224.97     13605424.98      2430770.14     13605113.19
      2430225.01     13605075.00
#Sta/Elev= 30
  4452.3  320.76  4470.6  320.54  4472.0  320.53  4654.0  316.11  4719.0  313.94
  4821.5  312.16  4854.3  310.92  4899.0  309.91  4934.9  310.01  4955.9  309.58
  5018.9  310.07  5057.0  309.31  5057.3  308.81  5060.8  308.81  5061.0  309.31
  5139.2  311.23  5159.3  312.16  5169.3  312.03  5193.4  312.57  5199.3  313.08
  5209.4  312.99  5229.4  314.07  5244.1  314.09  5309.6  315.96  5335.1  317.08
  5340.1  316.85  5481.9  319.67  5520.1  321.35  5539.4  320.72  5550.2  320.91
#Mann=8,-1,0
  4452.3    0.05       0  4470.6    0.07       0  4472.0    0.05       0
  4821.5    0.12       0  5057.0    0.05       0  5061.0    0.12       0
  5244.1    0.07       0  5539.4   0.035       0
Bank Sta=5057,5061
Exp/Cntr=0.3,0.1

Type RM Length L Ch R = 1,2455,446,446,446
BEGIN DESCRIPTION:
Stream0783 5.0
END DESCRIPTION:
XS GIS Cut Line= 3
      2431324.99     13605424.97      2430925.00     13604625.00
      2430174.97     13604875.01
#Sta/Elev= 30
  4105.6  321.50  4320.8  317.63  4642.2  308.86  4673.0  308.81  4723.3  307.35
  4765.8  307.41  4784.8  307.15  4798.8  308.19  4851.9  307.46  4857.4  308.66
  4865.8  308.84  4874.2  308.79  4879.8  307.77  4967.3  306.25  4967.5  305.75
  4971.3  306.25  4973.8  306.29  4986.0  306.94  5073.8  307.40  5147.6  307.02
  5196.2  308.15  5264.9  309.07  5300.9  309.80  5390.0  312.49  5501.1  313.62
  5551.8  314.77  5615.0  316.08  5643.0  317.08  5653.5  316.71  5790.6  318.91
#Mann=11,-1,0
  4105.6    0.05       0  4765.8    0.07       0  4967.3    0.05       0
  4971.3    0.07       0  4973.8    0.12       0  5196.2   0.035       0
  5264.9    0.07       0  5300.9   0.035       0  5501.1    0.05       0
  5551.8   0.035       0  5615.0    0.05       0
Bank Sta=4967.3,4971.3
Exp/Cntr=0.3,0.1

Type RM Length L Ch R = 1,2009,470,470,470
BEGIN DESCRIPTION:
Stream0783 4.0
END DESCRIPTION:
XS GIS Cut Line= 3
      2431825.03     13605175.03      2431175.00     13604275.00
      2429825.03     13604425.00
#Sta/Elev= 30
  3889.8  317.05  4477.4  307.17  4563.3  306.35  4584.2  307.62  4613.6  305.78
  4650.7  305.75  4678.6  304.96  4718.3  300.93  4718.6  300.43  4722.3  300.93
  4755.9  301.55  4770.6  303.57  4785.3  307.60  4791.5  307.70  4800.0  305.27
  4827.3  302.12  4864.3  301.80  4885.9  302.98  4906.8  302.75  4913.7  301.44
  4965.2  301.53  5030.2  303.44  5110.7  303.12  5171.1  304.72  5324.5  305.51
  5389.0  305.35  5428.3  305.46  5684.2  307.00  6227.5  313.91  6358.3  314.05
#Mann=8,-1,0
  3889.8    0.05       0  4650.7    0.07       0  4718.3   0.035       0
  4722.3    0.07       0  4965.2   0.035       0  5324.5    0.05       0
  5389.0   0.035       0  5428.3    0.05       0
Bank Sta=4718.3,4722.3
Exp/Cntr=0.3,0.1

Type RM Length L Ch R = 1,1539,495,495,495
BEGIN DESCRIPTION:
Stream0783 3.0
END DESCRIPTION:
XS GIS Cut Line= 3
      2431875.00     13605124.99      2431475.00     13603925.00
      2429975.00     13603925.00
#Sta/Elev= 30
  3735.1  316.36  3777.2  316.26  3819.4  313.41  3851.0  314.13  4064.5  309.60
  4220.0  306.93  4251.6  307.53  4294.2  306.89  4640.1  303.07  4810.3  301.90
  4899.7  300.03  4926.2  300.57  4957.8  299.32  5010.0  298.67  5216.2  298.73
  5260.0  298.92  5288.0  297.90  5288.2  297.40  5292.0  297.90  5320.0  299.08
  5490.0  302.02  5700.0  302.88  5740.0  301.85  5970.0  304.40  6150.0  305.32
  6350.0  308.40  6360.0  307.12  6390.0  309.00  6430.0  308.09  6500.0  308.42
#Mann=8,-1,0
  3735.1    0.05       0  4064.5    0.07       0  4294.2    0.05       0
  4640.1    0.07       0  4899.7   0.035       0  5216.2    0.05       0
  5288.0   0.035       0  5292.0    0.05       0
Bank Sta=5288,5292
Exp/Cntr=0.3,0.1

Type RM Length L Ch R = 1,1044,492,492,492
BEGIN DESCRIPTION:
Stream0783 2.0
END DESCRIPTION:
XS GIS Cut Line= 3
      2431825.00     13604575.01      2431825.00     13603575.00
      2430324.99     13603425.00
#Sta/Elev= 30
  4000.0  305.20  4216.1  302.60  4280.0  302.51  4370.0  300.91  4430.0  301.15
  4477.0  300.18  4518.9  300.00  4600.0  300.40  4710.1  298.64  4995.5  294.21
  4995.8  293.71  4999.5  294.21  5082.2  295.02  5361.8  295.63  5412.1  296.35
  5502.5  296.14  5532.7  295.05  5555.3  296.54  5593.0  295.97  5633.2  296.57
  5703.5  295.60  5851.7  297.56  5924.6  297.70  5952.2  298.84  5984.9  298.10
  6075.3  298.44  6253.7  303.28  6326.6  302.87  6407.0  300.60  6507.5  302.58
#Mann=8,-1,0
  4000.0    0.07       0  4216.1    0.05       0  4477.0    0.07       0
  4518.9    0.05       0  4710.1   0.035       0  4995.5   0.035       0
  4999.5   0.035       0  5082.2    0.05       0
Bank Sta=4995.5,4999.5
Exp/Cntr=0.3,0.1

Type RM Length L Ch R = 1,552,357,357,357
BEGIN DESCRIPTION:
Stream0783 1.0
END DESCRIPTION:
XS GIS Cut Line= 3
      2432346.52     13603925.68      2432175.00     13603225.00
      2430325.73     13603099.31
#Sta/Elev= 30
  4274.5  296.19  4460.5  293.62  4725.7  292.40  4738.8  292.43  4759.1  292.44
  4769.5  293.87  4790.0  293.15  4811.2  291.27  4842.9  291.12  5003.9  289.98
  5004.1  289.48  5007.9  289.98  5111.2  290.70  5209.7  292.33  5308.1  292.15
  5406.8  291.49  5462.9  292.44  5512.0  292.24  5537.1  293.05  5557.2  292.62
  5627.3  293.54  5657.2  292.64  5677.4  291.95  5737.6  293.29  5867.9  293.05
  5978.1  293.61  5988.1  294.26  6419.1  293.03  6709.8  295.80  6849.4  299.36
#Mann=11,-1,0
  4274.5    0.05       0  4725.7   0.035       0  4738.8    0.05       0
  4842.9    0.07       0  5003.9    0.05       0  5007.9    0.07       0
  5111.2    0.05       0  5209.7   0.035       0  5308.1    0.05       0
  5462.9    0.07       0  5657.2    0.05       0
Bank Sta=5003.9,5007.9
Exp/Cntr=0.3,0.1

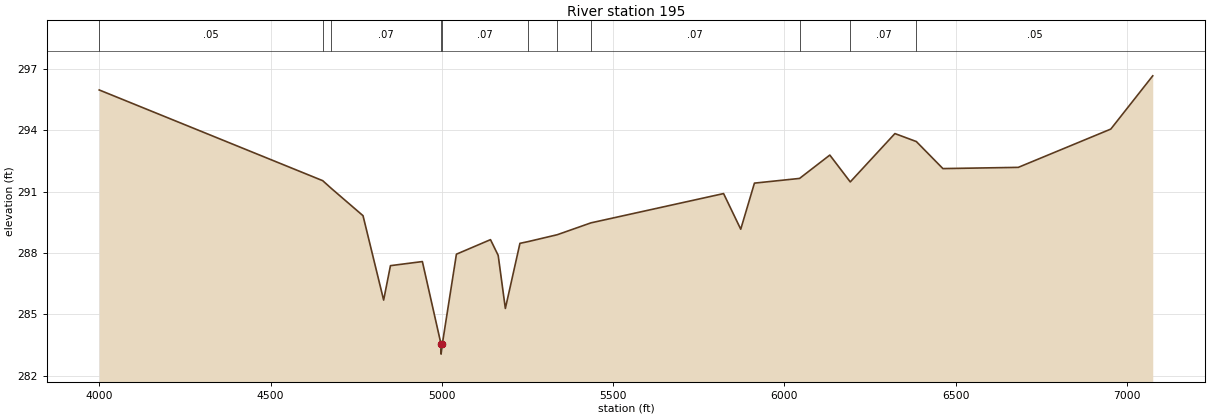
Type RM Length L Ch R = 1,195,0,0,0
BEGIN DESCRIPTION:
XS7722
END DESCRIPTION:
XS GIS Cut Line= 4
      2432409.03     13603932.63      2432478.47     13603092.36
      2432159.03     13602842.36      2430332.68     13602904.86
#Sta/Elev= 30
  3999.7  295.96  4652.3  291.53  4677.6  291.15  4770.0  289.82  4830.2  285.70
  4850.1  287.38  4943.3  287.58  4997.6  283.56  4997.9  283.06  5001.6  283.56
  5042.7  287.94  5142.2  288.65  5164.7  287.88  5185.6  285.29  5228.2  288.47
  5250.9  288.55  5337.0  288.89  5435.5  289.47  5822.8  290.90  5872.9  289.16
  5912.9  291.41  6044.7  291.64  6133.0  292.78  6192.7  291.47  6323.1  293.83
  6385.7  293.44  6463.2  292.12  6683.3  292.18  6953.5  294.05  7075.9  296.65
#Mann=11,-1,0
  3999.7    0.05       0  4652.3   0.035       0  4677.6    0.07       0
  4997.6    0.05       0  5001.6    0.07       0  5250.9   0.035       0
  5337.0    0.05       0  5435.5    0.07       0  6044.7    0.12       0
  6192.7    0.07       0  6385.7    0.05       0
Bank Sta=4997.6,5001.6
Exp/Cntr=0.3,0.1

Chan Stop Cuts=-1