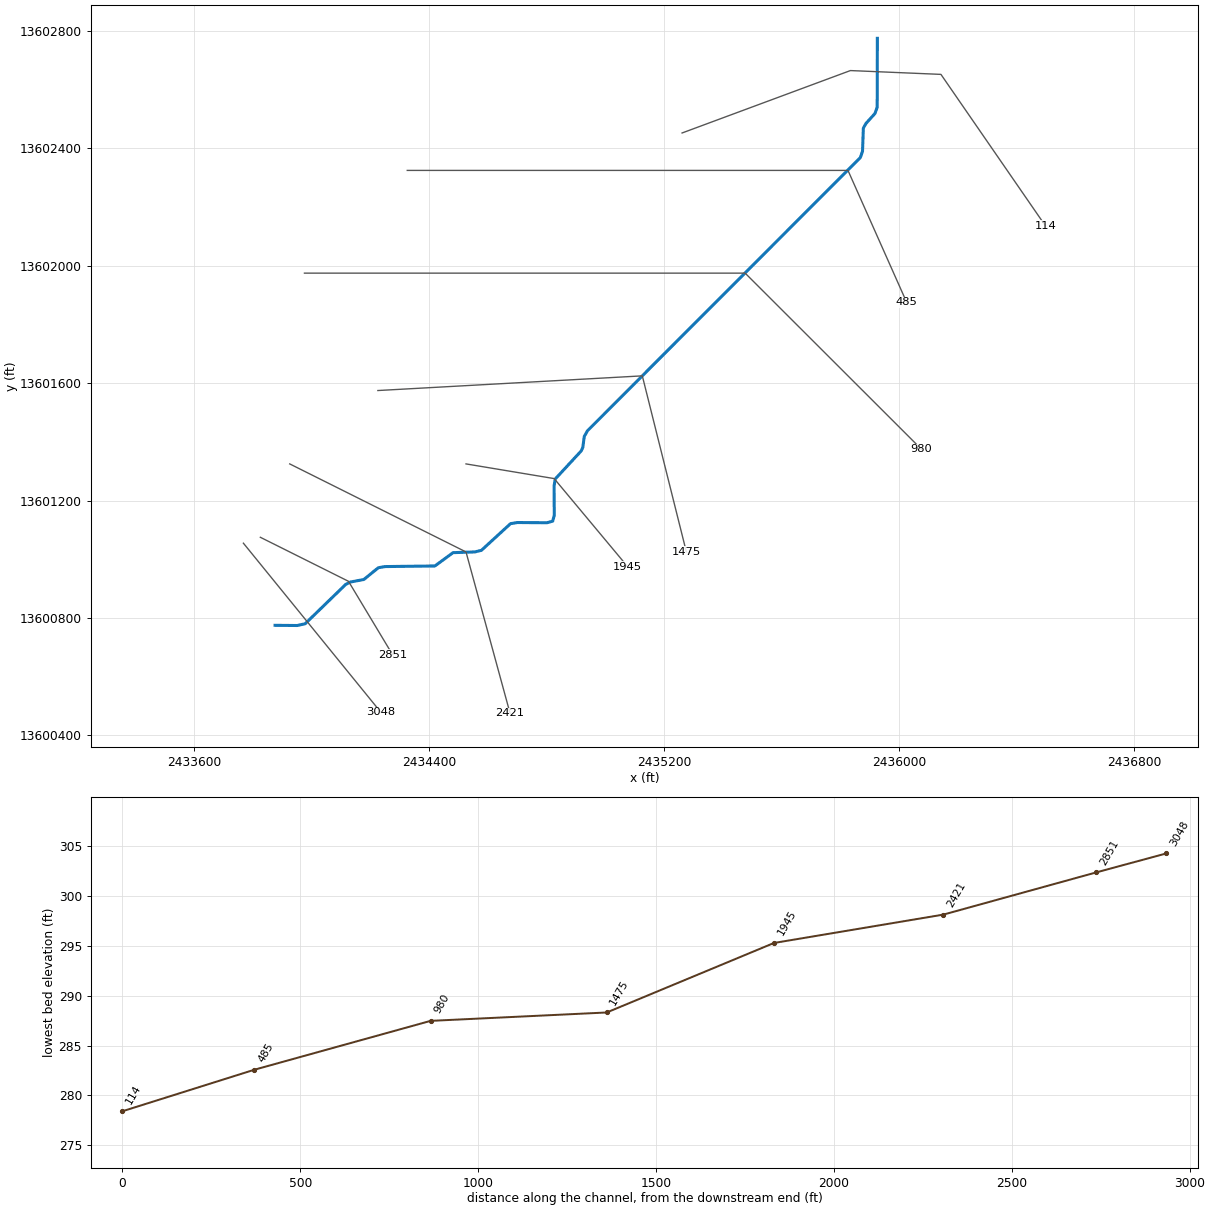
--- Stream0784.prj (project) ---

Proj Title=Stream0784 Base Level Engineering
Current Plan=p01
Default Exp/Contr=0.3,0.1
English Units
Geom File=g01
Flow File=f01
Plan File=p01
BEGIN DESCRIPTION:
Stream0784
END DESCRIPTION:

--- Stream0784.p01 (plan) ---

Plan Title=Multiple Run
Short Identifier=Multiple
Geom File=g01
Flow File=f01
Subcritical Flow
K Sum by GR= 0
Std Step Tol= 0.01
Critical Tol= 0.01
Num of Std Step Trials= 20
Max Error Tol= 0.3
Flow Tol Ratio= 0.001
Split Flow NTrial= 30
Split Flow Tol= 0.02
Split Flow Ratio= 0.02
Log Output Level= 0
Friction Slope Method= 1
Unsteady Friction Slope Method= 2
Unsteady Bridges Friction Slope Method= 1
Parabolic Critical Depth
Global Vel Dist=  1 , 1 , 1
Global Log Level= 0
CheckData=True
Encroach Param= -1, 0, 0, 0
BEGIN DESCRIPTION:
Multiple Run
END DESCRIPTION:

--- Stream0784.f01 (steady flow) ---

Flow Title=Multiple
Number of Profiles=7
Profile Names=10-year,25-year,50-year,1pct_min,100-year,1pct_plu,500-year
River Rch & RM= Stream0784,Reach-1,3048
     523     844    1134     740    1476    2945    2475
Boundary for River Rch & Prof#=Stream0784,Reach-1,1
Up Type=0
Dn Type=3
Dn Slope=0.005
Boundary for River Rch & Prof#=Stream0784,Reach-1,2
Up Type=0
Dn Type=3
Dn Slope=0.005
Boundary for River Rch & Prof#=Stream0784,Reach-1,3
Up Type=0
Dn Type=3
Dn Slope=0.005
Boundary for River Rch & Prof#=Stream0784,Reach-1,4
Up Type=0
Dn Type=3
Dn Slope=0.005
Boundary for River Rch & Prof#=Stream0784,Reach-1,5
Up Type=0
Dn Type=3
Dn Slope=0.005
Boundary for River Rch & Prof#=Stream0784,Reach-1,6
Up Type=0
Dn Type=3
Dn Slope=0.005
Boundary for River Rch & Prof#=Stream0784,Reach-1,7
Up Type=0
Dn Type=3
Dn Slope=0.005

--- Stream0784.g01 (geometry) ---

Geom Title=Existing Conditions

River Reach=Stream0784,Reach-1
Reach XY= 30
      2433875.00     13600775.00      2433950.25     13600774.41
      2433977.50     13600780.35      2434115.32     13600914.24
      2434131.03     13600922.50      2434177.17     13600931.14
      2434226.55     13600971.25      2434249.91     13600975.21
      2434419.06     13600977.26      2434480.98     13601022.64
      2434554.95     13601025.13      2434577.42     13601030.54
      2434676.48     13601121.44      2434699.92     13601125.26
      2434800.41     13601124.61      2434819.99     13601130.01
      2434825.39     13601149.59      2434824.74     13601250.08
      2434828.56     13601273.52      2434916.82     13601368.96
      2434922.46     13601381.05      2434927.53     13601418.95
      2434938.63     13601438.21      2435867.14     13602368.83
      2435874.48     13602390.22      2435877.36     13602469.02
      2435885.90     13602484.63      2435916.86     13602518.94
      2435924.48     13602540.22      2435925.00     13602775.00

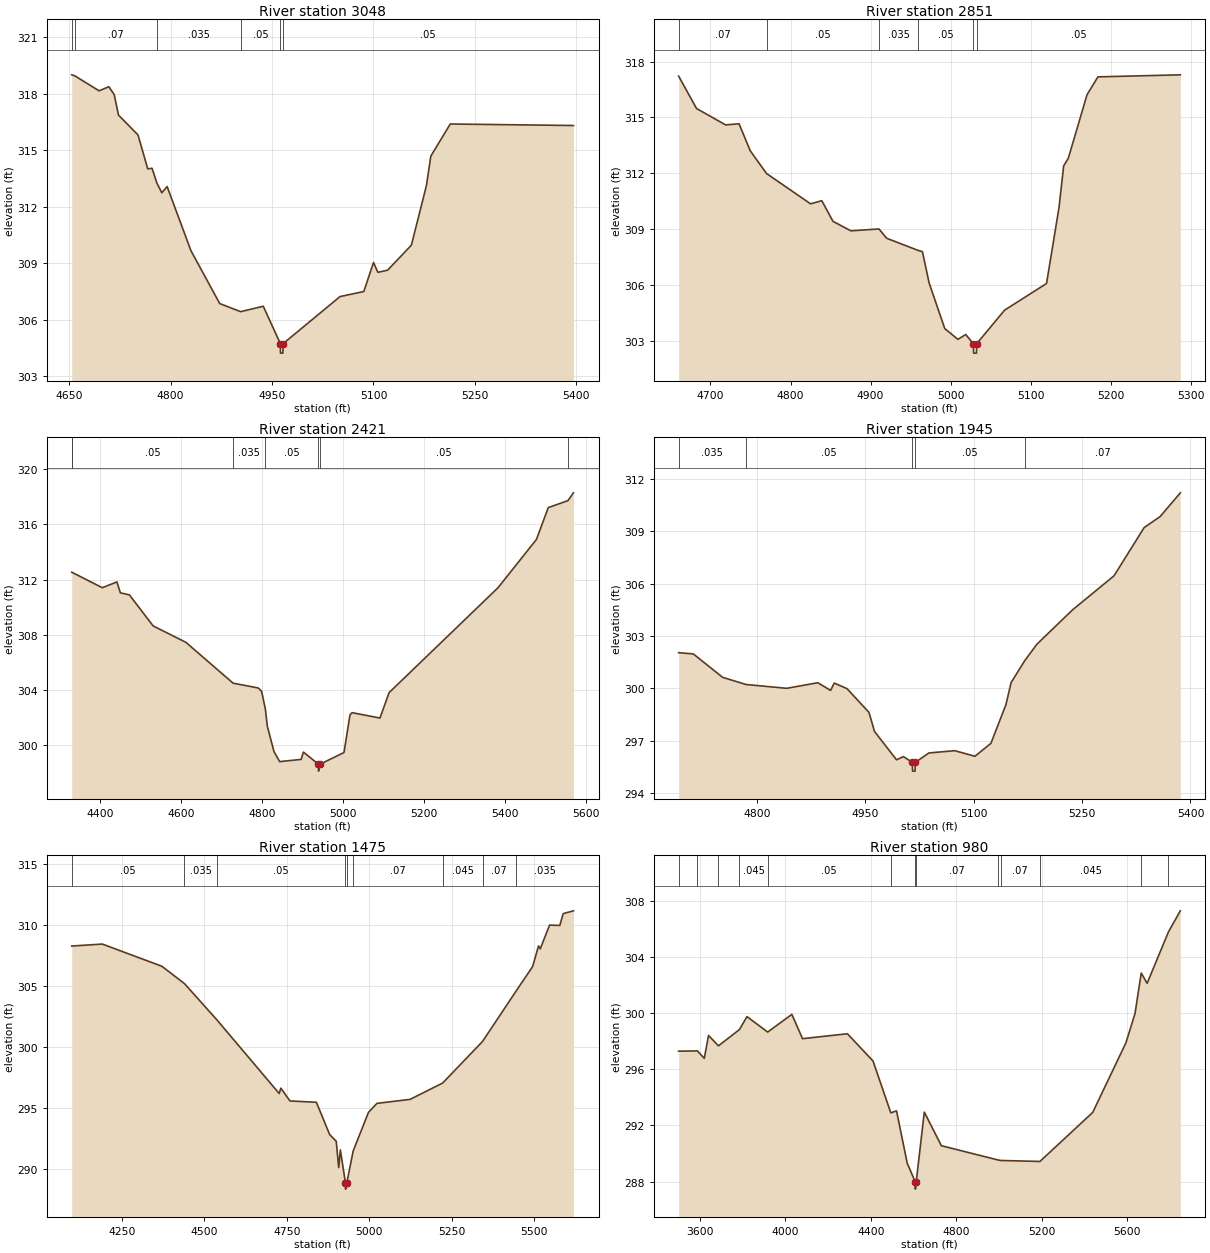
Type RM Length L Ch R = 1,3048,197,197,197
BEGIN DESCRIPTION:
XS7724
END DESCRIPTION:
XS GIS Cut Line= 2
      2433767.30     13601054.91      2434235.10     13600478.83
#Sta/Elev= 30
  4653.7  319.01  4658.1  318.96  4694.2  318.16  4708.6  318.38  4716.5  317.96
  4722.9  316.87  4751.7  315.82  4766.1  314.02  4772.5  314.05  4779.5  313.28
  4786.9  312.75  4794.8  313.08  4830.0  309.68  4872.6  306.87  4903.6  306.44
  4937.0  306.73  4962.3  304.74  4962.5  304.24  4966.0  304.24  4966.3  304.74
  5050.5  307.24  5085.7  307.51  5100.1  309.05  5106.5  308.53  5120.9  308.64
  5156.1  309.97  5178.4  313.14  5184.8  314.69  5213.6  316.40  5395.8  316.32
#Mann=6,-1,0
  4653.7    0.05       0  4658.1    0.07       0  4779.5   0.035       0
  4903.6    0.05       0  4962.3    0.05       0  4966.3    0.05       0
Bank Sta=4962.3,4966.3
Exp/Cntr=0.3,0.1

Type RM Length L Ch R = 1,2851,430,430,430
BEGIN DESCRIPTION:
Stream0784 6.0
END DESCRIPTION:
XS GIS Cut Line= 3
      2433824.98     13601075.01      2434125.00     13600925.00
      2434275.01     13600674.99
#Sta/Elev= 30
  4660.2  317.22  4682.6  315.48  4718.9  314.60  4735.7  314.66  4749.7  313.21
  4770.0  311.99  4825.1  310.36  4839.1  310.53  4853.1  309.42  4875.4  308.91
  4910.6  309.01  4920.2  308.51  4959.4  307.86  4964.9  307.79  4973.3  306.10
  4992.8  303.66  5009.2  303.08  5019.0  303.34  5028.6  302.84  5028.9  302.34
  5032.4  302.34  5032.6  302.84  5067.6  304.65  5120.0  306.08  5135.6  310.17
  5141.4  312.40  5147.2  312.81  5170.6  316.22  5184.2  317.18  5287.2  317.29
#Mann=6,-1,0
  4660.2    0.07       0  4770.0    0.05       0  4910.6   0.035       0
  4959.4    0.05       0  5028.6    0.05       0  5032.6    0.05       0
Bank Sta=5028.6,5032.6
Exp/Cntr=0.3,0.1

Type RM Length L Ch R = 1,2421,476,476,476
BEGIN DESCRIPTION:
Stream0784 5.0
END DESCRIPTION:
XS GIS Cut Line= 3
      2433924.98     13601325.01      2434525.00     13601025.00
      2434674.99     13600475.03
#Sta/Elev= 30
  4329.1  312.53  4329.4  312.53  4404.6  311.41  4440.9  311.83  4449.3  311.04
  4471.7  310.89  4530.4  308.64  4611.4  307.45  4728.1  304.49  4790.3  304.14
  4798.7  303.90  4808.2  302.58  4812.7  301.39  4829.4  299.52  4843.4  298.80
  4896.5  298.96  4902.1  299.49  4939.3  298.61  4939.5  298.11  4943.3  298.61
  5002.5  299.46  5017.2  302.17  5022.4  302.35  5091.5  301.96  5114.0  303.80
  5383.5  311.41  5478.5  314.91  5507.8  317.22  5556.3  317.72  5570.0  318.29
#Mann=7,-1,0
  4329.1    0.07       0  4329.4    0.05       0  4728.1   0.035       0
  4808.2    0.05       0  4939.3    0.05       0  4943.3    0.05       0
  5556.3    0.07       0
Bank Sta=4939.3,4943.3
Exp/Cntr=0.3,0.1

Type RM Length L Ch R = 1,1945,470,470,470
BEGIN DESCRIPTION:
Stream0784 4.0
END DESCRIPTION:
XS GIS Cut Line= 3
      2434524.95     13601325.01      2434825.00     13601275.00
      2435075.00     13600975.00
#Sta/Elev= 30
  4691.3  302.05  4711.6  301.98  4752.2  300.64  4784.4  300.23  4840.9  300.01
  4884.0  300.33  4901.7  299.89  4906.8  300.31  4924.5  299.99  4954.9  298.63
  4962.5  297.54  4993.0  295.92  5002.6  296.10  5015.0  295.77  5015.2  295.27
  5018.7  295.27  5019.0  295.77  5037.8  296.31  5073.6  296.44  5101.6  296.12
  5123.7  296.86  5144.5  299.07  5151.7  300.34  5170.5  301.59  5187.5  302.54
  5237.0  304.51  5294.2  306.45  5335.9  309.21  5358.0  309.84  5386.0  311.20
#Mann=5,-1,0
  4691.3   0.035       0  4784.4    0.05       0  5015.0    0.05       0
  5019.0    0.05       0  5170.5    0.07       0
Bank Sta=5015,5019
Exp/Cntr=0.3,0.1

Type RM Length L Ch R = 1,1475,495,495,495
BEGIN DESCRIPTION:
Stream0784 3.0
END DESCRIPTION:
XS GIS Cut Line= 3
      2434224.98     13601575.00      2435125.00     13601625.00
      2435275.01     13601024.97
#Sta/Elev= 30
  4098.6  308.27  4191.3  308.43  4371.5  306.61  4439.9  305.19  4538.3  302.21
  4727.1  296.16  4732.1  296.60  4759.6  295.55  4839.8  295.44  4879.8  292.80
  4899.9  292.24  4907.4  290.08  4912.4  291.53  4927.9  288.81  4928.1  288.31
  4931.9  288.81  4951.2  291.44  4997.5  294.61  5023.2  295.35  5123.7  295.68
  5222.3  297.02  5343.3  300.44  5444.2  304.55  5494.8  306.58  5512.8  308.28
  5518.0  308.04  5546.3  309.99  5577.2  309.96  5587.5  310.93  5618.5  311.16
#Mann=9,-1,0
  4098.6    0.05       0  4439.9   0.035       0  4538.3    0.05       0
  4927.9    0.07       0  4931.9    0.05       0  4951.2    0.07       0
  5222.3   0.045       0  5343.3    0.07       0  5444.2   0.035       0
Bank Sta=4927.9,4931.9
Exp/Cntr=0.3,0.1

Type RM Length L Ch R = 1,980,495,495,495
BEGIN DESCRIPTION:
Stream0784 2.0
END DESCRIPTION:
XS GIS Cut Line= 3
      2433975.01     13601975.00      2435475.00     13601975.00
      2436074.98     13601375.02
#Sta/Elev= 30
  3500.0  297.29  3588.0  297.31  3620.0  296.78  3640.0  298.41  3686.4  297.67
  3784.7  298.83  3820.0  299.75  3916.8  298.65  4030.0  299.91  4080.0  298.18
  4290.0  298.53  4410.0  296.59  4493.2  292.90  4520.0  293.04  4570.0  289.32
  4608.0  287.97  4608.2  287.47  4612.0  287.97  4650.0  292.95  4730.0  290.56
  4993.9  289.55  5007.5  289.51  5191.2  289.44  5438.4  292.93  5594.0  297.89
  5636.4  299.97  5665.5  302.85  5693.0  302.12  5793.0  305.78  5848.5  307.28
#Mann=13,-1,0
  3500.0    0.07       0  3588.0   0.035       0  3686.4    0.05       0
  3784.7   0.045       0  3916.8    0.05       0  4493.2    0.07       0
  4608.0    0.05       0  4612.0    0.07       0  4993.9    0.05       0
  5007.5    0.07       0  5191.2   0.045       0  5665.5   0.035       0
  5793.0    0.07       0
Bank Sta=4608,4612
Exp/Cntr=0.3,0.1

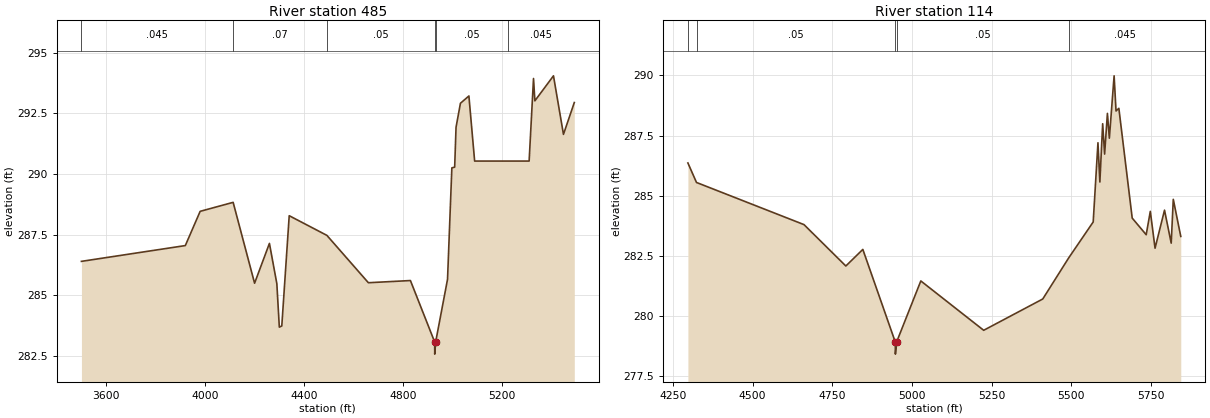
Type RM Length L Ch R = 1,485,371,371,371
BEGIN DESCRIPTION:
Stream0784 1.0
END DESCRIPTION:
XS GIS Cut Line= 3
      2434324.97     13602325.00      2435825.00     13602325.00
      2436025.01     13601874.98
#Sta/Elev= 30
  3499.7  286.40  3919.7  287.05  3979.7  288.46  4113.0  288.83  4199.7  285.50
  4259.7  287.14  4289.7  285.48  4299.7  283.69  4309.7  283.74  4339.7  288.28
  4492.0  287.47  4659.7  285.52  4829.7  285.61  4927.7  283.08  4928.0  282.58
  4931.7  283.08  4979.7  285.66  4997.2  290.25  5008.6  290.28  5014.1  291.92
  5031.9  292.91  5066.1  293.21  5089.3  290.53  5224.9  290.53  5309.6  290.53
  5327.3  293.93  5332.8  293.01  5408.0  294.04  5448.4  291.63  5492.2  292.94
#Mann=6,-1,0
  3499.7   0.045       0  4113.0    0.07       0  4492.0    0.05       0
  4927.7    0.05       0  4931.7    0.05       0  5224.9   0.045       0
Bank Sta=4927.7,4931.7
Exp/Cntr=0.3,0.1

Type RM Length L Ch R = 1,114,0,0,0
BEGIN DESCRIPTION:
XS7723
END DESCRIPTION:
XS GIS Cut Line= 4
      2435260.32     13602452.52      2435833.25     13602665.19
      2436141.41     13602652.17      2436497.31     13602135.68
#Sta/Elev= 30
  4297.0  286.36  4324.0  285.55  4661.3  283.80  4792.7  282.08  4846.0  282.77
  4947.9  278.92  4948.2  278.42  4951.9  278.92  5028.0  281.46  5225.3  279.41
  5410.7  280.71  5492.2  282.42  5569.0  283.91  5583.9  287.20  5589.9  285.57
  5598.7  287.99  5604.8  286.73  5613.6  288.42  5619.7  287.39  5634.6  289.98
  5640.6  288.52  5649.5  288.63  5691.4  284.07  5735.3  283.38  5748.2  284.35
  5763.1  282.82  5792.8  284.40  5813.8  283.03  5820.3  284.85  5843.8  283.31
#Mann=5,-1,0
  4297.0    0.07       0  4324.0    0.05       0  4947.9    0.05       0
  4951.9    0.05       0  5492.2   0.045       0
Bank Sta=4947.9,4951.9
Exp/Cntr=0.3,0.1

Chan Stop Cuts=-1