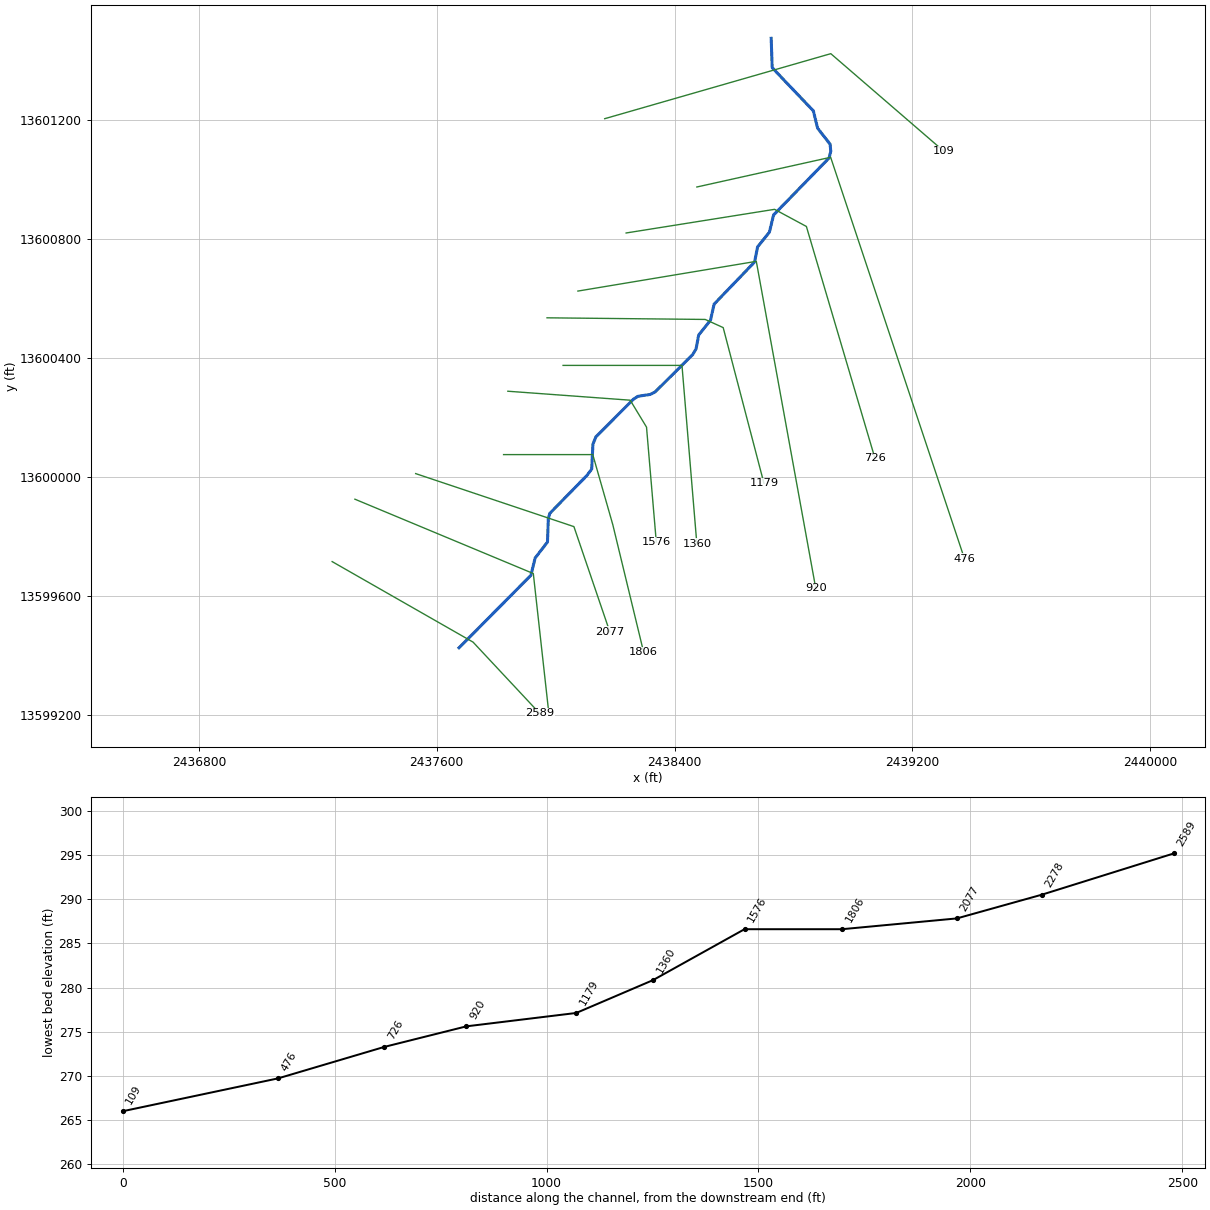
--- Stream0785.prj (project) ---

Proj Title=Stream0785 Base Level Engineering
Current Plan=p01
Default Exp/Contr=0.3,0.1
English Units
Geom File=g01
Flow File=f01
Plan File=p01
Y Axis Title=Elevation
X Axis Title(PF)=Main Channel Distance
X Axis Title(XS)=Station
BEGIN DESCRIPTION:
Stream0785
END DESCRIPTION:
DSS Export Rating Curves= 0
DSS Export Rating Curve Sorted= 0
DSS Export Volume Flow Curves= 0
DXF OffsetX= 0
DXF OffsetY= 0
DXF ScaleX= 1
DXF ScaleY= 10

--- Stream0785.p01 (plan) ---

Plan Title=Multiple Run
Short Identifier=Multiple
Geom File=g01
Flow File=f01
Subcritical Flow
K Sum by GR= 0
Std Step Tol= 0.01
Critical Tol= 0.01
Num of Std Step Trials= 20
Max Error Tol= 0.3
Flow Tol Ratio= 0.001
Split Flow NTrial= 30
Split Flow Tol= 0.02
Split Flow Ratio= 0.02
Log Output Level= 0
Friction Slope Method= 1
Unsteady Friction Slope Method= 2
Unsteady Bridges Friction Slope Method= 1
Parabolic Critical Depth
Global Vel Dist=  1 , 1 , 1
Global Log Level= 0
CheckData=True
Encroach Param= -1, 0, 0, 0
BEGIN DESCRIPTION:
Multiple Run
END DESCRIPTION:

--- Stream0785.f01 (steady flow) ---

Flow Title=Multiple
Number of Profiles=7
Profile Names=10-year,25-year,50-year,1pct_min,100-year,1pct_plu,500-year
River Rch & RM= Stream0785,Reach-1,2589
     461     742     996     650    1296    2587    2173
Boundary for River Rch & Prof#=Stream0785,Reach-1,1
Up Type=0
Dn Type=3
Dn Slope=0.005
Boundary for River Rch & Prof#=Stream0785,Reach-1,2
Up Type=0
Dn Type=3
Dn Slope=0.005
Boundary for River Rch & Prof#=Stream0785,Reach-1,3
Up Type=0
Dn Type=3
Dn Slope=0.005
Boundary for River Rch & Prof#=Stream0785,Reach-1,4
Up Type=0
Dn Type=3
Dn Slope=0.005
Boundary for River Rch & Prof#=Stream0785,Reach-1,5
Up Type=0
Dn Type=3
Dn Slope=0.005
Boundary for River Rch & Prof#=Stream0785,Reach-1,6
Up Type=0
Dn Type=3
Dn Slope=0.005
Boundary for River Rch & Prof#=Stream0785,Reach-1,7
Up Type=0
Dn Type=3
Dn Slope=0.005

--- Stream0785.g01 (geometry) ---

Geom Title=Existing Conditions

River Reach=Stream0785,Reach-1
Reach XY= 30
      2437675.00     13599425.00      2437916.86     13599668.94
      2437931.14     13599727.17      2437972.67     13599780.97
      2437975.52     13599859.78      2437980.52     13599877.43
      2438105.37     13600004.85      2438121.39     13600026.50
      2438125.53     13600109.78      2438135.52     13600134.79
      2438261.79     13600261.37      2438276.65     13600271.02
      2438318.95     13600277.53      2438334.68     13600285.78
      2438461.38     13600411.78      2438472.50     13600431.03
      2438481.10     13600477.19      2438520.81     13600526.74
      2438533.14     13600581.06      2438669.17     13600722.70
      2438679.19     13600773.26      2438718.90     13600822.81
      2438733.14     13600881.06      2438919.91     13601072.70
      2438925.41     13601095.13      2438923.24     13601118.88
      2438881.18     13601172.81      2438866.86     13601231.06
      2438728.38     13601376.40      2438725.00     13601475.00

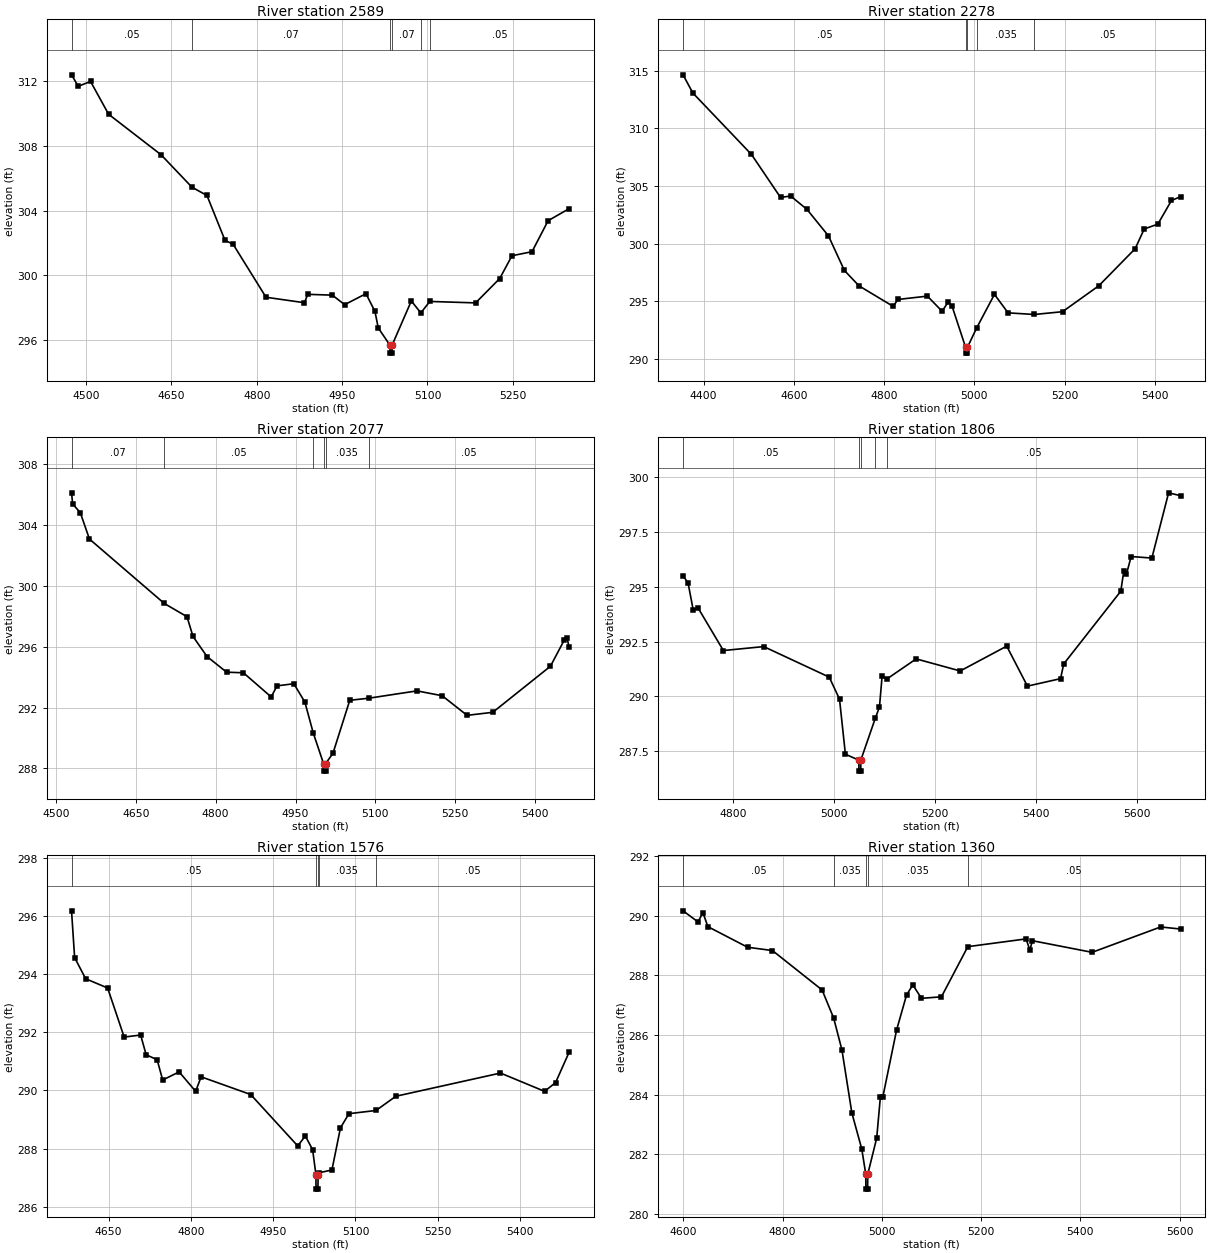
Type RM Length L Ch R = 1,2589,311,311,311
BEGIN DESCRIPTION:
XS7726
END DESCRIPTION:
XS GIS Cut Line= 3
      2437248.41     13599715.12      2437722.40     13599444.27
      2437946.38     13599204.66
#Sta/Elev= 30
  4474.7  312.40  4486.5  311.69  4508.1  311.99  4539.8  309.96  4632.0  307.45
  4686.3  305.44  4712.6  304.93  4744.2  302.16  4758.7  301.90  4816.3  298.63
  4883.9  298.29  4889.6  298.81  4932.8  298.76  4954.5  298.17  4991.9  298.85
  5007.7  297.75  5013.5  296.73  5033.9  295.67  5034.2  295.17  5037.7  295.17
  5037.9  295.67  5071.6  298.40  5088.3  297.66  5104.1  298.37  5184.5  298.28
  5226.9  299.79  5248.4  301.20  5283.6  301.45  5311.9  303.37  5348.6  304.11
#Mann=6,-1,0
  4474.7    0.05       0  4686.3    0.07       0  5033.9    0.05       0
  5037.9    0.07       0  5088.3   0.035       0  5104.1    0.05       0
Bank Sta=5033.9,5037.9
Exp/Cntr=0.3,0.1

Type RM Length L Ch R = 1,2278,201,201,201
BEGIN DESCRIPTION:
Stream0785 5.0
END DESCRIPTION:
XS GIS Cut Line= 3
      2437325.03     13599924.99      2437925.00     13599675.00
      2437975.00     13599225.04
#Sta/Elev= 30
  4354.3  314.63  4375.9  313.06  4505.9  307.73  4570.4  304.00  4592.6  304.13
  4628.9  302.97  4676.6  300.67  4711.8  297.68  4744.3  296.34  4820.1  294.56
  4830.4  295.16  4895.9  295.45  4928.4  294.14  4942.0  294.94  4950.1  294.63
  4980.6  291.01  4980.9  290.51  4984.4  290.51  4984.6  291.01  5004.9  292.68
  5044.5  295.60  5074.7  294.00  5133.0  293.86  5195.4  294.10  5275.9  296.35
  5356.4  299.56  5376.5  301.27  5406.7  301.69  5436.9  303.74  5457.0  304.07
#Mann=5,-1,0
  4354.3    0.05       0  4980.6    0.05       0  4984.6    0.05       0
  5004.9   0.035       0  5133.0    0.05       0
Bank Sta=4980.6,4984.6
Exp/Cntr=0.3,0.1

Type RM Length L Ch R = 1,2077,271,271,271
BEGIN DESCRIPTION:
H21052
END DESCRIPTION:
XS GIS Cut Line= 3
      2437529.35     13600011.08      2438061.59     13599832.76
      2438182.09     13599479.46
#Sta/Elev= 30
  4529.2  306.13  4531.3  305.40  4545.7  304.82  4562.8  303.09  4703.5  298.85
  4746.1  297.98  4757.4  296.68  4783.7  295.36  4820.5  294.33  4852.1  294.29
  4904.3  292.70  4915.2  293.43  4946.8  293.57  4967.6  292.36  4983.3  290.33
  5002.6  288.32  5002.9  287.82  5006.4  287.82  5006.6  288.32  5020.3  288.99
  5051.9  292.48  5088.1  292.62  5178.2  293.10  5225.5  292.78  5272.3  291.49
  5320.6  291.69  5428.9  294.72  5455.0  296.45  5460.3  296.58  5463.8  295.97
#Mann=6,-1,0
  4529.2    0.07       0  4703.5    0.05       0  4983.3   0.035       0
  5002.6   0.035       0  5006.6   0.035       0  5088.1    0.05       0
Bank Sta=5002.6,5006.6
Exp/Cntr=0.3,0.1

Type RM Length L Ch R = 1,1806,230,230,230
BEGIN DESCRIPTION:
Stream0785 4.0
END DESCRIPTION:
XS GIS Cut Line= 4
      2437824.98     13600075.00      2438125.00     13600075.00
      2438192.34     13599839.30      2438296.22     13599409.73
#Sta/Elev= 30
  4700.0  295.50  4710.0  295.16  4720.0  293.95  4730.0  294.02  4780.0  292.09
  4860.0  292.27  4990.0  290.88  5010.4  289.88  5022.1  287.37  5048.7  287.10
  5049.0  286.60  5052.5  286.60  5052.7  287.10  5081.3  289.00  5089.7  289.52
  5094.9  290.92  5104.1  290.79  5162.5  291.71  5249.9  291.16  5342.2  292.29
  5383.3  290.47  5449.0  290.81  5455.3  291.48  5568.5  294.79  5574.6  295.72
  5579.7  295.56  5589.1  296.37  5630.2  296.30  5663.4  299.27  5687.1  299.14
#Mann=5,-1,0
  4700.0    0.05       0  5048.7    0.05       0  5052.7    0.05       0
  5081.3   0.035       0  5104.1    0.05       0
Bank Sta=5048.7,5052.7
Exp/Cntr=0.3,0.1

Type RM Length L Ch R = 1,1576,216,216,216
BEGIN DESCRIPTION:
H21051
END DESCRIPTION:
XS GIS Cut Line= 4
      2437839.39     13600288.14      2438250.87     13600257.97
      2438305.74     13600167.44      2438338.66     13599780.58
#Sta/Elev= 30
  4582.5  296.19  4588.1  294.58  4608.2  293.85  4648.3  293.53  4678.4  291.84
  4708.4  291.91  4718.5  291.23  4738.5  291.06  4748.6  290.36  4778.6  290.64
  4808.7  289.97  4818.7  290.47  4909.0  289.86  4994.7  288.09  5008.6  288.43
  5021.9  287.96  5027.9  287.10  5028.1  286.60  5031.6  286.60  5031.9  287.10
  5032.7  287.16  5057.1  287.26  5072.6  288.71  5088.1  289.20  5137.4  289.31
  5173.6  289.80  5364.3  290.60  5444.6  289.97  5464.7  290.27  5489.2  291.31
#Mann=5,-1,0
  4582.5    0.05       0  5027.9    0.05       0  5031.9    0.05       0
  5032.7   0.035       0  5137.4    0.05       0
Bank Sta=5027.9,5031.9
Exp/Cntr=0.3,0.1

Type RM Length L Ch R = 1,1360,181,181,181
BEGIN DESCRIPTION:
Stream0785 3.0
END DESCRIPTION:
XS GIS Cut Line= 3
      2438025.03     13600375.00      2438425.00     13600375.00
      2438475.00     13599775.05
#Sta/Elev= 30
  4599.7  290.16  4629.7  289.79  4639.7  290.10  4649.7  289.63  4729.7  288.94
  4779.7  288.83  4879.7  287.51  4903.0  286.57  4919.7  285.50  4939.7  283.39
  4959.7  282.18  4967.7  281.34  4967.9  280.84  4971.4  280.84  4971.7  281.34
  4989.7  282.55  4997.2  283.94  5002.2  283.94  5029.8  286.17  5049.8  287.34
  5062.4  287.68  5079.9  287.23  5120.1  287.28  5173.2  288.96  5290.7  289.22
  5298.2  288.84  5303.2  289.16  5423.6  288.77  5561.6  289.62  5601.7  289.55
#Mann=5,-1,0
  4599.7    0.05       0  4903.0   0.035       0  4967.7   0.035       0
  4971.7   0.035       0  5173.2    0.05       0
Bank Sta=4967.7,4971.7
Exp/Cntr=0.3,0.1

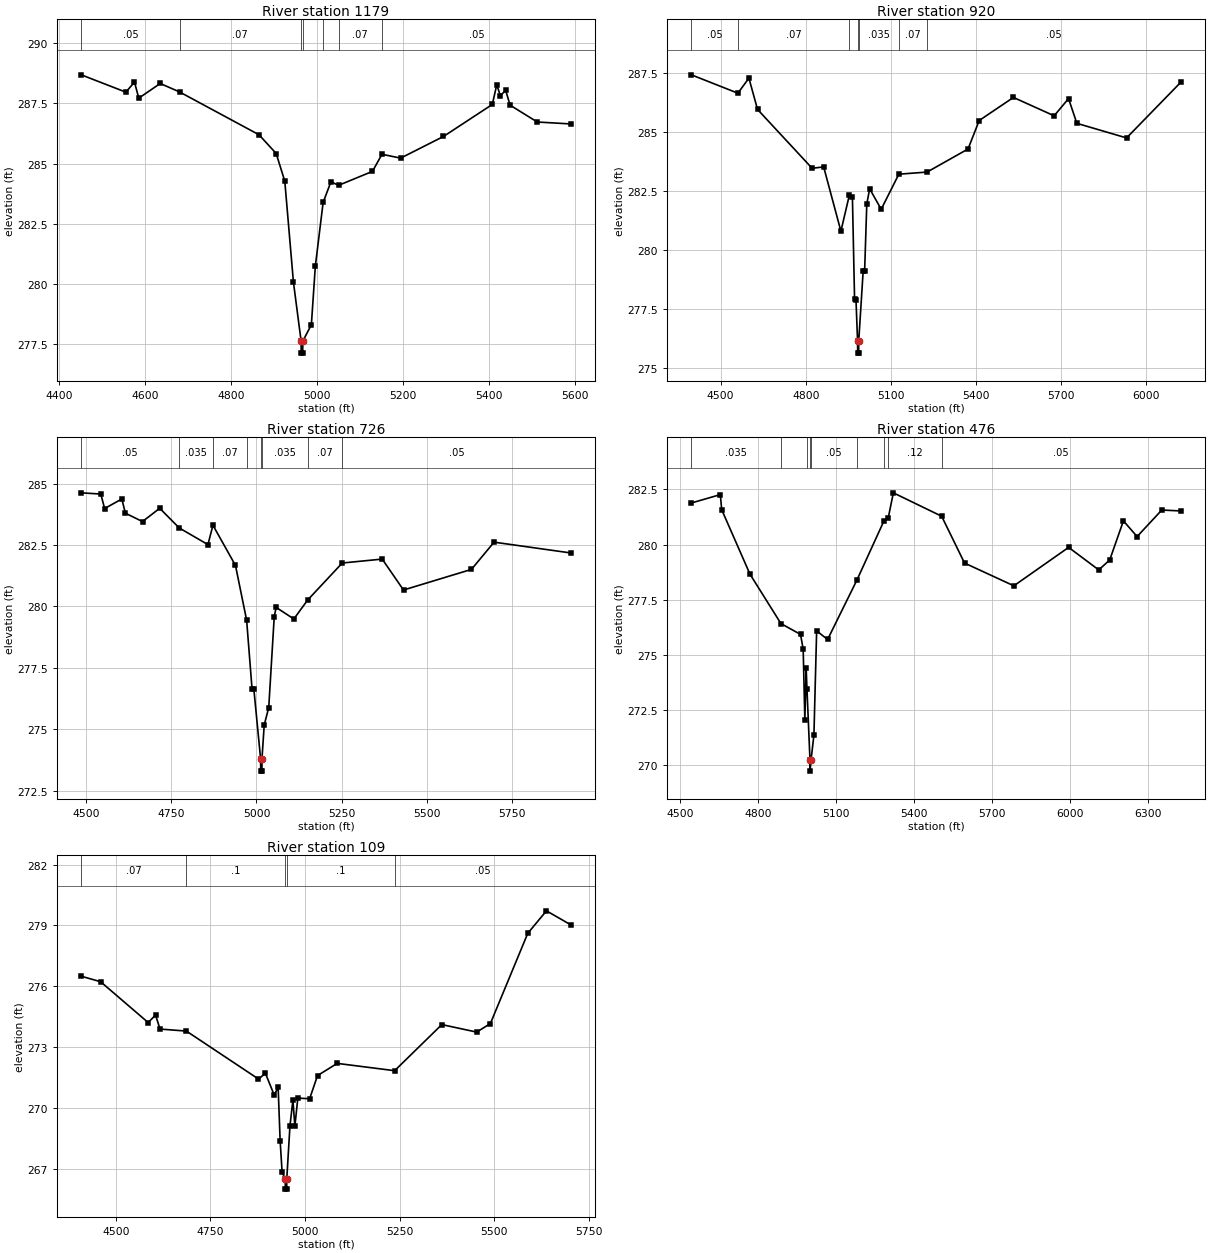
Type RM Length L Ch R = 1,1179,259,259,259
BEGIN DESCRIPTION:
H21050
END DESCRIPTION:
XS GIS Cut Line= 4
      2437971.07     13600535.04      2438503.26     13600529.56
      2438563.61     13600502.12      2438700.77     13599978.19
#Sta/Elev= 30
  4450.8  288.69  4554.7  287.97  4574.7  288.39  4584.7  287.72  4634.7  288.33
  4679.6  287.98  4864.8  286.20  4904.8  285.42  4924.8  284.27  4944.9  280.08
  4962.8  277.63  4963.0  277.13  4966.5  277.13  4966.8  277.63  4986.7  278.31
  4995.9  280.74  5014.1  283.39  5032.3  284.25  5050.0  284.10  5129.0  284.68
  5151.1  285.39  5194.6  285.23  5294.4  286.13  5408.1  287.46  5418.5  288.28
  5426.8  287.82  5439.1  288.05  5449.5  287.43  5512.8  286.73  5590.9  286.65
#Mann=7,-1,0
  4450.8    0.05       0  4679.6    0.07       0  4962.8    0.05       0
  4966.8    0.07       0  5014.1   0.035       0  5050.0    0.07       0
  5151.1    0.05       0
Bank Sta=4962.8,4966.8
Exp/Cntr=0.3,0.1

Type RM Length L Ch R = 1,920,194,194,194
BEGIN DESCRIPTION:
Stream0785 2.0
END DESCRIPTION:
XS GIS Cut Line= 3
      2438074.96     13600624.99      2438675.00     13600725.00
      2438874.99     13599625.05
#Sta/Elev= 30
  4396.9  287.44  4560.8  286.66  4599.7  287.30  4630.1  285.97  4822.7  283.47
  4863.3  283.53  4924.1  280.80  4953.7  282.32  4964.7  282.24  4972.3  277.90
  4977.3  277.89  4982.9  276.12  4983.2  275.62  4986.7  275.62  4986.9  276.12
  5002.7  279.12  5007.8  279.12  5015.4  281.96  5025.5  282.60  5066.2  281.73
  5128.4  283.22  5228.0  283.31  5372.4  284.29  5411.8  285.50  5532.5  286.48
  5676.0  285.70  5726.9  286.43  5756.1  285.38  5931.4  284.76  6123.2  287.13
#Mann=7,-1,0
  4396.9    0.05       0  4560.8    0.07       0  4953.7   0.035       0
  4982.9   0.035       0  4986.9   0.035       0  5128.4    0.07       0
  5228.0    0.05       0
Bank Sta=4982.9,4986.9
Exp/Cntr=0.3,0.1

Type RM Length L Ch R = 1,726,250,250,250
BEGIN DESCRIPTION:
H21049
END DESCRIPTION:
XS GIS Cut Line= 4
      2438237.15     13600820.34      2438736.44     13600899.90
      2438843.43     13600842.29      2439073.88     13600063.16
#Sta/Elev= 30
  4484.7  284.63  4542.1  284.58  4553.4  283.99  4604.0  284.38  4614.4  283.80
  4664.8  283.46  4715.4  284.00  4772.7  283.20  4857.2  282.52  4871.9  283.31
  4938.2  281.67  4971.0  279.44  4987.0  276.62  4992.3  276.62  5012.1  273.79
  5012.4  273.29  5015.9  273.29  5016.1  273.79  5022.7  275.17  5036.0  275.88
  5052.2  279.59  5057.9  279.96  5109.9  279.49  5150.3  280.26  5252.2  281.77
  5369.7  281.93  5432.3  280.67  5632.1  281.51  5698.6  282.62  5924.3  282.18
#Mann=8,-1,0
  4484.7    0.05       0  4772.7   0.035       0  4871.9    0.07       0
  4971.0   0.035       0  5012.1   0.035       0  5016.1   0.035       0
  5150.3    0.07       0  5252.2    0.05       0
Bank Sta=5012.1,5016.1
Exp/Cntr=0.3,0.1

Type RM Length L Ch R = 1,476,367,367,367
BEGIN DESCRIPTION:
Stream0785 1.0
END DESCRIPTION:
XS GIS Cut Line= 3
      2438475.04     13600975.01      2438925.00     13601075.00
      2439375.01     13599724.97
#Sta/Elev= 30
  4543.6  281.88  4655.0  282.26  4660.1  281.58  4768.9  278.66  4888.2  276.42
  4963.6  275.93  4973.8  275.26  4980.2  272.05  4985.3  274.40  4988.3  273.47
  5000.0  270.24  5000.2  269.74  5004.0  270.24  5015.1  271.37  5025.6  276.09
  5067.8  275.70  5181.0  278.40  5283.9  281.05  5301.4  281.22  5320.8  282.34
  5506.7  281.28  5594.8  279.16  5784.6  278.13  5995.4  279.87  6111.3  278.85
  6153.5  279.30  6206.2  281.07  6258.9  280.36  6353.8  281.56  6427.6  281.52
#Mann=9,-1,0
  4543.6   0.035       0  4888.2    0.07       0  4988.3    0.05       0
  5000.0    0.05       0  5004.0    0.05       0  5181.0   0.035       0
  5283.9    0.05       0  5301.4    0.12       0  5506.7    0.05       0
Bank Sta=5000,5004
Exp/Cntr=0.3,0.1

Type RM Length L Ch R = 1,109,0,0,0
BEGIN DESCRIPTION:
XS7725
END DESCRIPTION:
XS GIS Cut Line= 3
      2438165.07     13601204.68      2438925.52     13601423.44
      2439305.72     13601095.32
#Sta/Elev= 30
  4408.8  276.50  4459.9  276.23  4585.6  274.22  4605.1  274.59  4616.8  273.90
  4686.6  273.80  4877.0  271.44  4895.4  271.72  4918.6  270.65  4929.0  271.03
  4934.3  268.39  4939.5  266.85  4947.8  266.52  4948.1  266.02  4951.6  266.02
  4951.8  266.52  4960.2  269.13  4968.0  270.40  4973.2  269.12  4981.0  270.50
  5012.2  270.47  5033.1  271.61  5085.1  272.21  5236.8  271.85  5361.5  274.12
  5453.6  273.75  5489.8  274.17  5588.5  278.61  5637.9  279.72  5702.3  279.03
#Mann=5,-1,0
  4408.8    0.07       0  4686.6     0.1       0  4947.8    0.05       0
  4951.8     0.1       0  5236.8    0.05       0
Bank Sta=4947.8,4951.8
Exp/Cntr=0.3,0.1

Chan Stop Cuts=-1