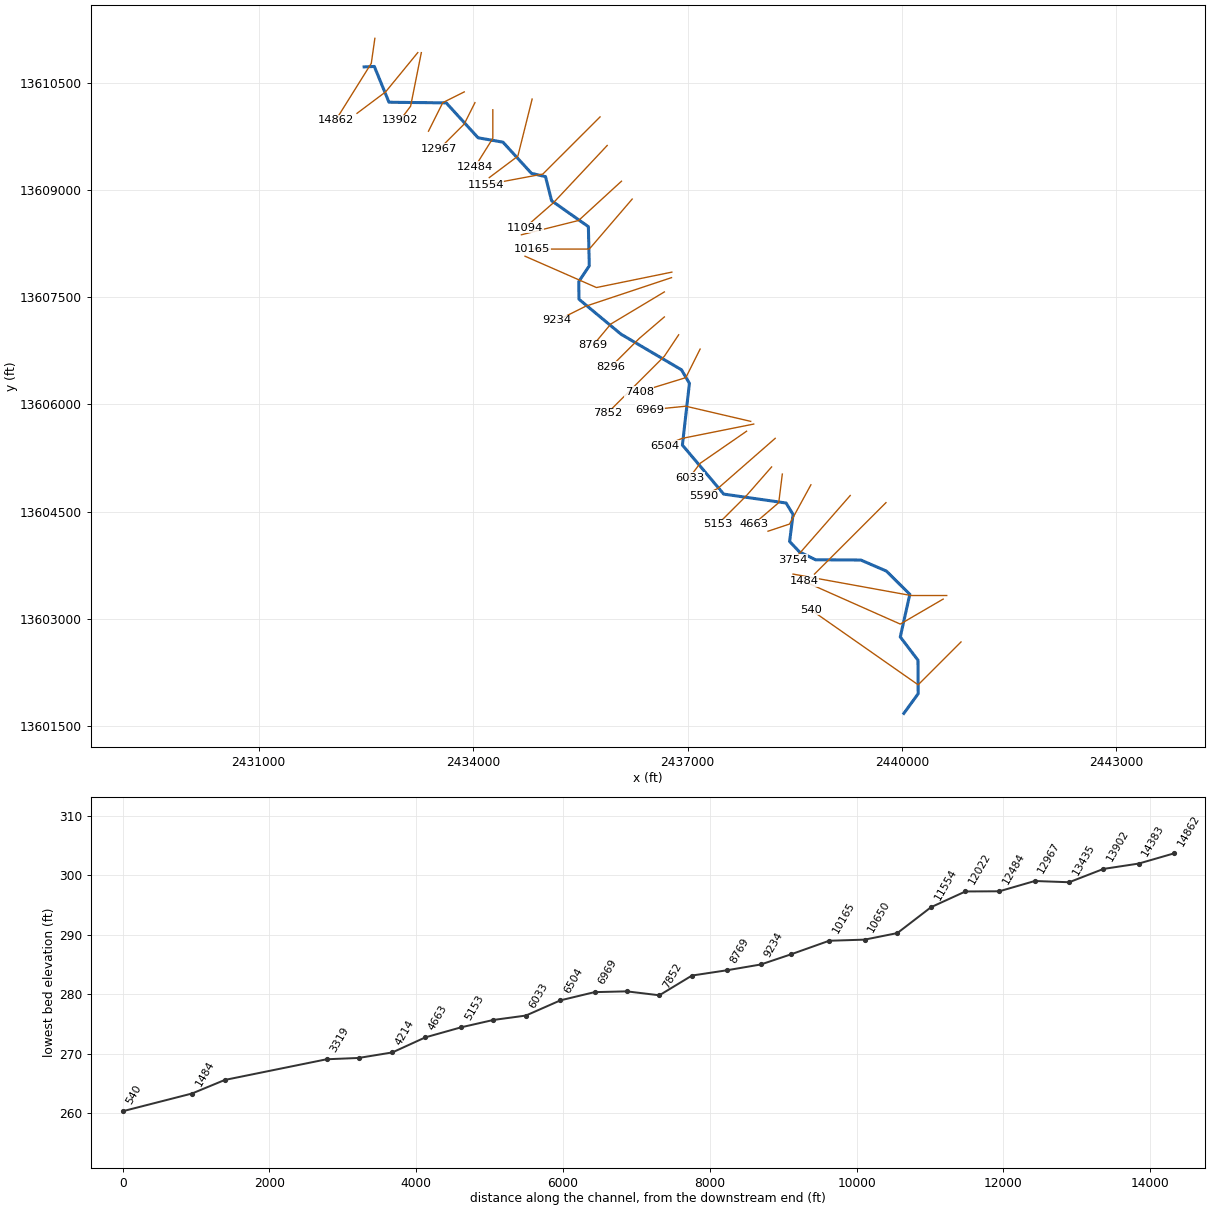
--- Stream0786.prj (project) ---

Proj Title=Stream0786 Base Level Engineering
Current Plan=p01
Default Exp/Contr=0.3,0.1
English Units
Geom File=g01
Flow File=f01
Plan File=p01
Y Axis Title=Elevation
X Axis Title(PF)=Main Channel Distance
X Axis Title(XS)=Station
BEGIN DESCRIPTION:
Stream0786
END DESCRIPTION:
DSS Export Rating Curves= 0
DSS Export Rating Curve Sorted= 0
DSS Export Volume Flow Curves= 0
DXF OffsetX= 0
DXF OffsetY= 0
DXF ScaleX= 1
DXF ScaleY= 10

--- Stream0786.p01 (plan) ---

Plan Title=Multiple Run
Short Identifier=Multiple
Geom File=g01
Flow File=f01
Subcritical Flow
K Sum by GR= 0
Std Step Tol= 0.01
Critical Tol= 0.01
Num of Std Step Trials= 20
Max Error Tol= 0.3
Flow Tol Ratio= 0.001
Split Flow NTrial= 30
Split Flow Tol= 0.02
Split Flow Ratio= 0.02
Log Output Level= 0
Friction Slope Method= 1
Unsteady Friction Slope Method= 2
Unsteady Bridges Friction Slope Method= 1
Parabolic Critical Depth
Global Vel Dist=  1 , 1 , 1
Global Log Level= 0
CheckData=True
Encroach Param= -1, 0, 0, 0
BEGIN DESCRIPTION:
Multiple Run
END DESCRIPTION:

--- Stream0786.f01 (steady flow) ---

Flow Title=Multiple
Number of Profiles=7
Profile Names=10-year,25-year,50-year,1pct_min,100-year,1pct_plu,500-year
River Rch & RM= Stream0786,Reach-1,14862
     601     962    1286     832    1660    3311    2739
River Rch & RM= Stream0786,Reach-1,13902
     890    1453    1966    1286    2565    5119    4330
River Rch & RM= Stream0786,Reach-1,9646
    1485    2498    3449    2298    4586    9150    8043
River Rch & RM= Stream0786,Reach-1,6969
    2021    3427    4758    3185    6354   12679   11242
River Rch & RM= Stream0786,Reach-1,540
    2033    3445    4780    3198    6381   12731   11274
Boundary for River Rch & Prof#=Stream0786,Reach-1,1
Up Type=0
Dn Type=3
Dn Slope=0.005
Boundary for River Rch & Prof#=Stream0786,Reach-1,2
Up Type=0
Dn Type=3
Dn Slope=0.005
Boundary for River Rch & Prof#=Stream0786,Reach-1,3
Up Type=0
Dn Type=3
Dn Slope=0.005
Boundary for River Rch & Prof#=Stream0786,Reach-1,4
Up Type=0
Dn Type=3
Dn Slope=0.005
Boundary for River Rch & Prof#=Stream0786,Reach-1,5
Up Type=0
Dn Type=3
Dn Slope=0.005
Boundary for River Rch & Prof#=Stream0786,Reach-1,6
Up Type=0
Dn Type=3
Dn Slope=0.005
Boundary for River Rch & Prof#=Stream0786,Reach-1,7
Up Type=0
Dn Type=3
Dn Slope=0.005

--- Stream0786.g01 (geometry) ---

Geom Title=Existing Conditions
Program Version=4.10

River Reach=Stream0786      ,Reach-1
Reach XY= 30
        2432475.       13610725.      2432617.32     13610731.56
      2432822.27     13610230.35      2433623.53     13610221.46
      2434068.81     13609732.81      2434416.52     13609671.49
       2434815.2     13609235.48      2435011.77     13609188.73
      2435097.71      13608851.1      2435611.77     13608488.67
       2435624.7     13607940.25      2435477.02     13607719.16
      2435480.45     13607472.53      2436068.83     13606982.86
      2436914.22     13606484.68      2437025.45     13606295.18
      2436927.24     13605430.93      2437504.83      13604744.6
       2438377.7     13604619.64      2438474.92     13604459.61
      2438427.06     13604080.85      2438565.21     13603935.52
      2438790.16     13603825.39      2439423.28     13603821.66
      2439781.06     13603666.86      2440108.86     13603342.08
      2439974.96     13602744.98      2440222.94     13602419.14
       2440225.3     13601949.87        2440025.       13601675.

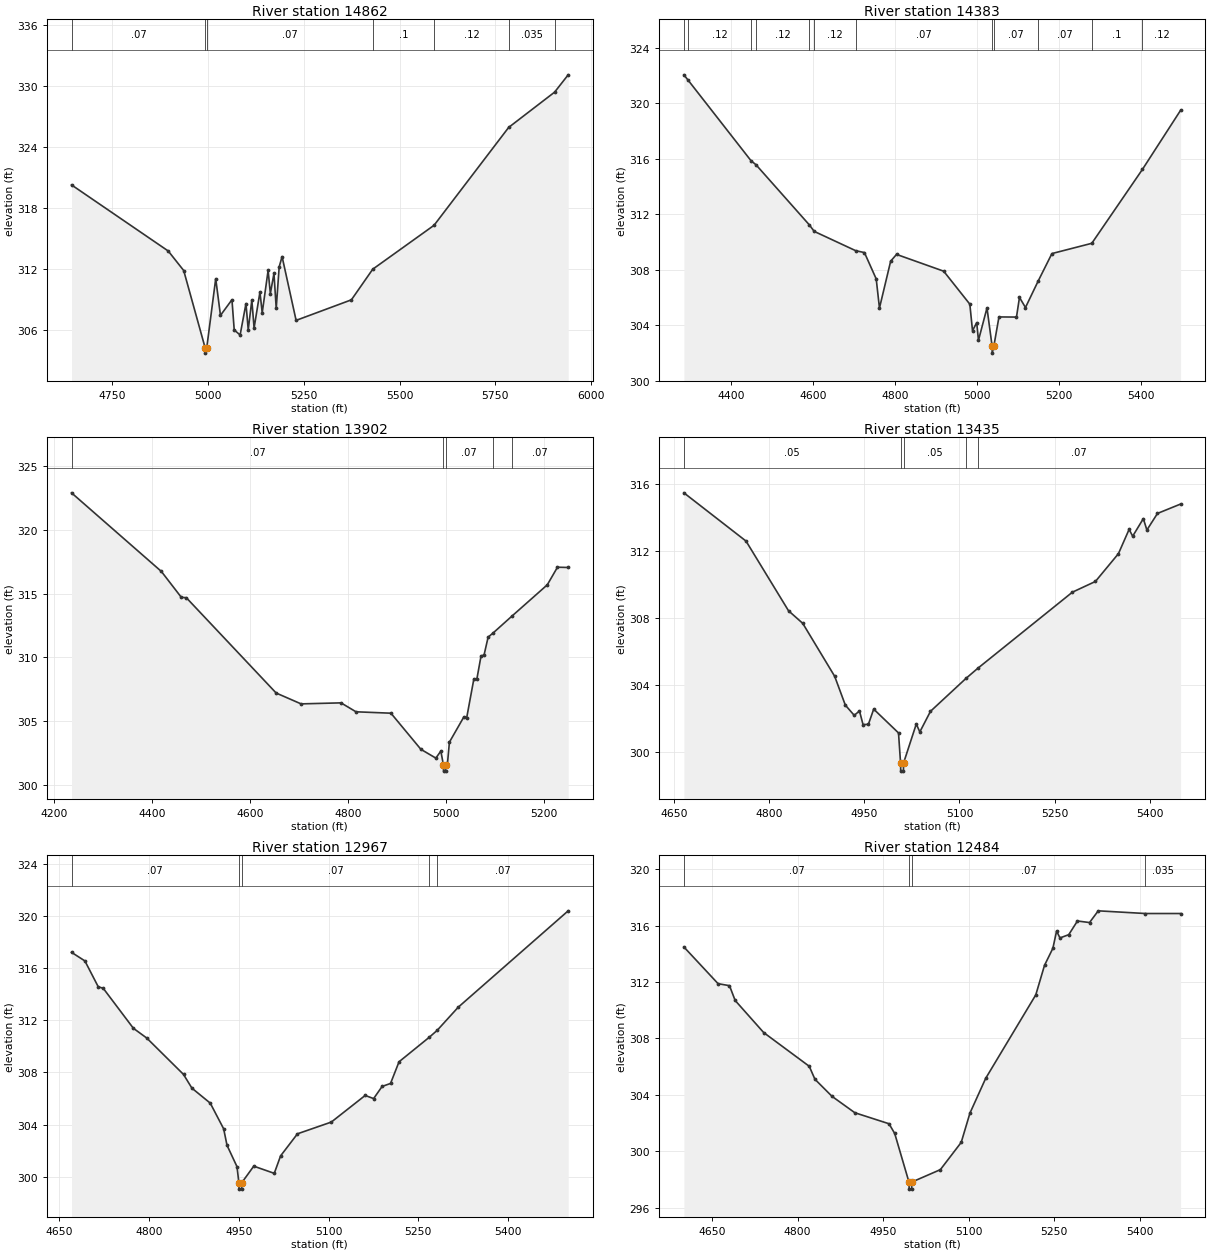
Type RM Length L Ch R = 1 ,14862   ,479,479,479
BEGIN DESCRIPTION:
Stream0786 29.0
END DESCRIPTION:
XS GIS Cut Line= 3
        2432625.     13611125.03        2432575.       13610775.
      2432074.99     13609974.99
#Sta/Elev= 30
  4643.1  320.24  4895.7  313.74  4936.1  311.82  4992.2   304.2  4992.4   303.7
  4996.2   304.2  5019.7  311.02  5032.1  307.41  5062.1  308.95    5068  305.98
  5083.4  305.48  5098.7  308.57  5104.6     306    5114  308.91  5119.9  306.17
  5135.2  309.71  5141.1  307.66  5156.5  311.83  5162.4  309.56  5171.8  311.54
  5177.7   308.1  5185.4  312.18    5193  313.19  5229.6  306.92    5374  308.94
  5429.7  311.95  5589.9  316.27  5784.7  325.89  5904.7  329.36  5940.1  331.06
#Mann= 7 ,-1 , 0
  4643.1     .07       0  4992.2     .05       0  4996.2     .07       0
  5429.7      .1       0  5589.9     .12       0  5784.7    .035       0
  5904.7     .05       0
Bank Sta=4992.2,4996.2
XS Rating Curve= 0 ,0
Exp/Cntr=0.3,0.1

Type RM Length L Ch R = 1 ,14383   ,481,481,481
BEGIN DESCRIPTION:
Stream0786 28.0
END DESCRIPTION:
XS GIS Cut Line= 3
      2433225.03     13610925.04        2432775.       13610375.
      2432374.99     13610074.99
#Sta/Elev= 30
  4285.2  322.06  4295.6  321.67    4449  315.86  4460.8  315.58  4591.2  311.23
  4602.8  310.77  4703.8  309.38  4725.3  309.24    4754  307.34  4761.9  305.24
  4789.2  308.62  4803.5  309.11  4918.4   307.9  4982.2  305.52  4988.7  303.61
    4999  304.19  5003.2  302.91    5024  305.25  5036.5  302.49  5036.7  301.99
  5040.7  302.49  5053.2   304.6  5095.9  304.59  5103.2  306.01  5117.8  305.28
  5148.8  307.19  5182.3  309.17  5279.5  309.91  5402.9  315.24  5495.9   319.5
#Mann= 12 ,-1 , 0
  4285.2     .07       0  4295.6     .12       0    4449     .07       0
  4460.8     .12       0  4591.2     .07       0  4602.8     .12       0
  4703.8     .07       0  5036.5     .05       0  5040.7     .07       0
  5148.8     .07       0  5279.5      .1       0  5402.9     .12       0
Bank Sta=5036.5,5040.7
XS Rating Curve= 0 ,0
Exp/Cntr=0.3,0.1

Type RM Length L Ch R = 1 ,13902   ,467,467,467
BEGIN DESCRIPTION:
Stream0786 27.0
END DESCRIPTION:
XS GIS Cut Line= 3
      2433275.01     13610925.04        2433125.       13610175.
      2432974.99     13609974.99
#Sta/Elev= 30
    4235   322.9  4418.6  316.74  4459.4  314.71  4469.6  314.68  4653.2  307.21
  4704.1  306.36  4785.7  306.44  4816.3  305.74  4887.7  305.63  4948.9   302.8
  4979.5  302.11  4989.7  302.66  4994.9  301.59  4995.3  301.09  4999.4  301.09
  4999.7  301.59    5003  301.59  5007.2  303.36  5036.3  305.31  5042.6  305.29
  5057.2  308.32  5063.4  308.33  5071.8  310.11    5078  310.19  5086.3  311.59
    5096   311.9    5135  313.24  5207.2  315.69    5228  317.07  5249.9  317.05
#Mann= 5 ,-1 , 0
    4235     .07       0  4994.9     .05       0  4999.7     .07       0
    5096    .035       0    5135     .07       0
Bank Sta=4994.9,4999.7
XS Rating Curve= 0 ,0
Exp/Cntr=0.3,0.1

Type RM Length L Ch R = 1 ,13435   ,468,468,468
BEGIN DESCRIPTION:
Stream0786 26.0
END DESCRIPTION:
XS GIS Cut Line= 3
      2433875.03     13610375.02        2433575.       13610225.
      2433374.98     13609824.96
#Sta/Elev= 30
  4665.7  315.46  4763.6  312.58  4830.6  308.42    4853  307.67  4903.3  304.51
  4920.1  302.79  4934.1  302.18  4942.4  302.44    4948  301.63  4956.4  301.64
  4964.8  302.55  5003.9  301.13  5007.1  299.35  5007.4  298.85  5011.6  298.85
    5012  299.35  5031.9  301.66  5037.5  301.19  5054.3  302.42  5110.4  304.39
  5128.6  304.98  5277.9  309.53  5314.2  310.17  5350.5  311.83  5367.3  313.28
  5372.9  312.87  5389.7  313.92  5395.3  313.24    5412  314.23  5448.4  314.79
#Mann= 5 ,-1 , 0
  4665.7     .05       0  5007.1     .05       0    5012     .05       0
  5110.4    .035       0  5128.6     .07       0
Bank Sta=5007.1,5012
XS Rating Curve= 0 ,0
Exp/Cntr=0.3,0.1

Type RM Length L Ch R = 1 ,12967   ,483,483,483
BEGIN DESCRIPTION:
Stream0786 25.0
END DESCRIPTION:
XS GIS Cut Line= 3
      2434025.01     13610225.01        2433875.       13609925.
        2433525.       13609575.
#Sta/Elev= 30
  4670.1  317.21  4692.5  316.55  4714.8  314.57  4723.2  314.45  4773.5  311.39
  4795.9  310.64  4857.4  307.85  4871.4   306.8  4902.1  305.65  4924.5  303.68
  4930.1  302.42  4946.8  300.78  4949.9  299.56  4950.3  299.06  4954.5  299.06
  4954.9  299.56  4974.8  300.82  5009.1  300.27  5019.7  301.61  5047.9   303.3
  5104.5   304.2  5161.1  306.24  5175.2     306  5189.4  306.93  5203.5  307.16
  5217.7  308.82    5268  310.69  5281.3  311.22  5316.6     313  5500.5  320.39
#Mann= 5 ,-1 , 0
  4670.1     .07       0  4949.9     .05       0  4954.9     .07       0
    5268     .05       0  5281.3     .07       0
Bank Sta=4949.9,4954.9
XS Rating Curve= 0 ,0
Exp/Cntr=0.3,0.1

Type RM Length L Ch R = 1 ,12484   ,462,462,462
BEGIN DESCRIPTION:
Stream0786 24.0
END DESCRIPTION:
XS GIS Cut Line= 3
        2434275.     13610125.01        2434275.       13609725.
        2434025.       13609325.
#Sta/Elev= 30
  4600.4  314.48  4660.4  311.88  4680.4  311.74  4690.4  310.69  4740.4  308.42
  4820.4  306.03  4830.4  305.11  4860.4   303.9  4900.4  302.74  4960.4  301.96
  4970.4  301.27  4995.4  297.83  4995.8  297.33  5000.1  297.33  5000.4  297.83
  5050.5  298.71  5087.1  300.64  5102.4  302.71  5130.1  305.18    5218  311.09
  5233.3  313.18    5248  314.39  5254.5  315.61  5260.4  315.12  5275.8  315.35
  5291.1  316.32  5312.3  316.21  5327.6  317.04  5410.2  316.85  5472.1  316.85
#Mann= 4 ,-1 , 0
  4600.4     .07       0  4995.4     .05       0  5000.4     .07       0
  5410.2    .035       0
Bank Sta=4995.4,5000.4
XS Rating Curve= 0 ,0
Exp/Cntr=0.3,0.1

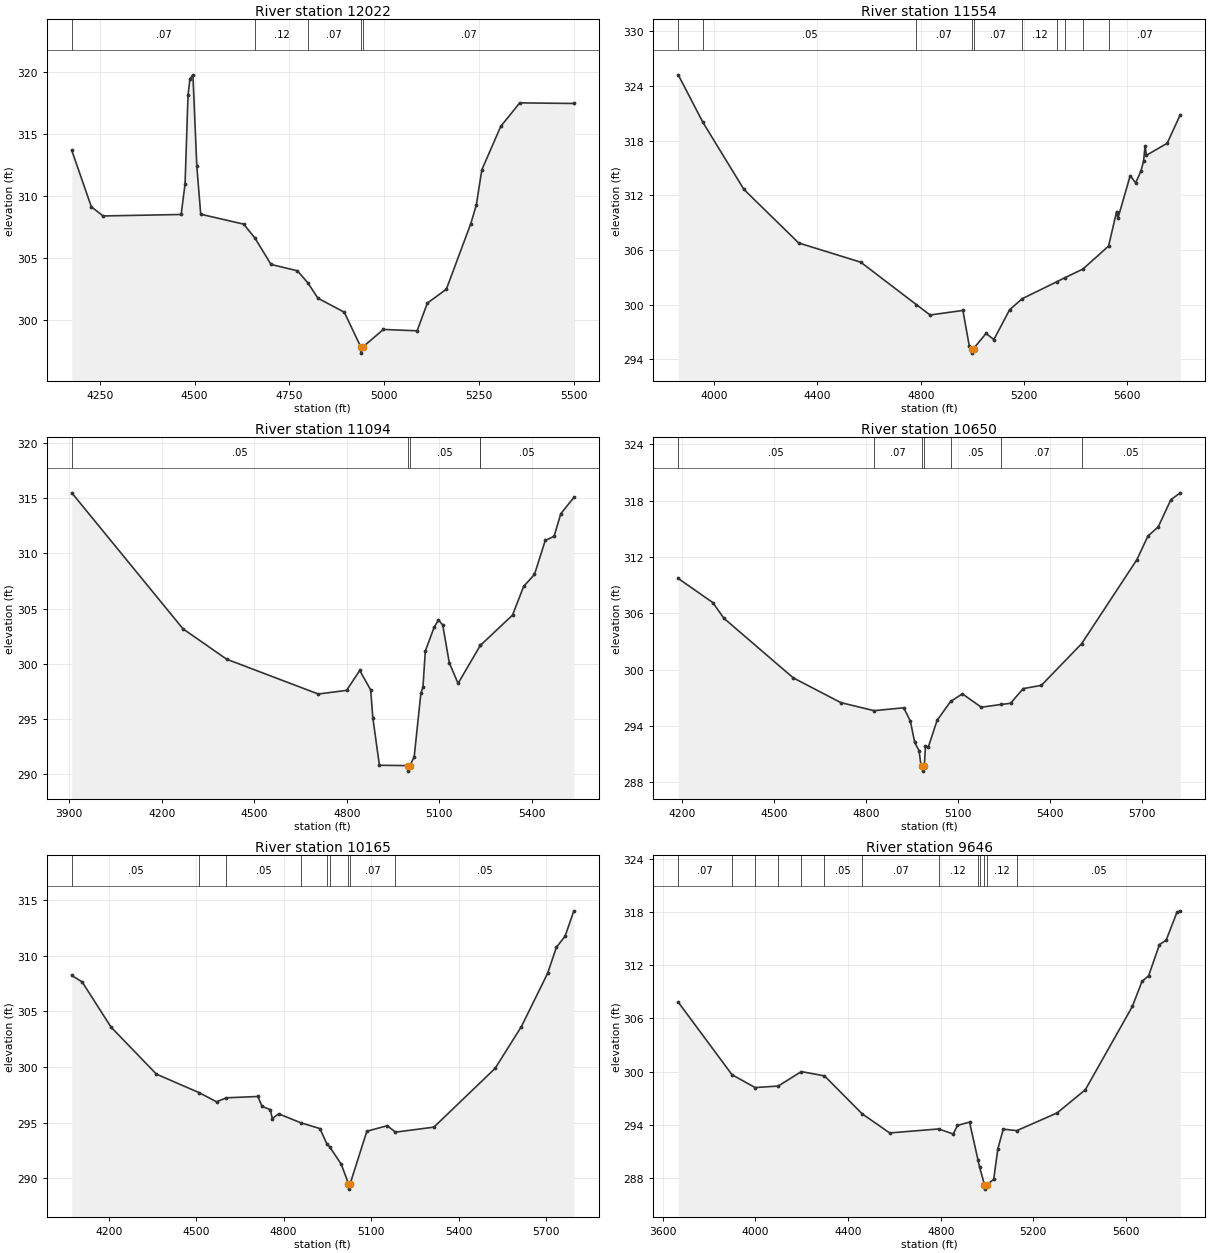
Type RM Length L Ch R = 1 ,12022   ,468,468,468
BEGIN DESCRIPTION:
Stream0786 23.0
END DESCRIPTION:
XS GIS Cut Line= 3
        2434825.     13610275.02        2434625.       13609475.
      2434225.03     13609175.02
#Sta/Elev= 30
  4175.9  313.65  4227.5   309.1  4258.4  308.36  4464.5  308.48  4474.8  310.96
  4482.6   318.1  4487.7  319.41  4495.5  319.74  4505.8  312.37  4516.1   308.5
  4629.5   307.7  4659.4  306.57  4701.6  304.45  4771.2  303.94  4798.7  302.97
  4825.3  301.73  4894.9   300.6  4938.4   297.8  4938.9   297.3  4944.1   297.8
    4998  299.21    5087   299.1  5114.1  301.34  5164.1  302.45  5228.7  307.75
  5243.2  309.25  5257.8  312.09  5307.8  315.59  5357.8  317.48  5500.5  317.43
#Mann= 5 ,-1 , 0
  4175.9     .07       0  4659.4     .12       0  4798.7     .07       0
  4938.4     .05       0  4944.1     .07       0
Bank Sta=4938.4,4944.1
XS Rating Curve= 0 ,0
Exp/Cntr=0.3,0.1

Type RM Length L Ch R = 1 ,11554   ,460,460,460
BEGIN DESCRIPTION:
Stream0786 22.0
END DESCRIPTION:
XS GIS Cut Line= 3
      2435775.03     13610025.03        2434975.       13609225.
      2434174.96     13609074.99
#Sta/Elev= 30
  3860.5  325.23  3956.1  320.01  4115.1  312.64  4327.2  306.76  4567.7  304.65
  4783.2  299.99  4836.4  298.85  4963.6  299.35  4988.4  295.41  4999.2  295.16
  4999.7  294.66    5005  295.16    5053  296.82  5083.5  296.15  5144.5  299.43
  5192.8  300.63  5328.8  302.52  5359.6  302.96  5428.3  303.89  5527.9  306.42
  5559.1  310.21  5564.2  309.48  5611.7  314.15  5632.9  313.36  5653.2  314.66
  5663.4  315.72  5669.4  317.44  5674.4  316.39    5755  317.71  5805.9  320.86
#Mann= 10 ,-1 , 0
  3860.5     .07       0  3956.1     .05       0  4783.2     .07       0
  4999.2     .05       0    5005     .07       0  5192.8     .12       0
  5328.8    .035       0  5359.6     .07       0  5428.3    .035       0
  5527.9     .07       0
Bank Sta=4999.2,5005
XS Rating Curve= 0 ,0
Exp/Cntr=0.3,0.1

Type RM Length L Ch R = 1 ,11094   ,444,444,444
BEGIN DESCRIPTION:
Stream0786 21.0
END DESCRIPTION:
XS GIS Cut Line= 3
      2435874.98     13609624.98        2435125.       13608825.
      2434724.97     13608474.98
#Sta/Elev= 30
    3908  315.49  4268.7  303.18  4410.3  300.43  4707.3  297.28  4799.2  297.61
  4841.7  299.41  4877.3  297.65  4884.2  295.14  4905.6  290.83  4998.2   290.8
  4998.7   290.3  5004.1   290.8  5018.3  291.57  5040.1  297.36  5046.8  297.89
  5054.4  301.16  5082.9  303.31  5097.1  303.98  5110.9  303.53  5132.2  300.11
  5160.7  298.24    5233  301.69  5233.3  301.69  5337.2  304.42  5373.3  307.02
  5408.4   308.1  5443.5  311.19    5472  311.55  5493.8   313.6  5536.1  315.07
#Mann= 5 ,-1 , 0
    3908     .05       0  4998.2     .05       0  5004.1     .05       0
    5233     .07       0  5233.3     .05       0
Bank Sta=4998.2,5004.1
XS Rating Curve= 0 ,0
Exp/Cntr=0.3,0.1

Type RM Length L Ch R = 1 ,10650   ,485,485,485
BEGIN DESCRIPTION:
Stream0786 20.0
END DESCRIPTION:
XS GIS Cut Line= 3
      2436074.96     13609124.97        2435475.       13608575.
      2434675.01       13608375.
#Sta/Elev= 30
  4186.1  309.73  4299.2  307.15    4335  305.49  4561.3  299.14  4716.7   296.5
  4825.3  295.64    4922  295.95  4943.6  294.53  4957.8  292.26  4971.9  291.39
  4978.7  289.72  4983.2   289.7  4983.7   289.2  4989.1   289.7  4992.9  291.83
  5002.6  291.81  5030.9  294.61  5075.1  296.63  5113.4  297.43  5175.2  296.01
  5239.5   296.3  5270.6  296.43  5311.8  297.99  5371.1  298.34  5502.6  302.78
  5682.9  311.73    5719  314.25  5752.5  315.22  5793.7  318.12  5824.6  318.85
#Mann= 7 ,-1 , 0
  4186.1     .05       0  4825.3     .07       0  4983.2     .05       0
  4989.1     .07       0  5075.1     .05       0  5239.5     .07       0
  5502.6     .05       0
Bank Sta=4983.2,4989.1
XS Rating Curve= 0 ,0
Exp/Cntr=0.3,0.1

Type RM Length L Ch R = 1 ,10165   ,519,519,519
BEGIN DESCRIPTION:
Stream0786 19.0
END DESCRIPTION:
XS GIS Cut Line= 3
      2436225.03     13608875.04        2435625.       13608175.
        2434825.       13608175.
#Sta/Elev= 30
  4073.4  308.24  4109.1  307.66  4207.9   303.6  4363.8  299.36  4510.5  297.69
  4570.1  296.87  4603.6  297.23  4711.7  297.35    4726  296.46  4754.5  296.16
  4761.1  295.36    4783  295.79  4859.2  294.98  4924.6  294.46  4949.3  293.03
  4957.4  292.84  4997.9  291.24  5022.4  289.51  5022.9  289.01  5028.4  289.51
  5085.4  294.22  5155.4  294.72  5183.7  294.14  5315.4  294.59  5525.4  299.88
  5615.4  303.64  5705.4  308.43  5735.4  310.77  5765.4  311.78  5795.4  314.06
#Mann= 9 ,-1 , 0
  4073.4     .05       0  4510.5     .07       0  4603.6     .05       0
  4859.2     .07       0  4949.3     .05       0  4957.4     .07       0
  5022.4     .05       0  5028.4     .07       0  5183.7     .05       0
Bank Sta=5022.4,5028.4
XS Rating Curve= 0 ,0
Exp/Cntr=0.3,0.1

Type RM Length L Ch R = 1 ,9646    ,412,412,412
BEGIN DESCRIPTION:
Stream0786 18.0
END DESCRIPTION:
XS GIS Cut Line= 3
      2436779.41     13607852.08      2435725.07     13607636.31
      2434724.96     13608075.02
#Sta/Elev= 30
  3666.5  307.83  3898.7  299.64  3998.5  298.19  4098.3  298.36  4198.1  299.99
    4298  299.51  4460.7  295.23  4579.6  293.07  4791.1  293.52  4854.4  292.95
  4872.3  293.92  4924.5  294.29  4961.3     290  4967.9  289.22  4989.1  287.23
  4989.6  286.73  4998.7  287.23  5028.9  287.83  5046.8  291.28  5070.2   293.5
  5128.4  293.33  5302.3  295.32  5424.6  297.94  5627.9  307.35  5669.2  310.16
    5698  310.81  5744.8  314.33  5773.6  314.81  5820.3  317.97  5834.8  318.13
#Mann= 13 ,-1 , 0
  3666.5     .07       0  3898.7     .12       0  3998.5     .07       0
  4098.3     .12       0  4198.1     .07       0    4298     .05       0
  4460.7     .07       0  4791.1     .12       0  4961.3     .07       0
  4967.9     .12       0  4989.1     .05       0  4998.7     .12       0
  5128.4     .05       0
Bank Sta=4989.1,4998.7
XS Rating Curve= 0 ,0
Exp/Cntr=0.3,0.1

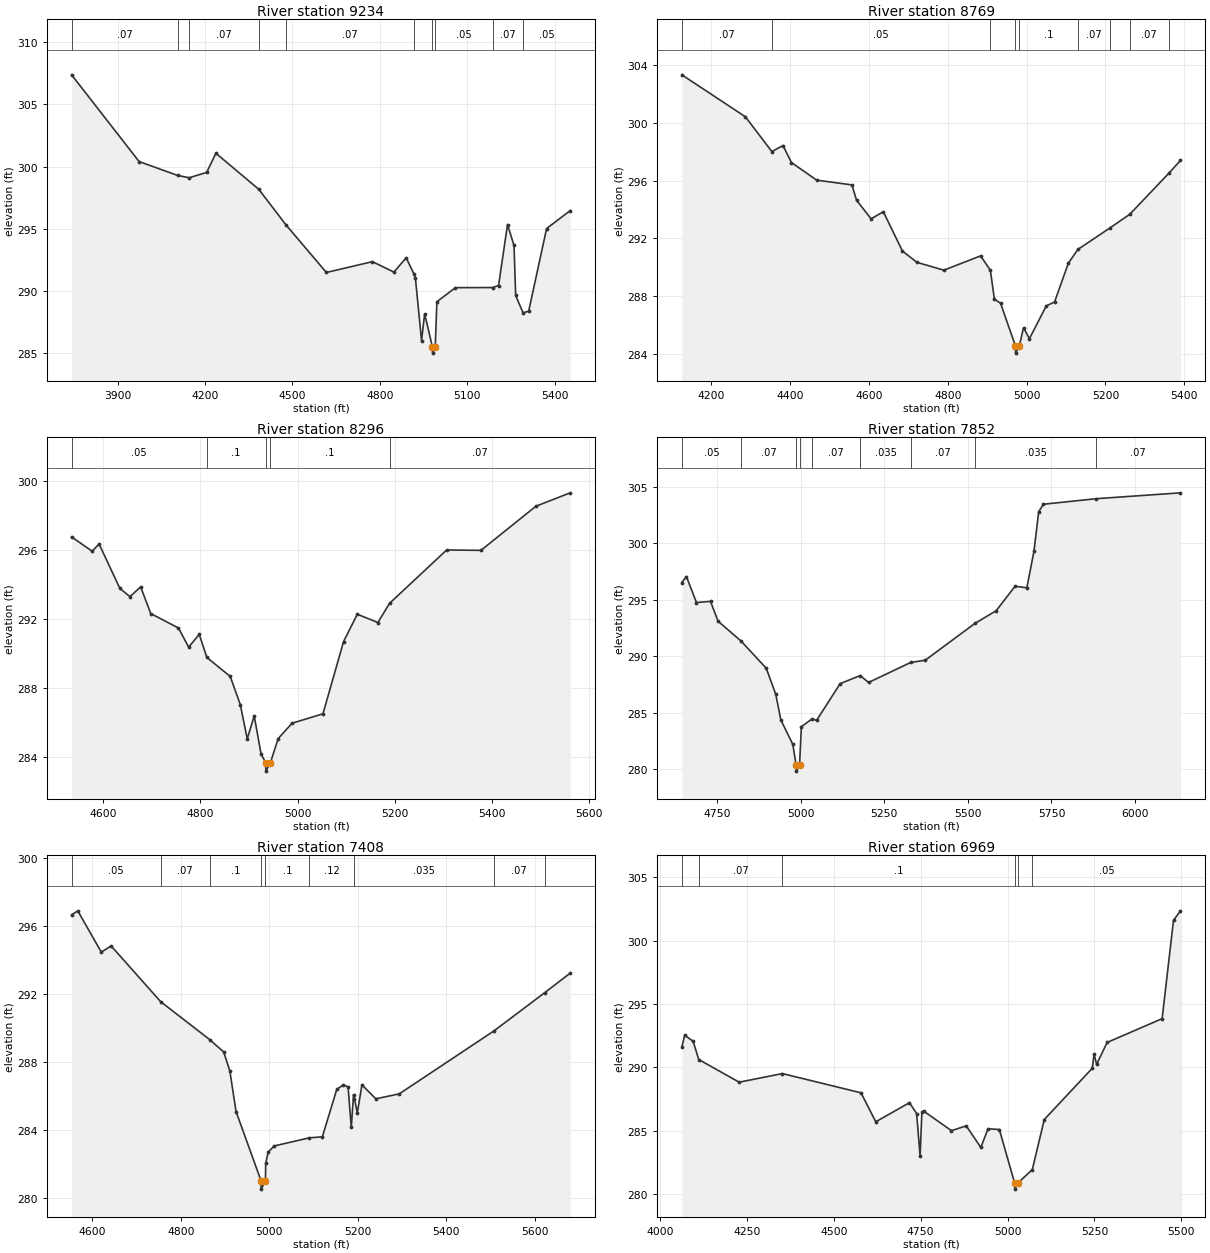
Type RM Length L Ch R = 1 ,9234    ,465,465,465
BEGIN DESCRIPTION:
Stream0786 17.0
END DESCRIPTION:
XS GIS Cut Line= 3
      2436775.04     13607775.01        2435575.       13607375.
      2435174.97     13607174.99
#Sta/Elev= 30
  3741.6  307.38  3973.5  300.41  4105.4   299.3  4145.2  299.11  4205.4  299.54
  4237.1  301.08  4384.5  298.18  4477.5  295.33  4616.5   291.5  4774.7  292.37
  4848.4  291.53  4890.6  292.68  4917.9  291.34  4922.2  291.06  4943.3  286.01
  4953.9  288.18  4980.6  285.52  4981.1  285.02  4990.3  285.52    4996  289.15
  5059.7  290.28  5187.8  290.29  5207.8  290.45  5238.5  295.35  5260.9  293.67
  5266.5  289.66  5291.8  288.26  5311.2  288.39  5372.7  295.03  5453.8  296.47
#Mann= 10 ,-1 , 0
  3741.6     .07       0  4105.4     .12       0  4145.2     .07       0
  4384.5     .05       0  4477.5     .07       0  4917.9     .05       0
  4980.6     .05       0  4990.3     .05       0  5187.8     .07       0
  5291.8     .05       0
Bank Sta=4980.6,4990.3
XS Rating Curve= 0 ,0
Exp/Cntr=0.3,0.1

Type RM Length L Ch R = 1 ,8769    ,473,473,473
BEGIN DESCRIPTION:
Stream0786 16.0
END DESCRIPTION:
XS GIS Cut Line= 3
      2436675.02     13607575.01        2435925.       13607125.
      2435674.99     13606824.98
#Sta/Elev= 30
  4125.3  303.33  4286.6  300.42  4353.6  298.01  4381.9  298.43  4403.3  297.25
  4467.4  296.03  4556.8   295.7  4568.5  294.64  4605.4  293.35  4636.5  293.84
  4685.1  291.11    4722  290.33  4790.1  289.79  4883.3  290.78  4908.1  289.78
  4918.3  287.78  4933.9   287.5  4971.7  284.54  4972.2  284.04  4981.6  284.54
  4992.2   285.8  5007.1  285.04  5050.1  287.32  5070.9  287.58  5106.1  290.28
  5130.3  291.23  5212.2  292.73  5261.7  293.66  5360.7   296.5  5390.5   297.4
#Mann= 9 ,-1 , 0
  4125.3     .07       0  4353.6     .05       0  4908.1      .1       0
  4971.7     .05       0  4981.6      .1       0  5130.3     .07       0
  5212.2     .05       0  5261.7     .07       0  5360.7     .05       0
Bank Sta=4971.7,4981.6
XS Rating Curve= 0 ,0
Exp/Cntr=0.3,0.1

Type RM Length L Ch R = 1 ,8296    ,444,444,444
BEGIN DESCRIPTION:
Stream0786 15.0
END DESCRIPTION:
XS GIS Cut Line= 3
      2436675.04     13607225.03        2436325.       13606925.
      2435925.01     13606525.01
#Sta/Elev= 30
  4534.6  296.76  4576.9  295.93  4591.2  296.35    4634  293.77  4654.8  293.29
  4676.8  293.86  4697.6  292.31  4754.7  291.47  4775.6  290.36  4797.5   291.1
  4813.1  289.76  4861.2  288.66    4882  287.02  4896.3  285.03  4910.6  286.37
  4924.8  284.15  4934.1  283.66  4934.6  283.16  4944.1  283.66    4960  285.05
  4988.5  285.94  5052.2  286.49  5094.6  290.68  5122.9  292.27  5165.3  291.79
  5189.2   292.9  5306.8     296  5377.5  295.98  5490.6  298.54  5561.3  299.32
#Mann= 5 ,-1 , 0
  4534.6     .05       0  4813.1      .1       0  4934.1     .05       0
  4944.1      .1       0  5189.2     .07       0
Bank Sta=4934.1,4944.1
XS Rating Curve= 0 ,0
Exp/Cntr=0.3,0.1

Type RM Length L Ch R = 1 ,7852    ,444,444,444
BEGIN DESCRIPTION:
Stream0786 14.0
END DESCRIPTION:
XS GIS Cut Line= 3
      2436875.02     13606975.03        2436675.       13606675.
      2435874.97     13605874.97
#Sta/Elev= 30
  4644.1  296.52  4657.7  297.05  4687.7  294.75  4729.8  294.85  4752.3   293.1
  4821.3  291.34  4896.5  288.94  4925.1  286.63  4940.1  284.38  4976.1   282.2
  4986.1  280.34  4986.6  279.84  4996.2  280.34  5001.7  283.77  5034.2  284.47
  5047.1  284.32  5117.8  287.58  5177.7  288.29  5202.7  287.68  5328.9  289.45
  5372.4  289.65  5521.3  292.91  5584.5  294.02  5641.1  296.19  5676.4  296.05
  5697.7  299.29  5711.8  302.78  5725.9  303.44  5883.7  303.93  6136.1  304.45
#Mann= 9 ,-1 , 0
  4644.1     .05       0  4821.3     .07       0  4986.1     .05       0
  4996.2     .07       0  5034.2     .07       0  5177.7    .035       0
  5328.9     .07       0  5521.3    .035       0  5883.7     .07       0
Bank Sta=4986.1,4996.2
XS Rating Curve= 0 ,0
Exp/Cntr=0.3,0.1

Type RM Length L Ch R = 1 ,7408    ,439,439,439
BEGIN DESCRIPTION:
Stream0786 13.0
END DESCRIPTION:
XS GIS Cut Line= 3
      2437175.01     13606775.02        2436975.       13606375.
        2436325.       13606175.
#Sta/Elev= 30
  4552.8  296.65  4566.8  296.89  4619.9  294.46  4642.3  294.82  4754.2  291.54
  4865.3   289.3  4896.6  288.58  4910.6  287.46  4924.6  285.07    4981     281
  4981.5   280.5  4991.1     281  4991.6  282.01  4997.2  282.67  5010.5  283.04
  5090.2  283.52  5119.7  283.58  5152.4  286.38  5167.4  286.64  5177.9  286.52
  5185.1  284.13  5190.3  286.07  5192.2  285.83  5198.8     285  5209.3  286.64
  5240.7  285.82  5293.6  286.11  5507.3  289.81  5622.5  292.07  5680.1  293.22
#Mann= 9 ,-1 , 0
  4552.8     .05       0  4754.2     .07       0  4865.3      .1       0
    4981     .05       0  4991.1      .1       0  5090.2     .12       0
  5192.2    .035       0  5507.3     .07       0  5622.5    .035       0
Bank Sta=4981,4991.1
XS Rating Curve= 0 ,0
Exp/Cntr=0.3,0.1

Type RM Length L Ch R = 1 ,6969    ,465,465,465
BEGIN DESCRIPTION:
Stream0786 12.0
END DESCRIPTION:
XS GIS Cut Line= 3
      2437882.78     13605763.01        2436975.       13605975.
        2436475.       13605925.
#Sta/Elev= 30
  4062.9  291.58  4070.9  292.53  4095.1  292.06  4111.5  290.61  4227.8  288.82
  4352.1   289.5  4578.3  287.98  4620.8  285.69  4717.8   287.2  4738.4  286.34
  4748.4  282.97  4753.5  286.44  4758.9  286.53  4838.6  284.99  4881.1  285.37
  4923.2  283.66  4943.8  285.14  4976.4  285.08  5020.2  280.87  5020.7  280.37
  5030.4  280.87  5071.2  281.91  5105.7  285.87  5243.8  289.92  5248.9  291.02
  5256.4  290.24  5286.5  291.96  5444.8  293.84  5477.5  301.61  5497.6  302.36
#Mann= 6 ,-1 , 0
  4062.9     .05       0  4111.5     .07       0  4352.1      .1       0
  5020.2     .05       0  5030.4      .1       0  5071.2     .05       0
Bank Sta=5020.2,5030.4
XS Rating Curve= 0 ,0
Exp/Cntr=0.3,0.1

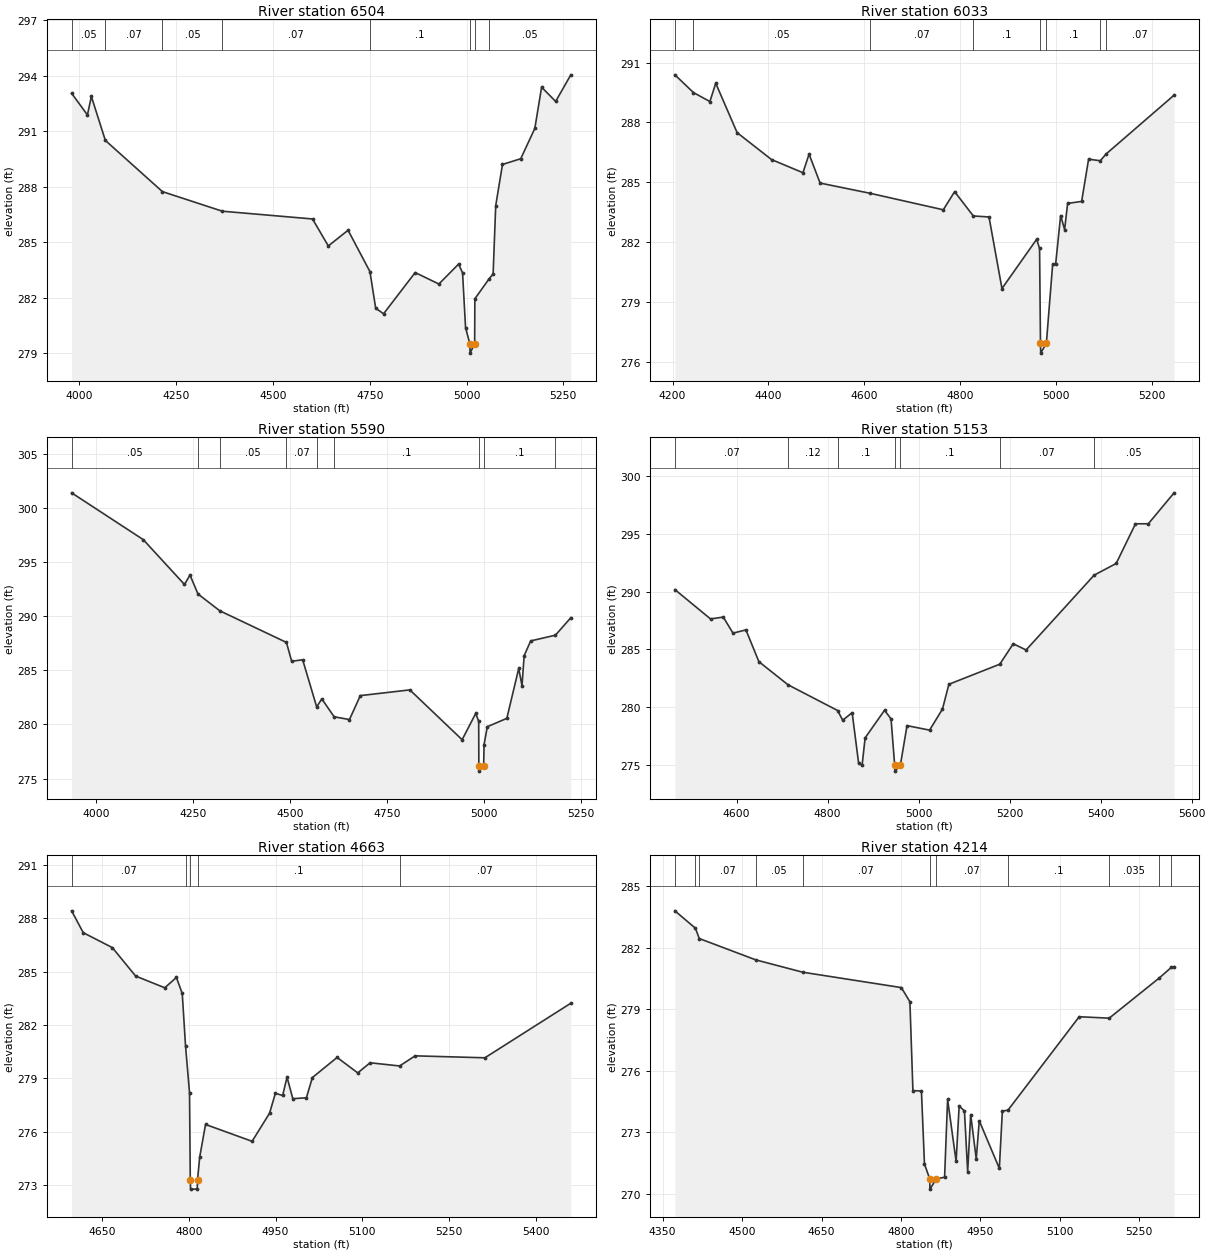
Type RM Length L Ch R = 1 ,6504    ,471,471,471
BEGIN DESCRIPTION:
Stream0786 11.0
END DESCRIPTION:
XS GIS Cut Line= 3
        2437925.       13605725.        2436925.       13605525.
      2436674.96     13605424.99
#Sta/Elev= 30
  3980.1  293.05  4020.9  291.88  4031.1  292.88  4067.2   290.5  4214.6  287.73
  4369.2  286.67  4602.2  286.25    4643  284.79    4694  285.64  4750.5   283.4
  4765.3  281.42  4785.7  281.12  4867.3  283.35  4928.5  282.73  4979.5  283.81
  4989.7  283.33  4997.4  280.37  5008.6  279.49  5009.1  278.99  5020.9  279.49
  5021.4  281.93  5057.5  282.99  5068.6  283.28  5075.3  286.97  5092.8   289.2
  5139.9  289.51  5176.3  291.15  5193.8  293.38  5230.1  292.61  5269.2  294.05
#Mann= 8 ,-1 , 0
  3980.1     .05       0  4067.2     .07       0  4214.6     .05       0
  4369.2     .07       0  4750.5      .1       0  5008.6     .05       0
  5020.9      .1       0  5057.5     .05       0
Bank Sta=5008.6,5020.9
XS Rating Curve= 0 ,0
Exp/Cntr=0.3,0.1

Type RM Length L Ch R = 1 ,6033    ,443,443,443
BEGIN DESCRIPTION:
Stream0786 10.0
END DESCRIPTION:
XS GIS Cut Line= 3
        2437825.       13605625.        2437175.       13605175.
      2437024.98     13604974.98
#Sta/Elev= 30
  4204.9  290.39  4243.6   289.5  4277.9  289.05    4290  289.97  4334.6  287.49
  4406.3  286.14  4471.8  285.48  4484.6  286.41  4507.6  284.96  4611.4  284.45
  4764.4  283.62    4788  284.53    4827  283.31  4859.7  283.26  4886.7  279.67
    4959  282.14  4965.1  281.68    4967  276.93  4967.5  276.43  4979.3  276.93
  4992.4  280.89  4998.6  280.89    5009  283.33  5017.3  282.63  5023.6  283.94
  5052.8  284.04  5067.3  286.16  5091.6  286.08  5104.3  286.43  5245.5  289.37
#Mann= 8 ,-1 , 0
  4204.9     .07       0  4243.6     .05       0  4611.4     .07       0
    4827      .1       0    4967     .05       0  4979.3      .1       0
  5091.6     .05       0  5104.3     .07       0
Bank Sta=4967,4979.3
XS Rating Curve= 0 ,0
Exp/Cntr=0.3,0.1

Type RM Length L Ch R = 1 ,5590    ,437,437,437
BEGIN DESCRIPTION:
Stream0786 9.0
END DESCRIPTION:
XS GIS Cut Line= 3
      2438224.96     13605524.97        2437425.       13604825.
      2437224.98     13604724.99
#Sta/Elev= 30
  3936.8  301.38  4121.4  297.06  4227.7  292.92  4241.9  293.79  4262.5  292.04
  4318.7  290.49  4490.5  287.57  4503.9  285.83  4532.3  285.97  4568.4  281.62
  4581.7  282.36  4613.3  280.71  4652.9  280.45  4680.9  282.66  4808.5  283.19
  4943.3  278.59  4978.4  281.02    4986  280.29  4986.4  276.19  4986.9  275.69
  4998.8  276.19  4999.8  278.14  5008.2  279.79  5058.5  280.56  5089.2  285.17
  5097.6  283.58  5103.2  286.35    5120  287.71  5183.8  288.24  5223.4  289.85
#Mann= 9 ,-1 , 0
  3936.8     .05       0  4262.5     .07       0  4318.7     .05       0
  4490.5     .07       0  4568.4     .12       0  4613.3      .1       0
  4986.4     .05       0  4998.8      .1       0  5183.8     .07       0
Bank Sta=4986.4,4998.8
XS Rating Curve= 0 ,0
Exp/Cntr=0.3,0.1

Type RM Length L Ch R = 1 ,5153    ,490,490,490
BEGIN DESCRIPTION:
Stream0786 8.0
END DESCRIPTION:
XS GIS Cut Line= 3
      2438175.01     13605125.01        2437825.       13604725.
      2437425.01     13604325.01
#Sta/Elev= 30
  4464.2  290.18  4542.5  287.64  4570.5   287.8  4591.9  286.41  4620.3  286.69
  4648.8  283.94  4712.7  281.94  4821.8  279.71    4833  278.87  4853.8  279.52
  4868.1  275.13  4875.7  274.98  4882.3  277.34    4925  279.73  4939.3  278.98
  4947.3  274.96  4947.8  274.46  4959.7  274.96  4974.4   278.4    5024  278.01
  5052.3  279.83  5066.4  281.98  5178.3  283.72  5207.9  285.49  5236.1  284.95
  5385.7  291.43  5434.1  292.44  5476.6  295.88  5504.8  295.88  5561.4  298.56
#Mann= 7 ,-1 , 0
  4464.2     .07       0  4712.7     .12       0  4821.8      .1       0
  4947.3     .05       0  4959.7      .1       0  5178.3     .07       0
  5385.7     .05       0
Bank Sta=4947.3,4959.7
XS Rating Curve= 0 ,0
Exp/Cntr=0.3,0.1

Type RM Length L Ch R = 1 ,4663    ,449,449,449
BEGIN DESCRIPTION:
Stream0786 7.0
END DESCRIPTION:
XS GIS Cut Line= 3
        2438325.     13605024.99        2438275.       13604625.
      2437924.98     13604324.98
#Sta/Elev= 30
    4597  288.42  4617.1  287.19  4667.5  286.35  4707.8  284.75  4758.2  284.09
  4778.4  284.67  4788.5  283.77  4794.2  280.81  4801.1  278.18  4802.4  273.26
  4802.9  272.76  4814.4  272.76  4814.9  273.26  4818.7  274.56  4828.8   276.4
  4909.4  275.45  4939.6  277.03  4949.7  278.15  4962.3  278.03  4969.9  279.06
  4979.9  277.85  5003.4   277.9  5013.8  279.04  5056.6  280.17  5092.3   279.3
  5113.7  279.87  5164.8  279.69  5191.6  280.26  5312.4  280.15  5461.1  283.22
#Mann= 5 ,-1 , 0
    4597     .07       0  4794.2      .1       0  4802.4     .05       0
  4814.9      .1       0  5164.8     .07       0
Bank Sta=4802.4,4814.9
XS Rating Curve= 0 ,0
Exp/Cntr=0.3,0.1

Type RM Length L Ch R = 1 ,4214    ,460,460,460
BEGIN DESCRIPTION:
Stream0786 6.0
END DESCRIPTION:
XS GIS Cut Line= 3
        2438725.       13604875.        2438425.       13604325.
      2438125.03     13604225.01
#Sta/Elev= 30
  4373.1  283.79  4411.9  282.94  4419.1  282.44  4525.9   281.4  4614.3   280.8
  4800.7  280.05  4816.9  279.36  4822.6  275.03  4838.7  275.01  4844.4  271.46
  4854.3  270.73  4854.8  270.23  4866.8  270.73  4882.4  270.81  4888.1   274.6
  4904.2  271.58  4909.9  274.28  4919.9  274.04    4926  271.08  4931.7  273.86
  4942.2   271.7  4947.9  273.56  4985.8  271.24  4991.5  274.03  5002.2  274.08
  5136.6  278.63  5193.3  278.56  5287.9  280.52  5310.4  281.03  5315.8  281.07
#Mann= 11 ,-1 , 0
  4373.1     .07       0  4411.9     .05       0  4419.1     .07       0
  4525.9     .05       0  4614.3     .07       0  4854.3     .05       0
  4866.8     .07       0  5002.2      .1       0  5193.3    .035       0
  5287.9     .05       0  5310.4    .035       0
Bank Sta=4854.3,4866.8
XS Rating Curve= 0 ,0
Exp/Cntr=0.3,0.1

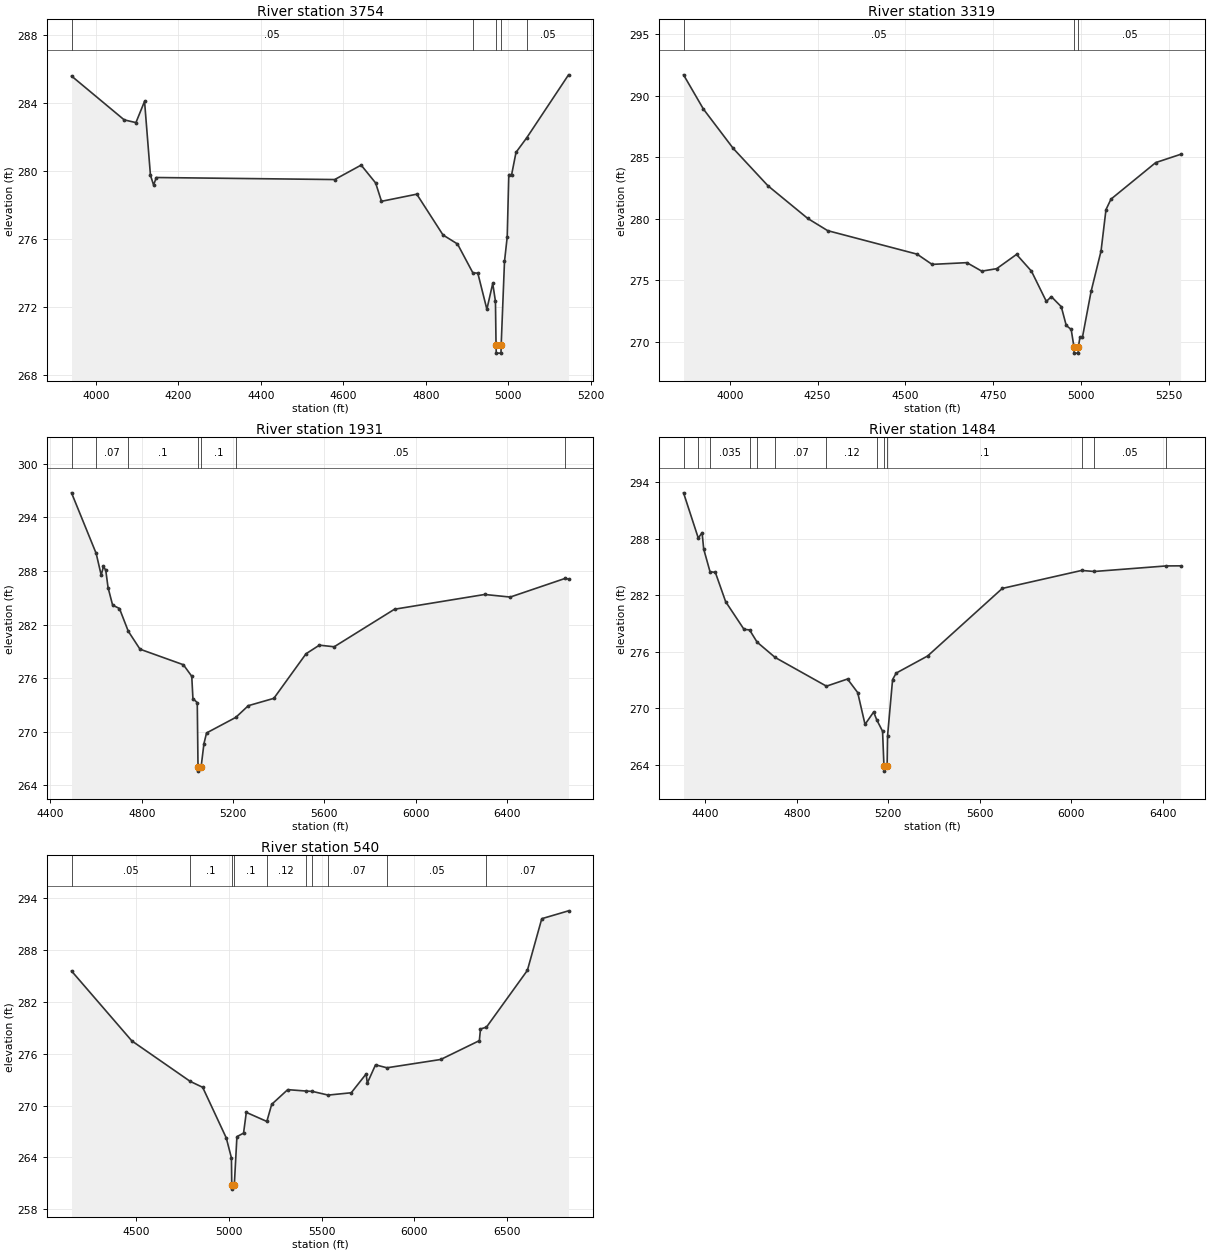
Type RM Length L Ch R = 1 ,3754    ,435,435,435
BEGIN DESCRIPTION:
Stream0786 5.0
END DESCRIPTION:
XS GIS Cut Line= 3
      2439275.01     13604725.01        2438575.       13603925.
      2438474.97     13603824.97
#Sta/Elev= 30
  3941.2   285.6  4068.9  283.02  4097.3  282.86  4118.2  284.11  4132.5  279.76
  4140.1  279.19  4146.7  279.63    4579  279.51  4643.1  280.36  4678.2  279.31
  4692.4  278.23  4777.9  278.65  4841.5  276.25  4876.6  275.72  4913.7  274.03
  4925.9     274  4947.8  271.88    4962   273.4  4968.6  272.34    4970   269.8
  4970.5   269.3    4982   269.3  4982.5   269.8  4990.5  274.69  4997.1  276.14
  5000.9   279.8  5007.8   279.8  5018.4  281.11  5044.5  281.97  5145.7  285.67
#Mann= 5 ,-1 , 0
  3941.2     .05       0  4913.7      .1       0    4970     .05       0
  4982.5      .1       0  5044.5     .05       0
Bank Sta=4970,4982.5
XS Rating Curve= 0 ,0
Exp/Cntr=0.3,0.1

Type RM Length L Ch R = 1 ,3319    ,1388,1388,1388
BEGIN DESCRIPTION:
Stream0786 4.0
END DESCRIPTION:
XS GIS Cut Line= 3
      2439774.97     13604624.97        2438975.       13603825.
      2438774.98     13603624.98
#Sta/Elev= 30
  3868.7  291.69  3925.2  288.91  4010.1  285.71  4109.1  282.67  4222.2  280.02
  4278.8  279.03  4533.3  277.12  4575.8  276.29  4674.8  276.43  4717.2  275.74
  4759.6  275.94  4816.2   277.1  4858.6  275.74    4901  273.28  4915.2  273.67
  4943.5  272.85  4957.6  271.33  4971.7     271  4979.6  269.58  4980.1  269.08
  4991.6  269.08  4992.1  269.58  4996.5  270.35  5003.6  270.35  5028.3  274.09
  5056.6  277.37  5070.7  280.74  5084.9  281.59  5212.2  284.56  5282.9  285.23
#Mann= 3 ,-1 , 0
  3868.7     .05       0  4979.6     .05       0  4992.1     .05       0
Bank Sta=4979.6,4992.1
XS Rating Curve= 0 ,0
Exp/Cntr=0.3,0.1

Type RM Length L Ch R = 1 ,1931    ,447,447,447
BEGIN DESCRIPTION:
Stream0786 3.0
END DESCRIPTION:
XS GIS Cut Line= 3
      2440625.01       13603325.        2440125.       13603325.
      2438474.96     13603625.01
#Sta/Elev= 30
  4492.5  296.73  4600.5  289.95  4622.5  287.53  4632.5  288.49  4642.5  288.07
  4652.5  286.14  4672.5  284.17  4702.5  283.79  4741.1  281.25  4792.5  279.24
  4982.5   277.5  5019.2  276.21  5024.3  273.72  5043.3  273.26  5046.6   266.1
  5047.1   265.6  5060.3   266.1  5072.6  268.68    5084  269.87    5212  271.61
  5266.9  272.92  5378.7  273.74  5519.8  278.73  5578.2  279.69    5643  279.51
  5907.3  283.71  6302.4  285.36  6414.2  285.07  6656.2  287.17  6669.6  287.07
#Mann= 7 ,-1 , 0
  4492.5    .035       0  4600.5     .07       0  4741.1      .1       0
  5046.6     .05       0  5060.3      .1       0    5212     .05       0
  6656.2     .07       0
Bank Sta=5046.6,5060.3
XS Rating Curve= 0 ,0
Exp/Cntr=0.3,0.1

Type RM Length L Ch R = 1 ,1484    ,944,944,944
BEGIN DESCRIPTION:
Stream0786 2.0
END DESCRIPTION:
XS GIS Cut Line= 3
      2440574.99       13603275.        2439975.       13602925.
      2438625.04     13603524.98
#Sta/Elev= 30
  4305.3   292.9  4369.7  288.09  4386.3  288.67  4393.4  286.92  4421.1  284.51
  4444.2  284.45  4489.3  281.33  4569.5  278.39  4593.8  278.33  4626.7  277.03
  4705.8   275.4  4929.8  272.35  5021.8  273.11  5066.3  271.67  5098.4  268.29
    5136   269.6  5149.8  268.76    5175  267.56  5181.1  263.82  5181.6  263.32
  5194.9  263.82  5196.9  267.09  5218.8  273.05  5234.5  273.74    5372  275.56
  5698.2  282.74  6044.9  284.65  6100.1  284.54  6414.2  285.13  6477.2  285.14
#Mann= 13 ,-1 , 0
  4305.3    .035       0  4369.7     .07       0  4421.1    .035       0
  4593.8     .07       0  4626.7    .035       0  4705.8     .07       0
  4929.8     .12       0  5149.8      .1       0  5181.1     .05       0
  5194.9      .1       0  6044.9     .07       0  6100.1     .05       0
  6414.2     .07       0
Bank Sta=5181.1,5194.9
XS Rating Curve= 0 ,0
Exp/Cntr=0.3,0.1

Type RM Length L Ch R = 1 ,540     ,0,0,0
BEGIN DESCRIPTION:
Stream0786 1.0
END DESCRIPTION:
XS GIS Cut Line= 3
      2440825.02     13602675.02        2440225.       13602075.
      2438725.03     13603124.98
#Sta/Elev= 30
  4151.5  285.58  4476.8  277.49  4791.1  272.81  4858.6  272.12  4985.9  266.26
  5013.6  263.95  5015.4  260.84  5015.9  260.34  5029.2  260.84  5043.2  266.41
    5079  266.82  5093.8  269.22  5204.5  268.17  5230.7  270.15    5317  271.85
    5415  271.69  5449.5  271.65  5535.1  271.22  5659.6  271.49  5739.9  273.67
    5746   272.6  5790.4  274.72  5852.1  274.38  6141.8  275.34  6350.2  277.52
  6356.3  278.87  6388.5  279.08  6609.1  285.65  6686.7  291.63    6831  292.54
#Mann= 10 ,-1 , 0
  4151.5     .05       0  4791.1      .1       0  5015.4     .05       0
  5029.2      .1       0  5204.5     .12       0    5415      .1       0
  5449.5     .12       0  5535.1     .07       0  5852.1     .05       0
  6388.5     .07       0
Bank Sta=5015.4,5029.2
XS Rating Curve= 0 ,0
Exp/Cntr=0.3,0.1

Chan Stop Cuts=-1
Use User Specified Reach Order=0
Composite Channel Slope=5