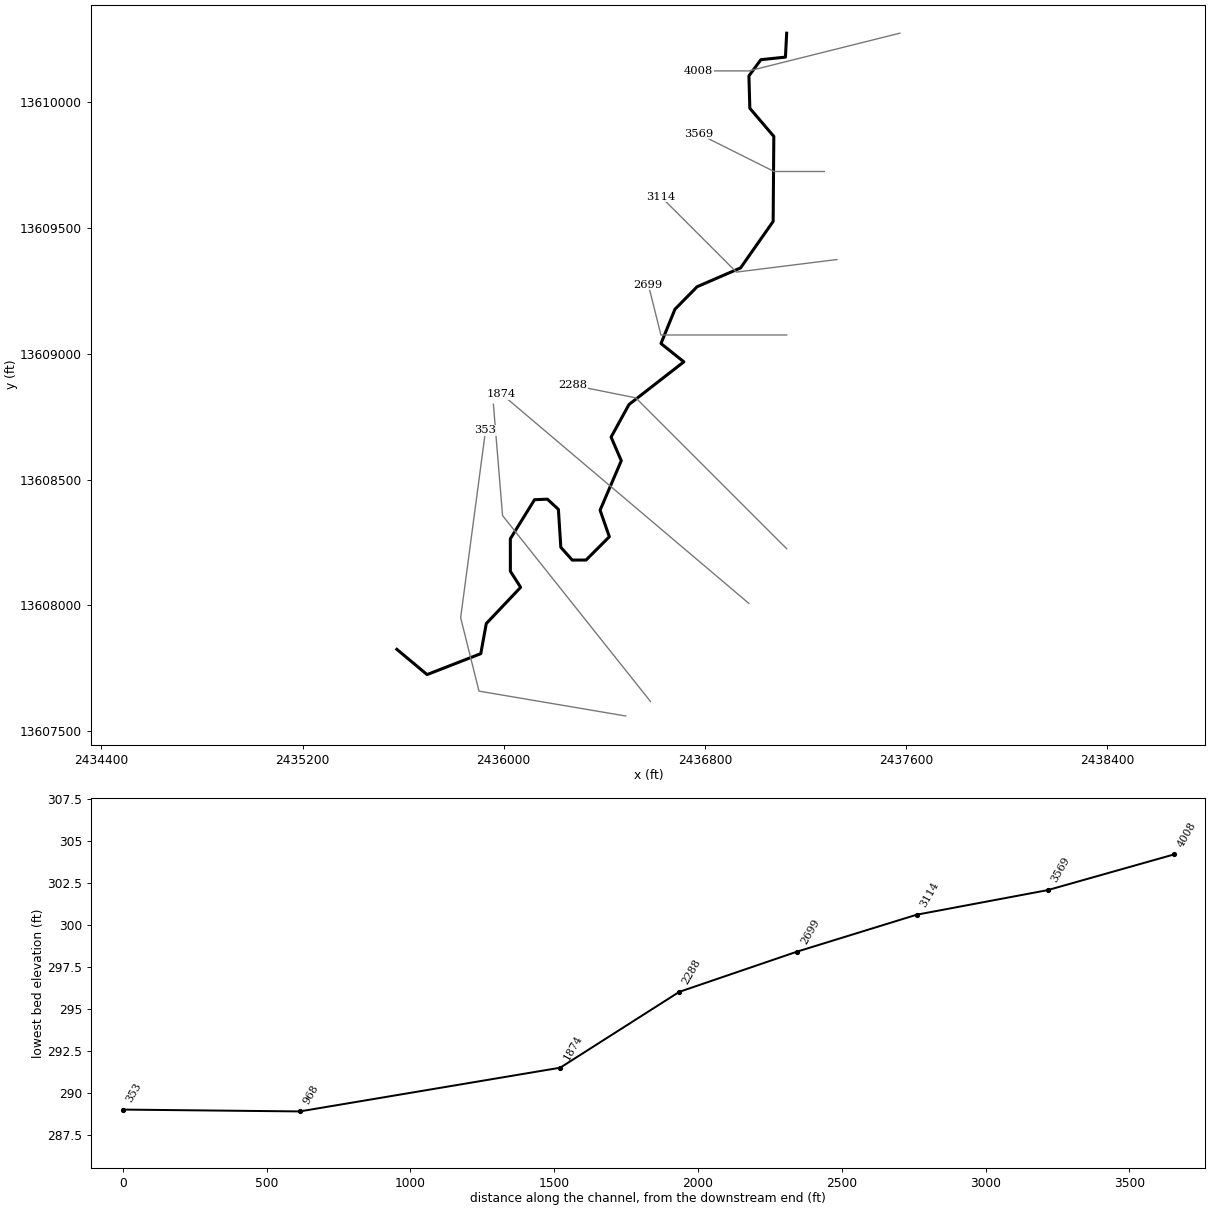
--- Stream0787.prj (project) ---

Proj Title=Stream0787 Base Level Engineering
Current Plan=p01
Default Exp/Contr=0.3,0.1
English Units
Geom File=g01
Flow File=f01
Plan File=p01
BEGIN DESCRIPTION:
Stream0787
END DESCRIPTION:

--- Stream0787.p01 (plan) ---

Plan Title=Multiple Run
Short Identifier=Multiple
Geom File=g01
Flow File=f01
Subcritical Flow
K Sum by GR= 0
Std Step Tol= 0.01
Critical Tol= 0.01
Num of Std Step Trials= 20
Max Error Tol= 0.3
Flow Tol Ratio= 0.001
Split Flow NTrial= 30
Split Flow Tol= 0.02
Split Flow Ratio= 0.02
Log Output Level= 0
Friction Slope Method= 1
Unsteady Friction Slope Method= 2
Unsteady Bridges Friction Slope Method= 1
Parabolic Critical Depth
Global Vel Dist=  1 , 1 , 1
Global Log Level= 0
CheckData=True
Encroach Param= -1, 0, 0, 0
BEGIN DESCRIPTION:
Multiple Run
END DESCRIPTION:

--- Stream0787.f01 (steady flow) ---

Flow Title=Multiple
Number of Profiles=7
Profile Names=10-year,25-year,50-year,1pct_min,100-year,1pct_plu,500-year
River Rch & RM= Stream0787,Reach-1,4008
     536     851    1130     728    1452    2897    2371
River Rch & RM= Stream0787,Reach-1,1874
     767    1244    1676    1093    2181    4351    3655
Boundary for River Rch & Prof#=Stream0787,Reach-1,1
Up Type=0
Dn Type=3
Dn Slope=0.005
Boundary for River Rch & Prof#=Stream0787,Reach-1,2
Up Type=0
Dn Type=3
Dn Slope=0.005
Boundary for River Rch & Prof#=Stream0787,Reach-1,3
Up Type=0
Dn Type=3
Dn Slope=0.005
Boundary for River Rch & Prof#=Stream0787,Reach-1,4
Up Type=0
Dn Type=3
Dn Slope=0.005
Boundary for River Rch & Prof#=Stream0787,Reach-1,5
Up Type=0
Dn Type=3
Dn Slope=0.005
Boundary for River Rch & Prof#=Stream0787,Reach-1,6
Up Type=0
Dn Type=3
Dn Slope=0.005
Boundary for River Rch & Prof#=Stream0787,Reach-1,7
Up Type=0
Dn Type=3
Dn Slope=0.005

--- Stream0787.g01 (geometry) ---

Geom Title=Existing Conditions

River Reach=Stream0787,Reach-1
Reach XY= 30
      2437125.00     13610275.00      2437120.18     13610179.87
      2437022.34     13610169.58      2436974.89     13610105.12
      2436978.54     13609976.47      2437073.94     13609864.56
      2437071.25     13609526.55      2436941.71     13609341.63
      2436768.93     13609266.87      2436680.82     13609177.31
      2436625.26     13609041.01      2436716.20     13608968.20
      2436498.01     13608798.47      2436426.84     13608668.88
      2436467.41     13608575.01      2436383.10     13608378.29
      2436419.89     13608272.69      2436327.28     13608180.05
      2436272.43     13608179.94      2436226.99     13608230.63
      2436217.30     13608381.57      2436173.57     13608422.02
      2436122.49     13608420.05      2436026.19     13608264.50
      2436026.38     13608135.44      2436067.20     13608071.58
      2435930.53     13607927.42      2435908.73     13607807.79
      2435695.13     13607724.57      2435575.00     13607825.00

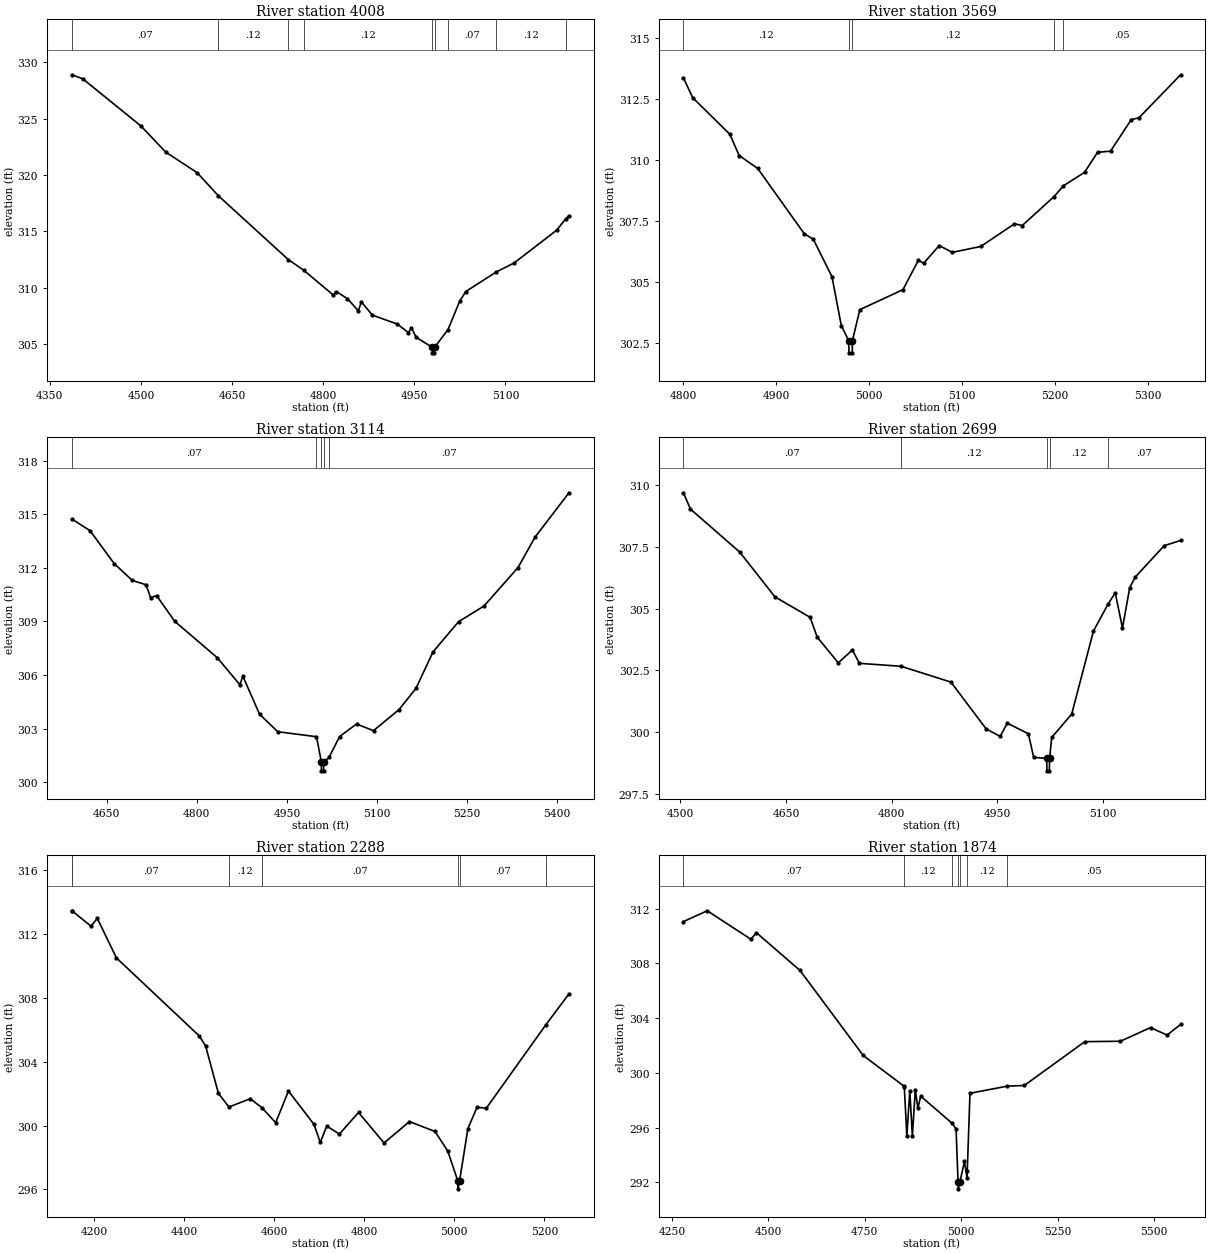
Type RM Length L Ch R = 1,4008,439,439,439
BEGIN DESCRIPTION:
Stream0787 5.0
END DESCRIPTION:
XS GIS Cut Line= 3
      2437575.05     13610275.01      2436975.00     13610125.00
      2436775.01     13610125.00
#Sta/Elev= 30
  4386.2  328.90  4404.3  328.54  4499.6  324.37  4540.9  322.03  4592.4  320.21
  4627.6  318.15  4742.6  312.49  4767.8  311.55  4816.6  309.35  4821.8  309.64
  4839.8  309.03  4857.8  307.95  4863.0  308.73  4881.0  307.56  4922.3  306.76
  4940.3  306.00  4945.4  306.43  4953.2  305.58  4979.5  304.71  4979.8  304.21
  4983.3  304.21  4983.5  304.71  5005.4  306.26  5024.7  308.78  5034.7  309.65
  5084.6  311.38  5114.7  312.20  5184.7  315.11  5199.1  316.10  5204.7  316.38
#Mann=9,-1,0
  4386.2    0.07       0  4627.6    0.12       0  4742.6    0.07       0
  4767.8    0.12       0  4979.5    0.05       0  4983.5    0.12       0
  5005.4    0.07       0  5084.6    0.12       0  5199.1    0.05       0
Bank Sta=4979.5,4983.5
Exp/Cntr=0.3,0.1

Type RM Length L Ch R = 1,3569,455,455,455
BEGIN DESCRIPTION:
Stream0787 4.0
END DESCRIPTION:
XS GIS Cut Line= 3
      2437275.02     13609725.00      2437075.00     13609725.00
      2436775.03     13609874.99
#Sta/Elev= 30
  4800.0  313.36  4810.0  312.55  4850.0  311.05  4860.0  310.18  4880.0  309.65
  4930.0  306.98  4940.0  306.74  4960.0  305.21  4970.0  303.21  4978.0  302.59
  4978.3  302.09  4981.8  302.09  4982.0  302.59  4990.0  303.86  5036.4  304.68
  5053.1  305.89  5058.7  305.76  5075.5  306.49  5089.5  306.21  5120.2  306.45
  5156.5  307.38  5164.9  307.31  5199.0  308.49  5209.3  308.94  5232.0  309.49
  5246.0  310.31  5260.0  310.36  5282.3  311.65  5290.7  311.73  5335.4  313.49
#Mann=5,-1,0
  4800.0    0.12       0  4978.0    0.05       0  4982.0    0.12       0
  5199.0    0.07       0  5209.3    0.05       0
Bank Sta=4978,4982
Exp/Cntr=0.3,0.1

Type RM Length L Ch R = 1,3114,415,415,415
BEGIN DESCRIPTION:
Stream0787 3.0
END DESCRIPTION:
XS GIS Cut Line= 3
      2437325.02     13609375.00      2436925.00     13609325.00
      2436625.00     13609625.00
#Sta/Elev= 30
  4592.1  314.73  4622.4  314.08  4662.7  312.23  4692.9  311.29  4715.6  311.05
  4723.1  310.33  4733.2  310.44  4763.4  309.00  4834.0  306.97  4871.8  305.45
  4876.8  305.93  4904.5  303.80  4934.8  302.82  4999.3  302.54  5007.4  301.13
  5007.6  300.63  5011.1  300.63  5011.4  301.13  5020.1  301.38  5037.7  302.55
  5065.9  303.25  5094.2  302.88  5136.7  304.06  5164.9  305.25  5193.2  307.29
  5235.7  308.98  5278.1  309.86  5334.6  312.01  5362.9  313.71  5419.5  316.20
#Mann=5,-1,0
  4592.1    0.07       0  4999.3    0.12       0  5007.4    0.05       0
  5011.4    0.12       0  5020.1    0.07       0
Bank Sta=5007.4,5011.4
Exp/Cntr=0.3,0.1

Type RM Length L Ch R = 1,2699,411,411,411
BEGIN DESCRIPTION:
Stream0787 2.0
END DESCRIPTION:
XS GIS Cut Line= 3
      2437125.03     13609075.00      2436625.00     13609075.00
      2436575.00     13609275.01
#Sta/Elev= 30
  4504.2  309.69  4514.2  309.03  4584.2  307.29  4634.2  305.48  4684.2  304.65
  4694.2  303.85  4724.2  302.81  4744.2  303.33  4754.2  302.79  4813.4  302.67
  4884.2  302.03  4934.2  300.14  4954.2  299.83  4964.2  300.37  4994.2  299.94
  5001.7  298.99  5020.3  298.94  5020.5  298.44  5024.0  298.44  5024.3  298.94
  5027.4  299.79  5055.8  300.74  5086.7  304.10  5107.3  305.18  5117.6  305.64
  5127.9  304.22  5138.2  305.85  5146.0  306.28  5187.2  307.55  5210.4  307.76
#Mann=5,-1,0
  4504.2    0.07       0  4813.4    0.12       0  5020.3    0.05       0
  5024.3    0.12       0  5107.3    0.07       0
Bank Sta=5020.3,5024.3
Exp/Cntr=0.3,0.1

Type RM Length L Ch R = 1,2288,414,414,414
BEGIN DESCRIPTION:
Stream0787 1.0
END DESCRIPTION:
XS GIS Cut Line= 3
      2437124.99     13608225.01      2436525.00     13608825.00
      2436274.97     13608875.01
#Sta/Elev= 30
  4151.2  313.44  4151.5  313.44  4193.6  312.48  4207.8  312.96  4250.2  310.49
  4434.0  305.61  4448.2  304.98  4476.5  302.02  4499.9  301.16  4547.2  301.68
  4573.1  301.12  4603.7  300.18  4632.0  302.16  4688.6  300.08  4702.7  298.94
  4716.9  299.97  4745.2  299.47  4787.6  300.82  4844.2  298.91  4900.7  300.25
  4957.3  299.63  4985.6  298.41  5007.9  296.54  5008.2  296.04  5011.9  296.54
  5030.3  299.80  5050.7  301.15  5071.1  301.08  5203.5  306.31  5254.7  308.24
#Mann=7,-1,0
  4151.2    0.05       0  4151.5    0.07       0  4499.9    0.12       0
  4573.1    0.07       0  5007.9    0.05       0  5011.9    0.07       0
  5203.5    0.05       0
Bank Sta=5007.9,5011.9
Exp/Cntr=0.3,0.1

Type RM Length L Ch R = 1,1874,906,906,906
BEGIN DESCRIPTION:
XS7728
END DESCRIPTION:
XS GIS Cut Line= 2
      2436974.47     13608007.82      2435990.81     13608840.55
#Sta/Elev= 30
  4280.1  311.05  4341.9  311.84  4455.0  309.76  4469.3  310.24  4582.4  307.48
  4746.2  301.27  4850.9  299.05  4852.7  298.98  4859.3  295.41  4867.0  298.67
  4873.6  295.40  4881.3  298.77  4887.9  297.40  4895.2  298.30  4976.2  296.33
  4986.9  295.91  4992.1  292.03  4992.4  291.53  4996.8  292.03  5008.7  293.53
  5015.3  292.33  5015.9  292.81  5023.0  298.51  5119.4  299.03  5163.8  299.08
  5320.7  302.28  5413.0  302.31  5491.0  303.31  5533.9  302.76  5568.9  303.54
#Mann=7,-1,0
  4280.1    0.07       0  4850.9    0.12       0  4976.2    0.07       0
  4992.1    0.05       0  4996.8    0.07       0  5015.9    0.12       0
  5119.4    0.05       0
Bank Sta=4992.1,4996.8
Exp/Cntr=0.3,0.1

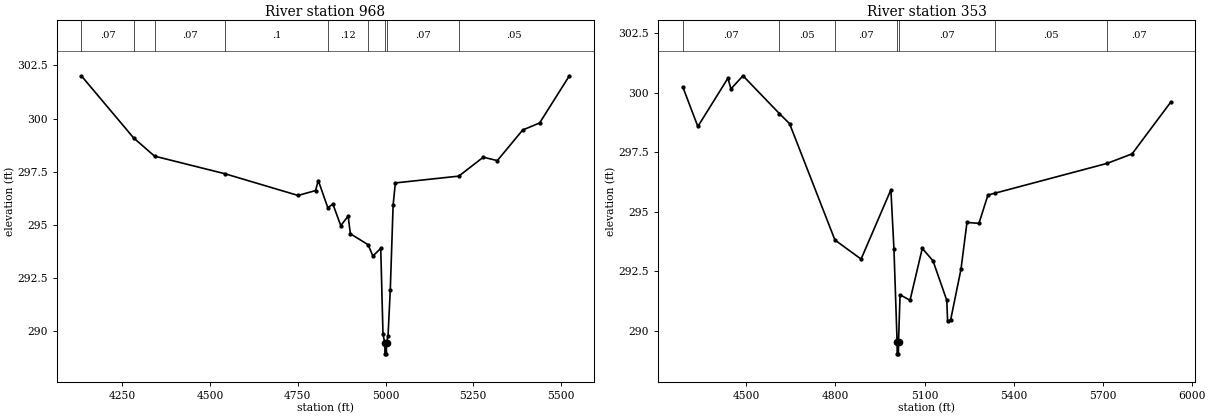
Type RM Length L Ch R = 1,968,615,615,615
BEGIN DESCRIPTION:
XS7729
END DESCRIPTION:
XS GIS Cut Line= 3
      2436583.84     13607617.20      2435995.31     13608356.77
      2435958.85     13608799.51
#Sta/Elev= 30
  4134.2  302.00  4282.5  299.09  4342.2  298.23  4543.0  297.40  4750.9  296.38
  4800.6  296.61  4808.6  297.08  4835.5  295.81  4850.2  295.97  4872.6  294.96
  4893.5  295.41  4899.9  294.58  4950.6  294.06  4963.9  293.53  4986.4  293.89
  4992.8  289.85  4998.0  289.43  4998.4  288.93  5002.5  288.93  5002.8  289.43
  5007.2  289.79  5013.6  291.95  5021.6  295.92  5028.0  296.97  5208.7  297.29
  5278.3  298.18  5318.4  298.02  5390.7  299.46  5438.8  299.79  5523.6  302.01
#Mann=9,-1,0
  4134.2    0.07       0  4282.5    0.12       0  4342.2    0.07       0
  4543.0     0.1       0  4835.5    0.12       0  4950.6    0.07       0
  4998.0    0.05       0  5002.8    0.07       0  5208.7    0.05       0
Bank Sta=4998,5002.8
Exp/Cntr=0.3,0.1

Type RM Length L Ch R = 1,353,0,0,0
BEGIN DESCRIPTION:
XS7727
END DESCRIPTION:
XS GIS Cut Line= 4
      2436484.94     13607559.89      2435901.56     13607658.85
      2435828.65     13607950.52      2435927.61     13608695.32
#Sta/Elev= 30
  4285.6  300.25  4336.3  298.59  4437.7  300.62  4447.8  300.17  4488.4  300.72
  4611.2  299.13  4645.3  298.71  4798.2  293.82  4886.3  293.02  4986.7  295.93
  4997.0  293.44  5007.6  289.54  5007.9  289.04  5012.0  289.04  5012.4  289.54
  5017.6  291.52  5051.2  291.29  5092.4  293.47  5128.5  292.95  5174.9  291.29
  5177.7  290.42  5187.9  290.46  5222.8  292.59  5243.0  294.56  5283.4  294.52
  5313.6  295.71  5337.8  295.79  5715.0  297.04  5799.3  297.44  5929.3  299.61
#Mann=7,-1,0
  4285.6    0.07       0  4611.2    0.05       0  4798.2    0.07       0
  5007.6    0.05       0  5012.4    0.07       0  5337.8    0.05       0
  5715.0    0.07       0
Bank Sta=5007.6,5012.4
Exp/Cntr=0.3,0.1

Chan Stop Cuts=-1