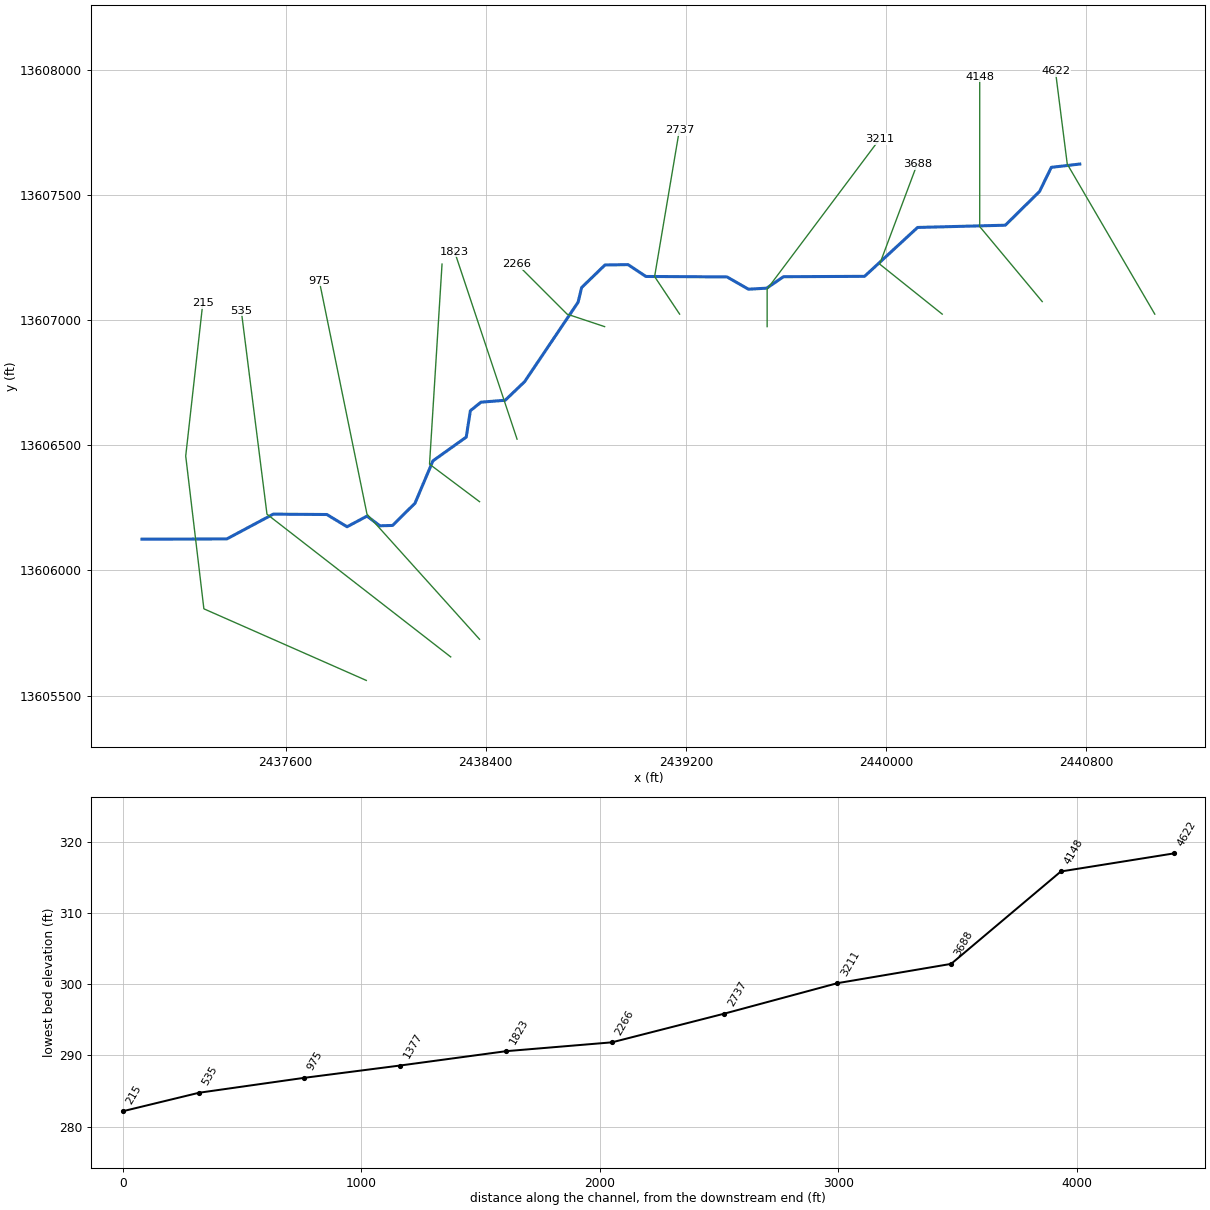
--- Stream0788.prj (project) ---

Proj Title=Stream0788 Base Level Engineering
Current Plan=p01
Default Exp/Contr=0.3,0.1
English Units
Geom File=g01
Flow File=f01
Plan File=p01
Y Axis Title=Elevation
X Axis Title(PF)=Main Channel Distance
X Axis Title(XS)=Station
BEGIN DESCRIPTION:
Stream0788
END DESCRIPTION:
DSS Export Rating Curves= 0
DSS Export Rating Curve Sorted= 0
DSS Export Volume Flow Curves= 0
DXF OffsetX= 0
DXF OffsetY= 0
DXF ScaleX= 1
DXF ScaleY= 10

--- Stream0788.p01 (plan) ---

Plan Title=Multiple Run
Short Identifier=Multiple
Geom File=g01
Flow File=f01
Subcritical Flow
K Sum by GR= 0
Std Step Tol= 0.01
Critical Tol= 0.01
Num of Std Step Trials= 20
Max Error Tol= 0.3
Flow Tol Ratio= 0.001
Split Flow NTrial= 30
Split Flow Tol= 0.02
Split Flow Ratio= 0.02
Log Output Level= 0
Friction Slope Method= 1
Unsteady Friction Slope Method= 2
Unsteady Bridges Friction Slope Method= 1
Parabolic Critical Depth
Global Vel Dist=  1 , 1 , 1
Global Log Level= 0
CheckData=True
Encroach Param= -1, 0, 0, 0
BEGIN DESCRIPTION:
Multiple Run
END DESCRIPTION:

--- Stream0788.f01 (steady flow) ---

Flow Title=Multiple
Number of Profiles=7
Profile Names=10-year,25-year,50-year,1pct_min,100-year,1pct_plu,500-year
River Rch & RM= Stream0788,Reach-1,4622
     730    1191    1613    1058    2112    4213    3583
River Rch & RM= Stream0788,Reach-1,1377
     701    1145    1550    1016    2028    4046    3440
Boundary for River Rch & Prof#=Stream0788,Reach-1,1
Up Type=0
Dn Type=3
Dn Slope=0.005
Boundary for River Rch & Prof#=Stream0788,Reach-1,2
Up Type=0
Dn Type=3
Dn Slope=0.005
Boundary for River Rch & Prof#=Stream0788,Reach-1,3
Up Type=0
Dn Type=3
Dn Slope=0.005
Boundary for River Rch & Prof#=Stream0788,Reach-1,4
Up Type=0
Dn Type=3
Dn Slope=0.005
Boundary for River Rch & Prof#=Stream0788,Reach-1,5
Up Type=0
Dn Type=3
Dn Slope=0.005
Boundary for River Rch & Prof#=Stream0788,Reach-1,6
Up Type=0
Dn Type=3
Dn Slope=0.005
Boundary for River Rch & Prof#=Stream0788,Reach-1,7
Up Type=0
Dn Type=3
Dn Slope=0.005

--- Stream0788.g01 (geometry) ---

Geom Title=Existing Conditions
Program Version=4.10

River Reach=Stream0788      ,Reach-1
Reach XY= 30
        2440775.       13607625.      2440661.28     13607611.81
      2440614.22     13607515.34      2440477.45     13607380.46
      2440126.46     13607371.46      2439914.57     13607176.05
      2439590.22     13607174.48       2439523.4      13607128.7
        2439450.      13607124.6       2439364.5     13607173.78
      2439040.22     13607175.52      2438969.02     13607222.84
      2438876.48     13607221.55      2438783.15     13607131.07
      2438769.13     13607072.72      2438555.23     13606754.87
      2438477.44     13606680.52      2438380.69     13606672.93
      2438338.25     13606638.69      2438321.83     13606533.35
      2438188.61     13606438.24      2438116.87     13606268.92
       2438027.3     13606180.11      2437976.65     13606178.57
        2437925.     13606217.38      2437845.21     13606174.79
       2437764.5     13606223.76      2437549.91     13606225.21
       2437364.5      13606126.2        2437025.       13606125.

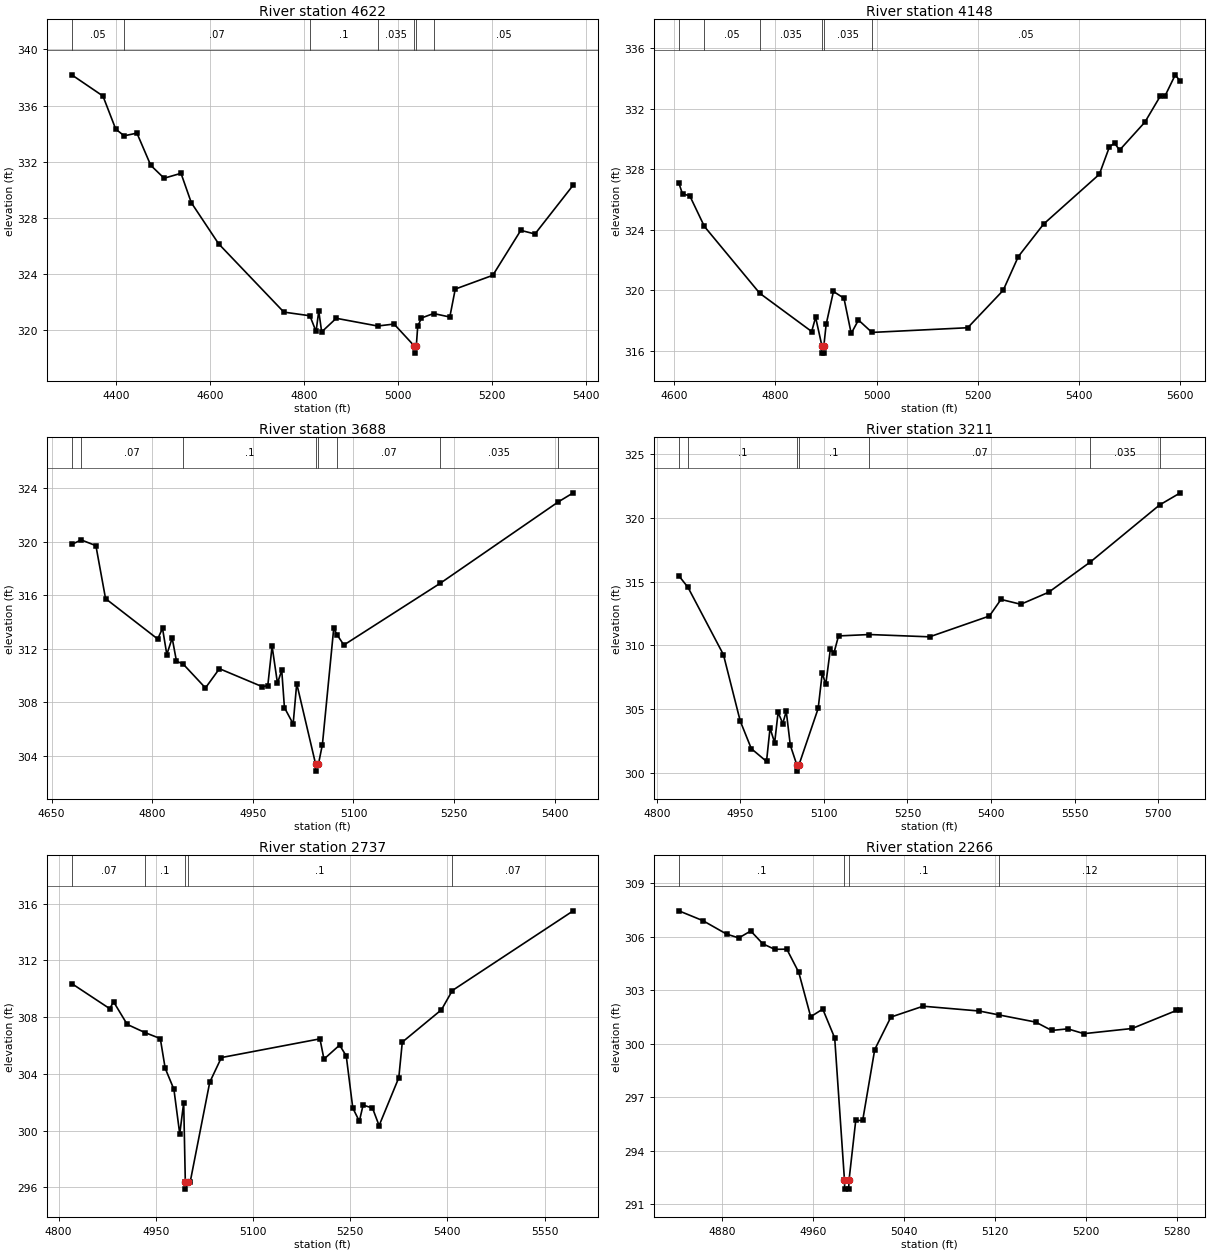
Type RM Length L Ch R = 1 ,4622    ,474,474,474
BEGIN DESCRIPTION:
Stream0788 10.0
END DESCRIPTION:
XS GIS Cut Line= 3
      2441074.99     13607025.02        2440725.       13607625.
      2440677.88     13607995.82
#Sta/Elev= 30
  4304.7  338.19  4371.2  336.68  4398.5  334.32  4416.5  333.85  4443.6  334.04
    4473  331.75  4501.5  330.83  4537.5  331.18  4559.4  329.09  4617.7  326.16
  4756.6   321.3  4812.1  321.04  4825.2  319.92    4831  321.37  4837.2  319.89
  4868.2  320.86  4956.5  320.31  4991.4  320.45  5034.8  318.88    5035  318.38
  5038.8  318.88  5041.8  320.28  5049.7  320.88  5075.6   321.2  5110.2  320.95
  5121.8  322.94  5201.8  323.92  5261.4  327.12  5291.6  326.86  5373.1  330.34
#Mann= 7 ,-1 , 0
  4304.7     .05       0  4416.5     .07       0  4812.1      .1       0
  4956.5    .035       0  5034.8    .035       0  5038.8    .035       0
  5075.6     .05       0
Bank Sta=5034.8,5038.8
XS Rating Curve= 0 ,0
Exp/Cntr=0.3,0.1

Type RM Length L Ch R = 1 ,4148    ,460,460,460
BEGIN DESCRIPTION:
Stream0788 9.0
END DESCRIPTION:
XS GIS Cut Line= 3
      2440625.01     13607074.99        2440375.       13607375.
        2440375.     13607974.98
#Sta/Elev= 30
  4609.6  327.08  4616.8  326.37  4631.1  326.25    4660  324.22  4769.3   319.8
  4871.9  317.27  4879.7  318.21    4892  316.34  4892.3  315.84  4895.8  315.84
    4896  316.34  4900.5  317.74  4914.9  319.92  4935.7  319.47    4950  317.14
  4964.3  318.03    4991  317.21  5180.1  317.52  5250.1  319.99  5280.1  322.23
  5330.1  324.38  5440.1  327.67  5460.1  329.49  5470.1  329.73  5480.1  329.27
  5530.1  331.12  5560.1  332.82  5570.1  332.87  5590.1  334.25  5600.1  333.81
#Mann= 6 ,-1 , 0
  4609.6     .07       0    4660     .05       0  4769.3    .035       0
    4892     .05       0    4896    .035       0    4991     .05       0
Bank Sta=4892,4896
XS Rating Curve= 0 ,0
Exp/Cntr=0.3,0.1

Type RM Length L Ch R = 1 ,3688    ,477,477,477
BEGIN DESCRIPTION:
Stream0788 8.0
END DESCRIPTION:
XS GIS Cut Line= 3
      2440225.01     13607024.99        2439975.       13607225.
      2440125.01     13607625.03
#Sta/Elev= 30
  4680.1  319.81  4694.2  320.15  4716.1  319.72  4730.5  315.76  4808.2  312.74
  4815.4  313.54  4821.8  311.58  4829.8  312.81  4836.2  311.08  4846.1  310.87
  4879.4  309.08  4900.2  310.52  4964.3  309.17  4972.3  309.26  4978.7   312.2
  4986.7  309.44  4993.1  310.39  4997.1  307.61  5010.1  306.39  5015.4  309.41
  5043.7  303.36  5043.9  302.86  5047.7  303.36  5053.7  304.85  5070.6  313.55
  5075.5  313.06  5085.7  312.29  5229.1   316.9  5405.2  322.99  5427.5  323.67
#Mann= 8 ,-1 , 0
  4680.1    .035       0  4694.2     .07       0  4846.1      .1       0
  5043.7     .05       0  5047.7      .1       0  5075.5     .07       0
  5229.1    .035       0  5405.2     .05       0
Bank Sta=5043.7,5047.7
XS Rating Curve= 0 ,0
Exp/Cntr=0.3,0.1

Type RM Length L Ch R = 1 ,3211    ,474,474,474
BEGIN DESCRIPTION:
Stream0788 7.0
END DESCRIPTION:
XS GIS Cut Line= 3
        2439525.     13606974.99        2439525.       13607125.
      2439974.99     13607724.99
#Sta/Elev= 30
  4839.8  315.45  4856.2  314.54  4919.8  309.27  4949.8  304.09  4969.8  301.91
  4997.1  300.91  5003.4  303.51  5011.7  302.38  5017.9  304.75  5026.3  303.88
  5032.5  304.84  5039.8  302.18  5051.4  300.65  5051.6  300.15  5055.4  300.65
  5089.8  305.06  5097.1  307.83  5103.4  306.94  5111.7   309.7  5117.9  309.37
  5126.3  310.74  5181.8  310.85  5289.8  310.67  5397.1   312.3  5417.9   313.6
  5453.4  313.22  5503.4  314.16  5578.5  316.54  5702.6     321  5739.8  321.95
#Mann= 7 ,-1 , 0
  4839.8     .07       0  4856.2      .1       0  5051.4     .05       0
  5055.4      .1       0  5181.8     .07       0  5578.5    .035       0
  5702.6     .05       0
Bank Sta=5051.4,5055.4
XS Rating Curve= 0 ,0
Exp/Cntr=0.3,0.1

Type RM Length L Ch R = 1 ,2737    ,471,471,471
BEGIN DESCRIPTION:
Stream0788 6.0
END DESCRIPTION:
XS GIS Cut Line= 3
      2439174.99     13607025.01        2439075.       13607175.
       2439173.9     13607760.44
#Sta/Elev= 30
  4820.2  310.37  4878.8   308.6  4884.8  309.08  4905.8  307.49  4933.3  306.91
  4956.9  306.49  4964.4   304.4  4977.9  302.91  4986.9  299.76    4993  301.98
  4995.5  296.37  4995.7  295.87  4999.5  296.37    5003  296.37  5033.2  303.41
  5051.2  305.15  5203.3  306.47  5209.5  305.04  5233.7  306.03  5243.9  305.26
    5254  301.59  5264.1  300.66  5269.9   301.8  5284.4  301.59  5294.6  300.35
    5325  303.73  5330.4  306.24  5390.8  308.52  5407.7  309.88  5594.2   315.5
#Mann= 5 ,-1 , 0
  4820.2     .07       0  4933.3      .1       0  4995.5     .05       0
  4999.5      .1       0  5407.7     .07       0
Bank Sta=4995.5,4999.5
XS Rating Curve= 0 ,0
Exp/Cntr=0.3,0.1

Type RM Length L Ch R = 1 ,2266    ,443,443,443
BEGIN DESCRIPTION:
Stream0788 5.0
END DESCRIPTION:
XS GIS Cut Line= 3
      2438874.99       13606975.        2438725.       13607025.
      2438525.03     13607224.97
#Sta/Elev= 30
  4841.9  307.45    4863   306.9    4884  306.14  4894.6  305.93  4905.1  306.32
  4915.7   305.6  4926.2  305.29  4936.8   305.3  4947.3     304  4957.8  301.51
  4968.4  301.94  4978.9  300.32  4987.5  292.34  4987.7  291.84  4991.2  291.84
  4991.5  292.34  4997.4  295.69  5003.5  295.69  5014.1  299.67  5028.3  301.49
  5056.6   302.1  5106.1  301.83  5123.4  301.61  5155.6  301.21  5169.7  300.74
  5183.8  300.83    5198  300.56  5240.4  300.85  5279.3  301.86  5282.8  301.86
#Mann= 4 ,-1 , 0
  4841.9      .1       0  4987.5     .05       0  4991.5      .1       0
  5123.4     .12       0
Bank Sta=4987.5,4991.5
XS Rating Curve= 0 ,0
Exp/Cntr=0.3,0.1

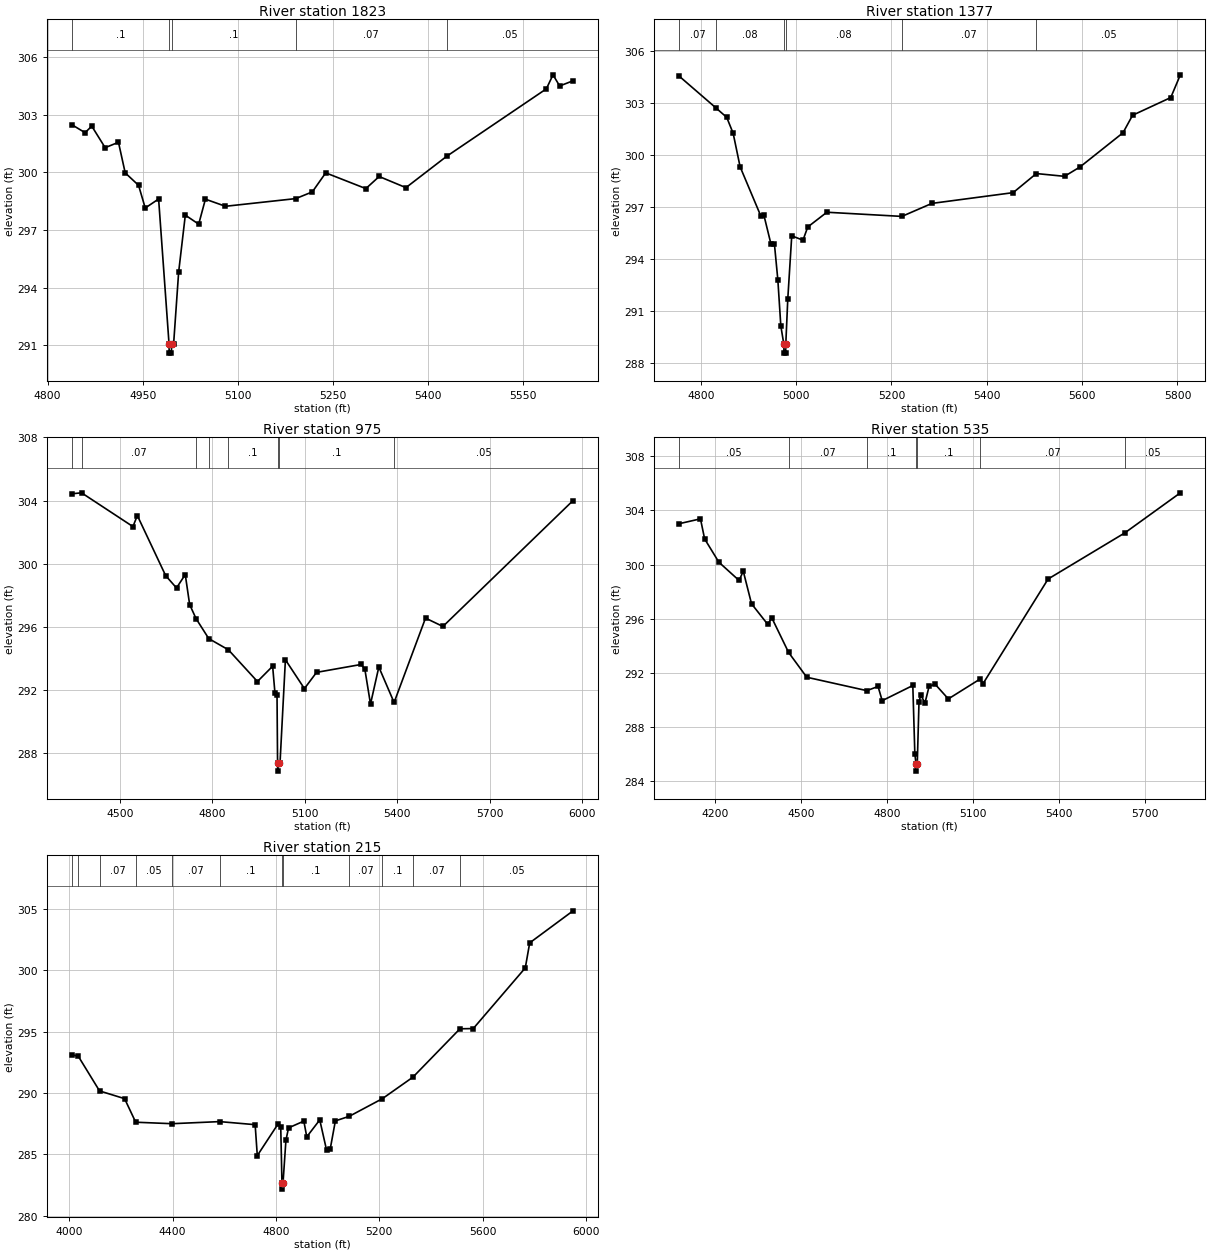
Type RM Length L Ch R = 1 ,1823    ,446,446,446
BEGIN DESCRIPTION:
Stream0788 4.0
END DESCRIPTION:
XS GIS Cut Line= 3
      2438524.99     13606525.04        2438475.       13606675.
      2438275.01     13607274.98
#Sta/Elev= 30
    4838  302.49    4859  302.07  4869.6  302.41  4890.7  301.29  4911.7  301.57
  4922.3  299.98  4943.4  299.33  4953.9  298.15    4975  298.62  4991.4   291.1
  4991.7   290.6  4995.2   290.6  4995.4   291.1  4998.7   291.1  5006.6  294.82
  5017.1  297.78  5038.2  297.31  5048.8  298.61  5080.4  298.24  5191.3  298.64
  5217.4  298.99  5238.5  299.98  5301.8  299.16  5322.8  299.79    5365  299.21
  5429.2  300.84  5586.4  304.35  5596.9  305.08  5607.4   304.5  5628.5  304.77
#Mann= 5 ,-1 , 0
    4838      .1       0  4991.4     .05       0  4995.4      .1       0
  5191.3     .07       0  5429.2     .05       0
Bank Sta=4991.4,4995.4
XS Rating Curve= 0 ,0
Exp/Cntr=0.3,0.1

Type RM Length L Ch R = 1 ,1377    ,402,402,402
BEGIN DESCRIPTION:
Stream0788 3.0
END DESCRIPTION:
XS GIS Cut Line= 3
      2438374.99     13606275.01        2438175.       13606425.
        2438225.     13607225.05
#Sta/Elev= 30
  4754.5  304.55  4831.2  302.73  4854.5  302.17    4868  301.25  4882.6  299.32
  4926.4  296.46  4932.6  296.52  4947.2  294.88  4954.5  294.89  4961.8  292.79
    4968  290.15  4974.4  289.08  4974.6  288.58  4978.1  288.58  4978.4  289.08
  4982.6   291.7  4990.9  295.34  5014.5  295.09  5024.5  295.85  5064.6   296.7
  5221.9  296.46    5285  297.21  5455.4  297.83    5504  298.93  5563.1  298.77
  5595.6  299.31  5685.8  301.28  5705.9  302.29    5786  303.31  5806.1  304.62
#Mann= 6 ,-1 , 0
  4754.5     .07       0  4831.2     .08       0  4974.4     .07       0
  4978.4     .08       0  5221.9     .07       0    5504     .05       0
Bank Sta=4974.4,4978.4
XS Rating Curve= 0 ,0
Exp/Cntr=0.3,0.1

Type RM Length L Ch R = 1 ,975     ,440,440,440
BEGIN DESCRIPTION:
Stream0788 2.0
END DESCRIPTION:
XS GIS Cut Line= 3
      2438375.02     13605724.97        2437925.       13606225.
      2437734.13     13607158.37
#Sta/Elev= 30
  4344.3  304.43  4376.2  304.49  4542.8  302.35    4557  303.05  4648.9  299.24
    4684  298.46  4712.4  299.31  4726.6  297.41  4747.3  296.52  4788.6  295.25
  4852.3  294.54  4946.4  292.53  4995.7   293.5  5003.2   291.8  5009.9  291.67
  5011.7  287.35  5011.9  286.85  5015.7  287.35  5019.6  287.35  5037.1  293.91
  5098.7  292.08  5138.1  293.11  5282.4  293.61  5294.6  293.32    5313   291.1
    5340  293.45  5389.5   291.2  5491.4  296.55  5547.8  296.02  5969.7     304
#Mann= 8 ,-1 , 0
  4344.3     .05       0  4376.2     .07       0  4747.3      .1       0
  4788.6     .05       0  4852.3      .1       0  5011.7     .05       0
  5015.7      .1       0  5389.5     .05       0
Bank Sta=5011.7,5015.7
XS Rating Curve= 0 ,0
Exp/Cntr=0.3,0.1

Type RM Length L Ch R = 1 ,535     ,320,320,320
BEGIN DESCRIPTION:
Stream0788 1.0
END DESCRIPTION:
XS GIS Cut Line= 3
      2438259.61     13605654.47        2437525.       13606225.
      2437422.24      13607038.7
#Sta/Elev= 30
  4074.7  303.02  4149.5  303.38    4164   301.9  4213.8  300.18  4284.4  298.83
  4298.9  299.52  4327.8  297.11  4384.4  295.59  4398.4  296.08  4457.2  293.52
  4520.6  291.69  4730.4   290.7  4769.5  291.01    4784  289.96  4890.9  291.08
    4898  286.03  4902.3  285.26  4902.6  284.76  4906.4  285.26  4912.5  289.87
  4918.9  290.38  4933.3  289.78  4947.8  291.02  4968.6  291.18  5014.9  290.09
    5126  291.56  5135.9  291.21  5363.3  298.94  5630.9  302.34    5825   305.3
#Mann= 7 ,-1 , 0
  4074.7     .05       0  4457.2     .07       0  4730.4      .1       0
  4902.3     .05       0  4906.4      .1       0    5126     .07       0
  5630.9     .05       0
Bank Sta=4902.3,4906.4
XS Rating Curve= 0 ,0
Exp/Cntr=0.3,0.1

Type RM Length L Ch R = 1 ,215     ,0,0,0
BEGIN DESCRIPTION:
XS7730
END DESCRIPTION:
XS GIS Cut Line= 4
      2437922.09     13605560.47       2437272.7     13605846.71
      2437200.06     13606457.68      2437268.42     13607068.62
#Sta/Elev= 30
  4010.1  293.12  4035.9  292.97  4117.7  290.16  4214.6  289.53  4257.6  287.61
  4398.3  287.49  4582.3  287.66  4719.8  287.41  4728.1  284.89  4808.7  287.48
  4818.8  287.25  4823.5  282.66  4823.8  282.16  4827.6  282.66  4838.9  286.14
    4849  287.15  4908.2   287.7  4919.5  286.42  4969.8   287.8  4995.9  285.36
  5010.1  285.41  5030.2  287.72  5083.8  288.09  5212.2  289.53  5330.2  291.28
  5512.2  295.22  5563.8  295.24    5765  300.18  5782.1  302.22  5949.8  304.83
#Mann= 12 ,-1 , 0
  4010.1     .07       0  4035.9     .05       0  4117.7     .07       0
  4257.6     .05       0  4398.3     .07       0  4582.3      .1       0
  4823.5     .05       0  4827.6      .1       0  5083.8     .07       0
  5212.2      .1       0  5330.2     .07       0  5512.2     .05       0
Bank Sta=4823.5,4827.6
XS Rating Curve= 0 ,0
Exp/Cntr=0.3,0.1

Chan Stop Cuts=-1
Use User Specified Reach Order=0
Composite Channel Slope=5