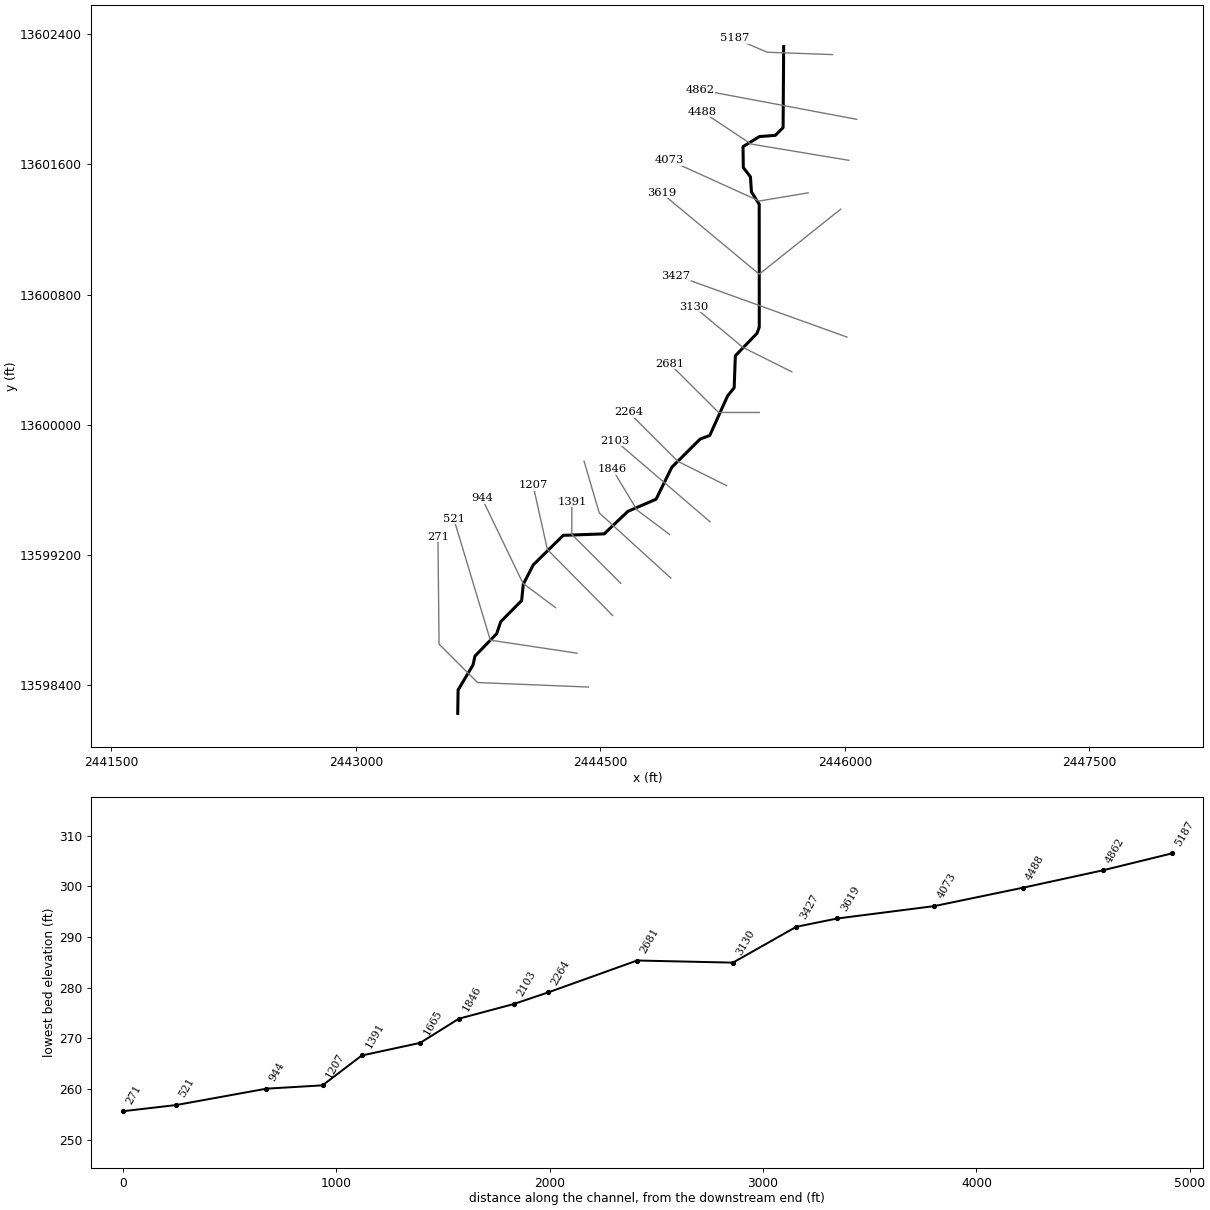
--- Stream0789.prj (project) ---

Proj Title=Stream0789 Base Level Engineering
Current Plan=p01
Default Exp/Contr=0.3,0.1
English Units
Geom File=g01
Flow File=f01
Plan File=p01
BEGIN DESCRIPTION:
Stream0789
END DESCRIPTION:

--- Stream0789.p01 (plan) ---

Plan Title=Multiple Run
Short Identifier=Multiple
Geom File=g01
Flow File=f01
Subcritical Flow
K Sum by GR= 0
Std Step Tol= 0.01
Critical Tol= 0.01
Num of Std Step Trials= 20
Max Error Tol= 0.3
Flow Tol Ratio= 0.001
Split Flow NTrial= 30
Split Flow Tol= 0.02
Split Flow Ratio= 0.02
Log Output Level= 0
Friction Slope Method= 1
Unsteady Friction Slope Method= 2
Unsteady Bridges Friction Slope Method= 1
Parabolic Critical Depth
Global Vel Dist=  1 , 1 , 1
Global Log Level= 0
CheckData=True
Encroach Param= -1, 0, 0, 0
BEGIN DESCRIPTION:
Multiple Run
END DESCRIPTION:

--- Stream0789.f01 (steady flow) ---

Flow Title=Multiple
Number of Profiles=7
Profile Names=10-year,25-year,50-year,1pct_min,100-year,1pct_plu,500-year
River Rch & RM= Stream0789,Reach-1,5187
     676    1103    1494     981    1958    3906    3329
Boundary for River Rch & Prof#=Stream0789,Reach-1,1
Up Type=0
Dn Type=3
Dn Slope=0.005
Boundary for River Rch & Prof#=Stream0789,Reach-1,2
Up Type=0
Dn Type=3
Dn Slope=0.005
Boundary for River Rch & Prof#=Stream0789,Reach-1,3
Up Type=0
Dn Type=3
Dn Slope=0.005
Boundary for River Rch & Prof#=Stream0789,Reach-1,4
Up Type=0
Dn Type=3
Dn Slope=0.005
Boundary for River Rch & Prof#=Stream0789,Reach-1,5
Up Type=0
Dn Type=3
Dn Slope=0.005
Boundary for River Rch & Prof#=Stream0789,Reach-1,6
Up Type=0
Dn Type=3
Dn Slope=0.005
Boundary for River Rch & Prof#=Stream0789,Reach-1,7
Up Type=0
Dn Type=3
Dn Slope=0.005

--- Stream0789.g01 (geometry) ---

Geom Title=Existing Conditions

River Reach=Stream0789,Reach-1
Reach XY= 30
      2445625.00     13602325.00      2445621.56     13601826.22
      2445573.75     13601778.51      2445476.56     13601771.18
      2445375.64     13601709.17      2445377.25     13601580.95
      2445421.14     13601523.40      2445427.36     13601430.98
      2445474.93     13601354.97      2445475.30     13600599.88
      2445461.63     13600561.68      2445328.54     13600423.54
      2445321.25     13600226.55      2445281.12     13600177.18
      2445171.49     13599933.48      2445112.02     13599911.27
      2444938.62     13599738.21      2444842.05     13599541.49
      2444668.94     13599466.86      2444523.54     13599328.54
      2444272.55     13599319.54      2444088.62     13599138.22
      2444027.33     13599019.03      2444017.14     13598918.83
      2443888.63     13598788.21      2443864.22     13598715.32
      2443730.83     13598577.30      2443718.90     13598522.81
      2443627.20     13598369.09      2443625.00     13598225.00

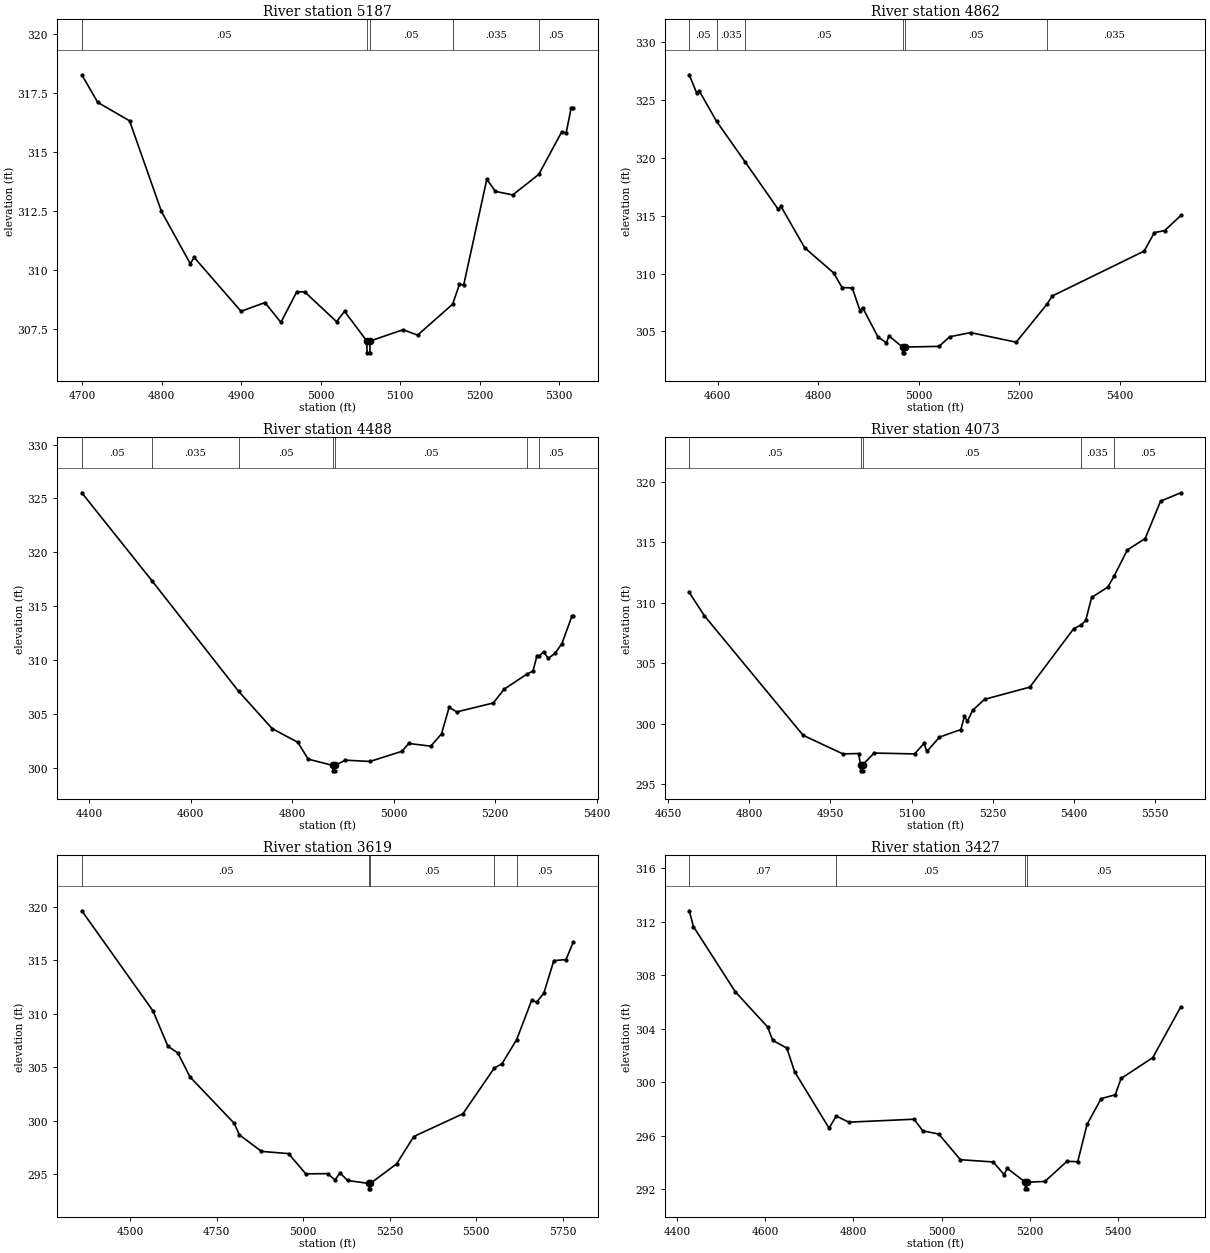
Type RM Length L Ch R = 1,5187,325,325,325
BEGIN DESCRIPTION:
Stream0789 11.0
END DESCRIPTION:
XS GIS Cut Line= 3
      2445925.00     13602275.00      2445524.31     13602289.58
      2445325.00     13602375.00
#Sta/Elev= 30
  4699.8  318.28  4719.8  317.11  4759.8  316.33  4799.9  312.49  4836.1  310.28
  4841.1  310.54  4899.9  308.26  4930.0  308.63  4950.0  307.79  4970.0  309.09
  4980.0  309.08  5020.0  307.82  5030.0  308.26  5058.0  307.00  5058.3  306.50
  5061.8  306.50  5062.0  307.00  5103.6  307.48  5121.8  307.25  5165.8  308.56
  5174.4  309.40  5179.8  309.38  5208.8  313.85  5219.7  313.34  5241.4  313.19
  5274.1  314.06  5303.1  315.87  5308.5  315.81  5314.9  316.89  5317.6  316.89
#Mann=5,-1,0
  4699.8    0.05       0  5058.0    0.05       0  5062.0    0.05       0
  5165.8   0.035       0  5274.1    0.05       0
Bank Sta=5058,5062
Exp/Cntr=0.3,0.1

Type RM Length L Ch R = 1,4862,374,374,374
BEGIN DESCRIPTION:
H21053
END DESCRIPTION:
XS GIS Cut Line= 2
      2446073.42     13601877.10      2445113.34     13602058.14
#Sta/Elev= 30
  4543.7  327.20  4558.4  325.62  4563.4  325.81  4598.0  323.17  4654.3  319.69
  4720.7  315.55  4725.8  315.83  4773.1  312.24  4830.6  310.06  4847.4  308.80
  4867.7  308.76  4883.1  306.79  4888.2  307.07  4918.6  304.53  4935.5  304.02
  4940.6  304.61  4967.5  303.65  4967.7  303.15  4971.2  303.15  4971.5  303.65
  5040.3  303.71  5061.1  304.54  5102.9  304.90  5193.4  304.07  5254.5  307.35
  5265.3  308.07  5447.8  311.95  5468.1  313.55  5488.5  313.72  5520.7  315.03
#Mann=6,-1,0
  4543.7    0.05       0  4598.0   0.035       0  4654.3    0.05       0
  4967.5    0.05       0  4971.5    0.05       0  5254.5   0.035       0
Bank Sta=4967.5,4971.5
Exp/Cntr=0.3,0.1

Type RM Length L Ch R = 1,4488,415,415,415
BEGIN DESCRIPTION:
Stream0789 10.0
END DESCRIPTION:
XS GIS Cut Line= 3
      2446025.05     13601624.99      2445425.00     13601725.00
      2445124.98     13601925.01
#Sta/Elev= 30
  4385.5  325.53  4523.5  317.38  4694.4  307.11  4760.7  303.64  4811.3  302.37
  4831.6  300.81  4880.3  300.22  4880.6  299.72  4884.1  299.72  4884.3  300.22
  4905.1  300.71  4953.3  300.59  5016.4  301.53  5029.9  302.26  5073.4  302.01
  5094.5  303.15  5109.5  305.61  5124.5  305.19  5196.6  306.02  5217.7  307.29
  5262.8  308.70  5274.8  308.98  5282.3  310.34  5286.3  310.35  5295.8  310.77
  5304.8  310.15  5318.3  310.63  5331.8  311.53  5351.4  314.06  5354.4  314.06
#Mann=7,-1,0
  4385.5    0.05       0  4523.5   0.035       0  4694.4    0.05       0
  4880.3    0.05       0  4884.3    0.05       0  5262.8   0.035       0
  5286.3    0.05       0
Bank Sta=4880.3,4884.3
Exp/Cntr=0.3,0.1

Type RM Length L Ch R = 1,4073,454,454,454
BEGIN DESCRIPTION:
Stream0789 9.0
END DESCRIPTION:
XS GIS Cut Line= 3
      2445774.98     13601425.00      2445475.00     13601375.00
      2444924.97     13601625.01
#Sta/Elev= 30
  4689.3  310.84  4717.2  308.92  4899.6  299.04  4973.1  297.50  5002.2  297.53
  5005.7  296.60  5005.9  296.10  5009.4  296.10  5009.7  296.60  5030.8  297.57
  5105.5  297.50  5123.0  298.36  5128.5  297.70  5151.6  298.89  5191.1  299.51
  5197.7  300.61  5203.2  300.20  5213.1  301.12  5235.1  302.01  5318.6  303.02
  5399.8  307.86  5413.0  308.14  5421.8  308.53  5432.8  310.43  5462.5  311.28
  5474.1  312.18  5498.7  314.35  5531.7  315.30  5560.2  318.39  5597.6  319.08
#Mann=5,-1,0
  4689.3    0.05       0  5005.7    0.05       0  5009.7    0.05       0
  5413.0   0.035       0  5474.1    0.05       0
Bank Sta=5005.7,5009.7
Exp/Cntr=0.3,0.1

Type RM Length L Ch R = 1,3619,192,192,192
BEGIN DESCRIPTION:
Stream0789 8.0
END DESCRIPTION:
XS GIS Cut Line= 3
      2445975.00     13601325.00      2445475.00     13600925.00
      2444875.03     13601424.98
#Sta/Elev= 30
  4359.7  319.64  4565.4  310.29  4608.6  306.99  4637.4  306.35  4672.7  304.11
  4800.7  299.77  4815.1  298.71  4879.2  297.16  4957.6  296.95  5007.2  295.06
  5071.0  295.08  5091.8  294.48  5106.1  295.16  5128.2  294.44  5190.0  294.16
  5190.3  293.66  5193.8  293.66  5194.0  294.16  5270.1  296.00  5319.6  298.55
  5461.5  300.67  5552.5  304.95  5574.7  305.35  5616.8  307.59  5660.6  311.29
  5674.9  311.10  5695.8  311.96  5724.4  314.98  5759.6  315.08  5781.0  316.73
#Mann=5,-1,0
  4359.7    0.05       0  5190.0    0.05       0  5194.0    0.05       0
  5552.5   0.035       0  5616.8    0.05       0
Bank Sta=5190,5194
Exp/Cntr=0.3,0.1

Type RM Length L Ch R = 1,3427,297,297,297
BEGIN DESCRIPTION:
H21057
END DESCRIPTION:
XS GIS Cut Line= 2
      2446013.08     13600538.37      2444965.16     13600916.94
#Sta/Elev= 30
  4427.9  312.83  4437.3  311.65  4532.2  306.77  4605.3  304.14  4617.2  303.13
  4649.1  302.55  4666.6  300.79  4744.8  296.56  4761.1  297.47  4789.3  297.01
  4937.3  297.23  4957.3  296.36  4993.3  296.12  5042.5  294.20  5117.0  294.03
  5141.3  293.09  5148.9  293.55  5189.4  292.52  5189.6  292.02  5193.1  292.02
  5193.4  292.52  5233.9  292.57  5284.0  294.08  5308.4  294.05  5329.6  296.85
  5361.5  298.77  5393.4  299.06  5406.7  300.28  5478.5  301.84  5542.1  305.65
#Mann=4,-1,0
  4427.9    0.07       0  4761.1    0.05       0  5189.4    0.05       0
  5193.4    0.05       0
Bank Sta=5189.4,5193.4
Exp/Cntr=0.3,0.1

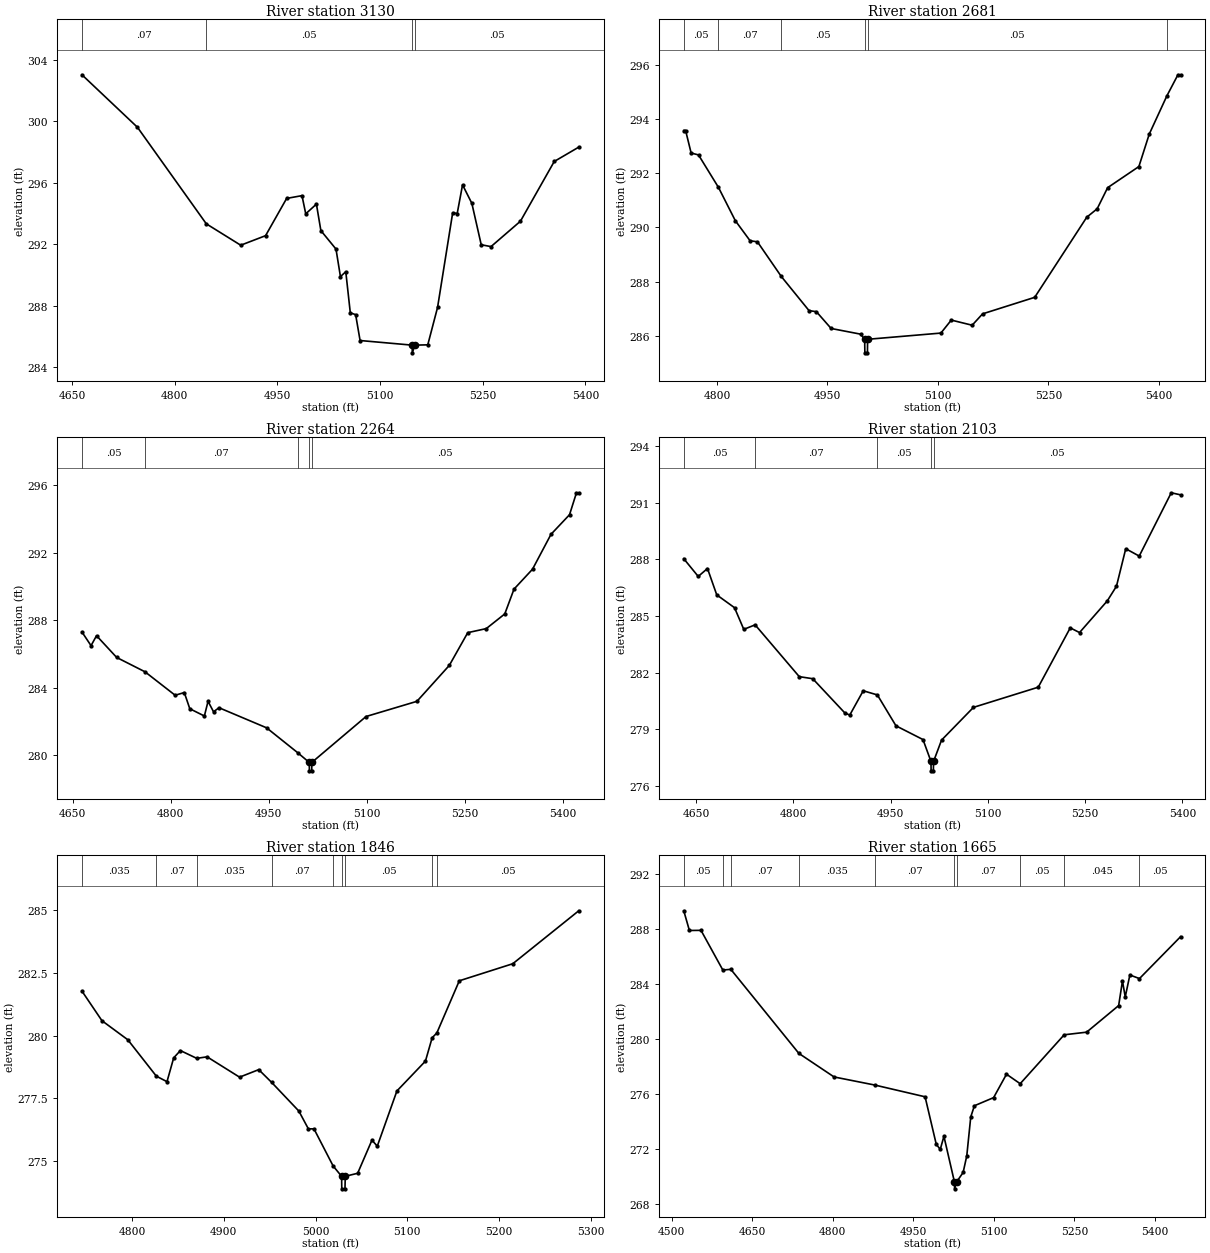
Type RM Length L Ch R = 1,3130,449,449,449
BEGIN DESCRIPTION:
Stream0789 7.0
END DESCRIPTION:
XS GIS Cut Line= 3
      2445675.02     13600324.99      2445375.00     13600475.00
      2445075.03     13600724.97
#Sta/Elev= 30
  4664.3  303.01  4745.4  299.60  4846.0  293.33  4896.3  291.94  4932.6  292.56
  4963.4  294.98  4985.8  295.16  4991.3  293.98  5006.9  294.61  5013.4  292.89
  5035.5  291.69  5042.0  289.90  5049.8  290.22  5056.4  287.55  5064.2  287.43
  5070.7  285.75  5146.8  285.45  5147.0  284.95  5150.8  285.45  5169.6  285.47
  5183.9  287.90  5206.0  294.05  5212.6  294.00  5220.4  295.86  5234.0  294.66
  5247.7  291.97  5262.0  291.85  5305.0  293.50  5354.4  297.38  5390.2  298.31
#Mann=4,-1,0
  4664.3    0.07       0  4846.0    0.05       0  5146.8    0.05       0
  5150.8    0.05       0
Bank Sta=5146.8,5150.8
Exp/Cntr=0.3,0.1

Type RM Length L Ch R = 1,2681,417,417,417
BEGIN DESCRIPTION:
Stream0789 6.0
END DESCRIPTION:
XS GIS Cut Line= 3
      2445475.01     13600075.00      2445225.00     13600075.00
      2444924.98     13600375.02
#Sta/Elev= 30
  4755.0  293.58  4757.5  293.58  4765.0  292.75  4775.0  292.68  4802.1  291.48
  4825.0  290.25  4845.0  289.51  4855.0  289.47  4887.4  288.19  4925.0  286.93
  4935.0  286.89  4955.0  286.27  4995.0  286.06  5000.5  285.87  5000.8  285.37
  5004.3  285.37  5004.5  285.87  5104.0  286.10  5118.1  286.58  5146.4  286.39
  5160.6  286.81  5231.3  287.42  5302.0  290.38  5316.1  290.69  5330.3  291.47
  5372.7  292.25  5386.8  293.45  5410.7  294.86  5425.7  295.64  5429.3  295.64
#Mann=6,-1,0
  4755.0    0.05       0  4802.1    0.07       0  4887.4    0.05       0
  5000.5    0.05       0  5004.5    0.05       0  5410.7   0.035       0
Bank Sta=5000.5,5004.5
Exp/Cntr=0.3,0.1

Type RM Length L Ch R = 1,2264,161,161,161
BEGIN DESCRIPTION:
Stream0789 5.0
END DESCRIPTION:
XS GIS Cut Line= 3
      2445274.97     13599625.01      2444975.00     13599775.00
      2444675.03     13600074.97
#Sta/Elev= 30
  4664.4  287.30  4678.3  286.49  4686.7  287.08  4717.5  285.79  4760.8  284.94
  4806.9  283.55  4820.9  283.71  4829.3  282.75  4851.6  282.32  4857.2  283.19
  4865.6  282.57  4874.0  282.81  4946.7  281.62  4994.1  280.15  5011.9  279.57
  5012.2  279.07  5015.7  279.07  5015.9  279.57  5098.8  282.29  5176.6  283.19
  5226.1  285.32  5254.3  287.26  5282.6  287.50  5310.9  288.37  5325.0  289.84
  5353.3  291.02  5381.6  293.09  5409.9  294.25  5420.5  295.55  5424.0  295.55
#Mann=5,-1,0
  4664.4    0.05       0  4760.8    0.07       0  4994.1    0.05       0
  5011.9    0.05       0  5015.9    0.05       0
Bank Sta=5011.9,5015.9
Exp/Cntr=0.3,0.1

Type RM Length L Ch R = 1,2103,257,257,257
BEGIN DESCRIPTION:
H21056
END DESCRIPTION:
XS GIS Cut Line= 2
      2445173.65     13599402.63      2444592.07     13599901.92
#Sta/Elev= 30
  4630.8  288.04  4653.1  287.10  4667.4  287.52  4681.7  286.12  4709.1  285.44
  4723.4  284.29  4740.9  284.53  4809.0  281.78  4829.8  281.67  4879.4  279.85
  4886.9  279.74  4907.7  281.03  4929.5  280.81  4958.2  279.17  4999.9  278.44
  5012.2  277.28  5012.4  276.78  5015.9  276.78  5016.2  277.28  5028.5  278.41
  5077.8  280.15  5177.7  281.22  5227.1  284.37  5241.4  284.12  5284.2  285.80
  5298.4  286.58  5312.7  288.57  5333.5  288.18  5382.9  291.54  5397.3  291.43
#Mann=5,-1,0
  4630.8    0.05       0  4740.9    0.07       0  4929.5    0.05       0
  5012.2    0.05       0  5016.2    0.05       0
Bank Sta=5012.2,5016.2
Exp/Cntr=0.3,0.1

Type RM Length L Ch R = 1,1846,181,181,181
BEGIN DESCRIPTION:
Stream0789 4.0
END DESCRIPTION:
XS GIS Cut Line= 3
      2444924.98     13599325.02      2444725.00     13599475.00
      2444575.01     13599724.99
#Sta/Elev= 30
  4745.4  281.77  4767.2  280.59  4795.4  279.83  4826.5  278.38  4838.1  278.16
  4845.4  279.11  4852.7  279.40  4870.5  279.09  4881.8  279.15  4917.2  278.34
  4938.1  278.64  4952.2  278.13  4981.8  276.99  4992.2  276.28  4998.3  276.28
  5019.2  274.80  5028.4  274.39  5028.6  273.89  5032.1  273.89  5032.4  274.39
  5045.9  274.51  5061.5  275.83  5067.3  275.59  5088.7  277.79  5119.8  278.98
  5127.1  279.91  5132.2  280.10  5156.7  282.18  5215.0  282.86  5286.9  284.97
#Mann=9,-1,0
  4745.4   0.035       0  4826.5    0.07       0  4870.5   0.035       0
  4952.2    0.07       0  5019.2    0.05       0  5028.4    0.05       0
  5032.4    0.05       0  5127.1    0.07       0  5132.2    0.05       0
Bank Sta=5028.4,5032.4
Exp/Cntr=0.3,0.1

Type RM Length L Ch R = 1,1665,274,274,274
BEGIN DESCRIPTION:
H21055
END DESCRIPTION:
XS GIS Cut Line= 3
      2444932.25     13599056.97      2444493.32     13599457.49
      2444400.05     13599775.70
#Sta/Elev= 30
  4522.2  289.30  4532.7  287.87  4554.3  287.88  4595.0  285.00  4609.9  285.05
  4736.7  278.95  4802.3  277.24  4878.5  276.65  4971.9  275.80  4992.8  272.34
  5000.2  271.99  5007.0  272.93  5026.6  269.62  5026.9  269.12  5030.6  269.62
  5042.8  270.31  5049.6  271.52  5057.0  274.34  5063.8  275.15  5099.6  275.74
  5123.6  277.44  5149.1  276.75  5231.1  280.30  5272.9  280.49  5332.6  282.42
  5339.7  284.20  5344.9  283.05  5353.5  284.64  5371.4  284.38  5448.0  287.42
#Mann=10,-1,0
  4522.2    0.05       0  4595.0   0.035       0  4609.9    0.07       0
  4736.7   0.035       0  4878.5    0.07       0  5026.6    0.05       0
  5030.6    0.07       0  5149.1    0.05       0  5231.1   0.045       0
  5371.4    0.05       0
Bank Sta=5026.6,5030.6
Exp/Cntr=0.3,0.1

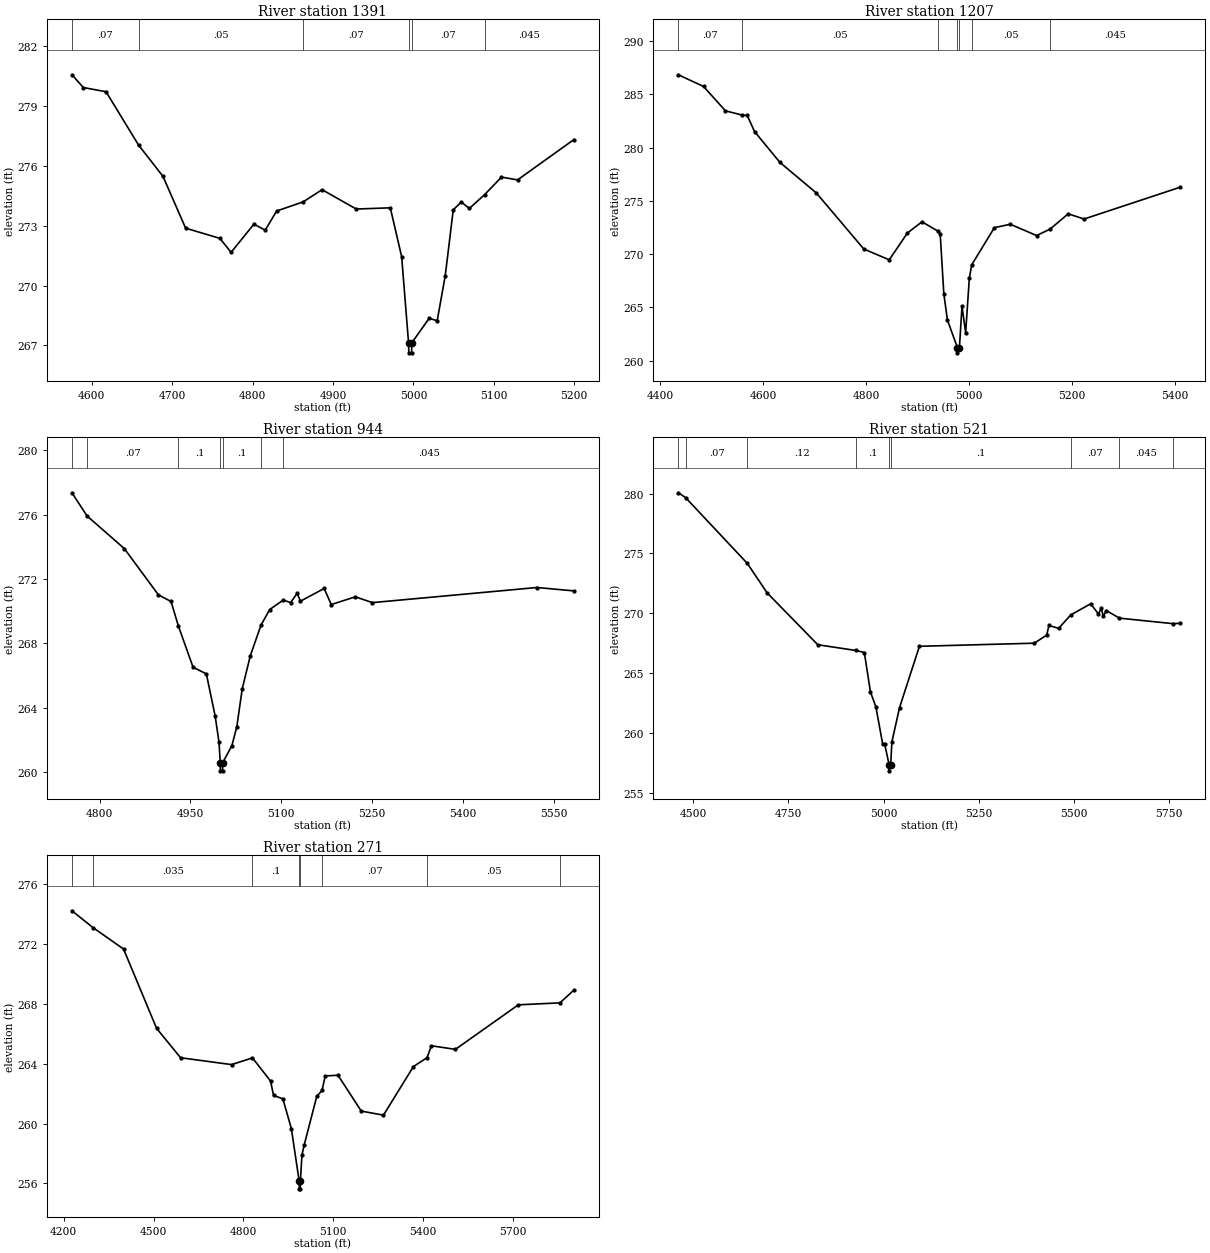
Type RM Length L Ch R = 1,1391,184,184,184
BEGIN DESCRIPTION:
Stream0789 3.0
END DESCRIPTION:
XS GIS Cut Line= 3
      2444625.01     13599024.99      2444325.00     13599325.00
      2444325.00     13599525.02
#Sta/Elev= 30
  4575.3  280.57  4589.5  279.93  4617.7  279.72  4658.1  277.05  4688.5  275.48
  4716.7  272.88  4759.2  272.37  4773.3  271.67  4801.6  273.08  4815.7  272.78
  4829.9  273.74  4863.0  274.20  4886.4  274.81  4928.9  273.84  4971.3  273.90
  4985.4  271.45  4994.0  267.13  4994.3  266.63  4997.8  266.63  4998.0  267.13
  5019.6  268.36  5029.6  268.24  5039.6  270.49  5049.6  273.80  5059.6  274.19
  5069.6  273.87  5088.6  274.56  5109.6  275.44  5129.6  275.30  5199.6  277.32
#Mann=6,-1,0
  4575.3    0.07       0  4658.1    0.05       0  4863.0    0.07       0
  4994.0    0.05       0  4998.0    0.07       0  5088.6   0.045       0
Bank Sta=4994,4998
Exp/Cntr=0.3,0.1

Type RM Length L Ch R = 1,1207,263,263,263
BEGIN DESCRIPTION:
H21054
END DESCRIPTION:
XS GIS Cut Line= 3
      2444575.63     13598826.52      2444175.09     13599232.54
      2444087.31     13599627.57
#Sta/Elev= 30
  4434.9  286.84  4483.8  285.74  4526.2  283.46  4559.2  283.05  4568.6  283.02
  4582.8  281.51  4632.2  278.61  4703.0  275.74  4794.9  270.49  4844.4  269.47
  4879.8  271.99  4908.1  273.04  4939.5  272.15  4943.4  271.94  4950.5  266.28
  4957.5  263.81  4976.8  261.24  4977.0  260.74  4980.8  261.24  4985.8  265.11
  4992.9  262.64  5000.0  267.73  5004.6  269.00  5048.7  272.49  5079.7  272.81
  5130.7  271.75  5156.8  272.35  5192.1  273.79  5222.9  273.30  5409.9  276.29
#Mann=7,-1,0
  4434.9    0.07       0  4559.2    0.05       0  4939.5     0.1       0
  4976.8    0.05       0  4980.8     0.1       0  5004.6    0.05       0
  5156.8   0.045       0
Bank Sta=4976.8,4980.8
Exp/Cntr=0.3,0.1

Type RM Length L Ch R = 1,944,423,423,423
BEGIN DESCRIPTION:
Stream0789 2.0
END DESCRIPTION:
XS GIS Cut Line= 3
      2444225.04     13598874.97      2444025.00     13599025.00
      2443774.31     13599546.53
#Sta/Elev= 30
  4754.3  277.37  4779.2  275.93  4840.8  273.90  4897.1  271.02  4917.9  270.61
  4930.1  269.08  4954.3  266.52  4976.2  266.11  4990.8  263.48  4997.1  261.86
  4999.2  260.58  4999.5  260.08  5003.0  260.08  5003.2  260.58  5018.4  261.65
  5026.5  262.82  5035.5  265.19  5048.7  267.22  5066.3  269.13  5080.8  270.11
  5103.2  270.70  5115.3  270.54  5126.1  271.12  5131.6  270.63  5170.8  271.42
  5182.4  270.42  5222.2  270.90  5250.4  270.54  5522.0  271.48  5583.0  271.27
#Mann=7,-1,0
  4754.3    0.05       0  4779.2    0.07       0  4930.1     0.1       0
  4999.2    0.05       0  5003.2     0.1       0  5066.3    0.05       0
  5103.2   0.045       0
Bank Sta=4999.2,5003.2
Exp/Cntr=0.3,0.1

Type RM Length L Ch R = 1,521,250,250,250
BEGIN DESCRIPTION:
Stream0789 1.0
END DESCRIPTION:
XS GIS Cut Line= 3
      2444357.61     13598595.14      2443825.00     13598675.00
      2443600.91     13599420.80
#Sta/Elev= 30
  4461.7  280.07  4480.4  279.67  4642.6  274.17  4694.3  271.72  4827.5  267.38
  4927.8  266.90  4949.7  266.73  4965.7  263.44  4980.0  262.19  4997.7  259.11
  5002.9  259.11  5014.8  257.35  5015.0  256.85  5018.8  257.35  5022.0  259.27
  5042.0  262.12  5094.2  267.25  5395.9  267.51  5428.4  268.19  5434.1  268.99
  5459.7  268.75  5491.5  269.87  5543.7  270.80  5564.1  269.95  5571.5  270.43
  5576.7  269.77  5585.0  270.23  5619.2  269.60  5760.2  269.14  5779.0  269.17
#Mann=9,-1,0
  4461.7    0.05       0  4480.4    0.07       0  4642.6    0.12       0
  4927.8     0.1       0  5014.8    0.05       0  5018.8     0.1       0
  5491.5    0.07       0  5619.2   0.045       0  5760.2    0.05       0
Bank Sta=5014.8,5018.8
Exp/Cntr=0.3,0.1

Type RM Length L Ch R = 1,271,0,0,0
BEGIN DESCRIPTION:
XS7731
END DESCRIPTION:
XS GIS Cut Line= 4
      2444427.05     13598386.81      2443746.53     13598414.58
      2443510.42     13598650.69      2443503.47     13599310.16
#Sta/Elev= 30
  4227.9  274.23  4297.8  273.11  4400.1  271.67  4510.2  266.37  4590.2  264.40
  4760.4  263.94  4830.2  264.39  4890.5  262.84  4900.5  261.88  4931.6  261.65
  4959.9  259.66  4986.1  256.13  4986.4  255.63  4989.9  255.63  4990.1  256.13
  4995.2  257.88  5002.3  258.53  5044.7  261.82  5062.2  262.21  5073.0  263.18
  5115.4  263.23  5193.2  260.83  5267.2  260.56  5367.2  263.81  5412.5  264.40
  5427.2  265.20  5507.2  264.96  5717.2  267.94  5855.9  268.07  5902.4  268.92
#Mann=8,-1,0
  4227.9    0.05       0  4297.8   0.035       0  4830.2     0.1       0
  4986.1    0.05       0  4990.1     0.1       0  5062.2    0.07       0
  5412.5    0.05       0  5855.9    0.07       0
Bank Sta=4986.1,4990.1
Exp/Cntr=0.3,0.1

Chan Stop Cuts=-1