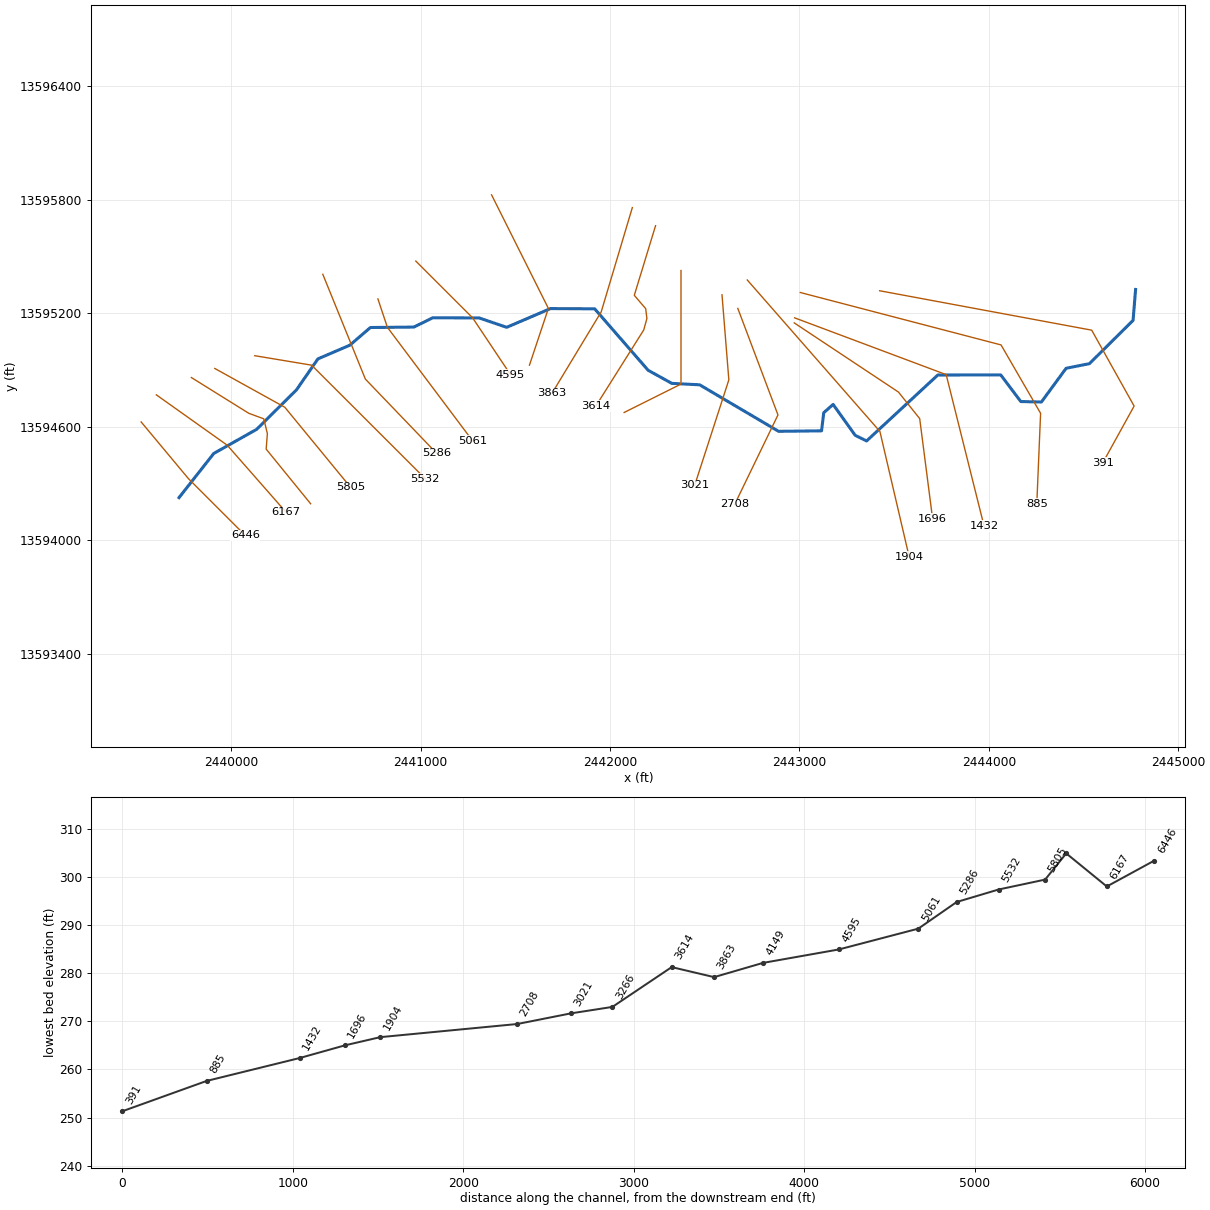
--- Stream0790.prj (project) ---

Proj Title=Stream0790 Base Level Engineering
Current Plan=p01
Default Exp/Contr=0.3,0.1
English Units
Geom File=g01
Flow File=f01
Plan File=p01
BEGIN DESCRIPTION:
Stream0790
END DESCRIPTION:

--- Stream0790.p01 (plan) ---

Plan Title=Multiple Run
Short Identifier=Multiple
Geom File=g01
Flow File=f01
Subcritical Flow
K Sum by GR= 0
Std Step Tol= 0.01
Critical Tol= 0.01
Num of Std Step Trials= 20
Max Error Tol= 0.3
Flow Tol Ratio= 0.001
Split Flow NTrial= 30
Split Flow Tol= 0.02
Split Flow Ratio= 0.02
Log Output Level= 0
Friction Slope Method= 1
Unsteady Friction Slope Method= 2
Unsteady Bridges Friction Slope Method= 1
Parabolic Critical Depth
Global Vel Dist=  1 , 1 , 1
Global Log Level= 0
CheckData=True
Encroach Param= -1, 0, 0, 0
BEGIN DESCRIPTION:
Multiple Run
END DESCRIPTION:

--- Stream0790.f01 (steady flow) ---

Flow Title=Multiple
Number of Profiles=7
Profile Names=10-year,25-year,50-year,1pct_min,100-year,1pct_plu,500-year
River Rch & RM= Stream0790,Reach-1,6446
     756    1244    1695    1119    2233    4455    3838
River Rch & RM= Stream0790,Reach-1,1696
     768    1266    1725    1139    2272    4533    3906
Boundary for River Rch & Prof#=Stream0790,Reach-1,1
Up Type=0
Dn Type=3
Dn Slope=0.005
Boundary for River Rch & Prof#=Stream0790,Reach-1,2
Up Type=0
Dn Type=3
Dn Slope=0.005
Boundary for River Rch & Prof#=Stream0790,Reach-1,3
Up Type=0
Dn Type=3
Dn Slope=0.005
Boundary for River Rch & Prof#=Stream0790,Reach-1,4
Up Type=0
Dn Type=3
Dn Slope=0.005
Boundary for River Rch & Prof#=Stream0790,Reach-1,5
Up Type=0
Dn Type=3
Dn Slope=0.005
Boundary for River Rch & Prof#=Stream0790,Reach-1,6
Up Type=0
Dn Type=3
Dn Slope=0.005
Boundary for River Rch & Prof#=Stream0790,Reach-1,7
Up Type=0
Dn Type=3
Dn Slope=0.005

--- Stream0790.g01 (geometry) ---

Geom Title=Existing Conditions

River Reach=Stream0790,Reach-1
Reach XY= 30
      2439725.00     13594225.00      2439908.33     13594458.35
      2440134.68     13594585.78      2440345.38     13594794.84
      2440458.29     13594958.37      2440627.29     13595030.85
      2440735.44     13595123.95      2440964.50     13595126.22
      2441064.81     13595175.45      2441309.78     13595174.48
      2441454.90     13595124.90      2441685.50     13595223.78
      2441919.15     13595222.94      2442201.48     13594897.99
      2442326.56     13594828.76      2442473.44     13594821.24
      2442890.16     13594575.39      2443117.03     13594577.94
      2443128.65     13594673.91      2443178.14     13594717.50
      2443294.63     13594554.31      2443354.77     13594524.50
      2443730.85     13594872.94      2444063.17     13594873.38
      2444168.81     13594732.75      2444277.67     13594730.29
      2444408.21     13594908.56      2444531.17     13594932.86
      2444761.64     13595161.68      2444775.00     13595325.00

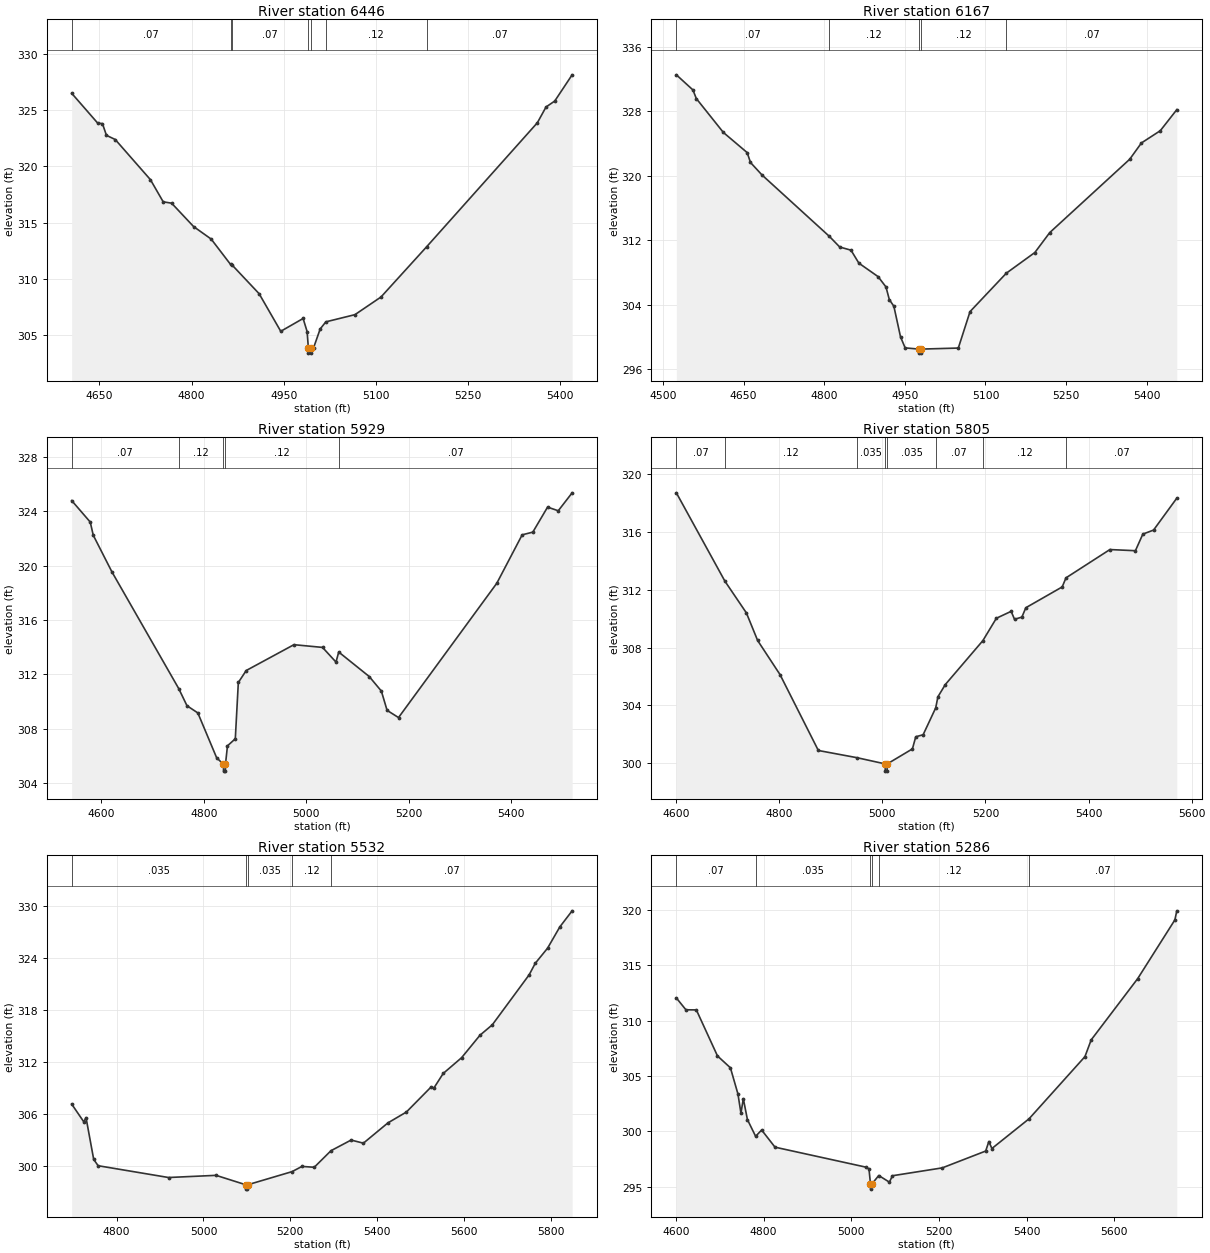
Type RM Length L Ch R = 1,6446,279,279,279
BEGIN DESCRIPTION:
Stream0790 12.0
END DESCRIPTION:
XS GIS Cut Line= 3
      2439525.00     13594624.99      2439775.00     13594325.00
      2440075.02     13594024.98
#Sta/Elev= 30
  4604.9  326.49  4647.2  323.84  4655.0  323.79  4661.5  322.75  4675.8  322.38
  4733.1  318.81  4753.9  316.84  4767.6  316.72  4803.4  314.64  4832.0  313.53
  4863.5  311.28  4865.6  311.25  4910.1  308.67  4945.3  305.33  4981.7  306.47
  4988.2  305.31  4990.2  303.89  4990.4  303.39  4993.9  303.39  4994.2  303.89
  4998.9  303.89  5009.5  305.54  5018.7  306.17  5066.1  306.81  5108.5  308.38
  5182.9  312.85  5363.1  323.87  5377.2  325.27  5391.4  325.80  5419.7  328.13
#Mann=7,-1,0
  4604.9    0.07       0  4863.5    0.12       0  4865.6    0.07       0
  4990.2    0.05       0  4994.2    0.07       0  5018.7    0.12       0
  5182.9    0.07       0
Bank Sta=4990.2,4994.2
Exp/Cntr=0.3,0.1

Type RM Length L Ch R = 1,6167,238,238,238
BEGIN DESCRIPTION:
Stream0790 11.0
END DESCRIPTION:
XS GIS Cut Line= 3
      2439605.17     13594768.20      2439979.30     13594502.15
      2440290.56     13594147.31
#Sta/Elev= 30
  4524.9  332.53  4555.8  330.65  4562.0  329.59  4612.4  325.38  4656.7  322.88
  4662.8  321.66  4684.2  320.11  4809.3  312.51  4828.9  311.17  4849.8  310.78
  4864.5  309.17  4900.2  307.50  4914.9  306.22  4921.1  304.66  4929.6  303.82
  4942.0  300.02  4950.6  298.66  4976.3  298.51  4976.5  298.01  4980.0  298.01
  4980.3  298.51  5049.5  298.64  5071.3  303.16  5138.9  307.93  5191.9  310.49
  5219.6  312.96  5368.4  322.06  5390.2  324.08  5425.3  325.60  5456.0  328.21
#Mann=5,-1,0
  4524.9    0.07       0  4809.3    0.12       0  4976.3    0.05       0
  4980.3    0.12       0  5138.9    0.07       0
Bank Sta=4976.3,4980.3
Exp/Cntr=0.3,0.1

Type RM Length L Ch R = 1,5929,124,124,124
BEGIN DESCRIPTION:
Stream0790 11.0a
END DESCRIPTION:
XS GIS Cut Line= 6
      2439790.16     13594859.65      2440093.62     13594670.51
      2440172.61     13594641.41      2440191.40     13594562.94
      2440185.08     13594481.36      2440419.95     13594192.45
#Sta/Elev= 30
  4542.4  324.78  4578.6  323.20  4584.5  322.23  4621.0  319.53  4751.3  310.95
  4767.4  309.69  4788.6  309.16  4825.2  305.87  4838.5  305.38  4838.8  304.88
  4842.3  304.88  4842.5  305.38  4846.4  306.74  4861.7  307.26  4867.6  311.40
  4883.0  312.28  4976.1  314.18  5031.9  313.98  5058.2  312.90  5063.5  313.64
  5123.0  311.84  5146.7  310.77  5157.9  309.35  5180.2  308.82  5372.0  318.70
  5421.5  322.26  5442.3  322.46  5471.1  324.30  5491.9  324.03  5519.0  325.35
#Mann=5,-1,0
  4542.4    0.07       0  4751.3    0.12       0  4838.5    0.05       0
  4842.5    0.12       0  5063.5    0.07       0
Bank Sta=4838.5,4842.5
Exp/Cntr=0.3,0.1

Type RM Length L Ch R = 1,5805,273,273,273
BEGIN DESCRIPTION:
H21062
END DESCRIPTION:
XS GIS Cut Line= 3
      2439914.00     13594907.48      2440283.34     13594702.74
      2440631.46     13594278.60
#Sta/Elev= 30
  4600.2  318.72  4694.4  312.60  4736.1  310.40  4757.9  308.49  4801.3  306.13
  4875.7  300.87  4950.8  300.37  5005.4  299.94  5005.6  299.44  5009.1  299.44
  5009.4  299.94  5058.2  300.98  5064.7  301.82  5079.0  301.96  5103.4  303.82
  5107.7  304.59  5122.1  305.44  5194.9  308.48  5221.1  310.03  5249.8  310.51
  5256.3  309.96  5270.6  310.11  5278.3  310.76  5348.8  312.20  5356.2  312.83
  5441.4  314.79  5490.9  314.71  5505.3  315.86  5526.1  316.14  5571.2  318.35
#Mann=8,-1,0
  4600.2    0.07       0  4694.4    0.12       0  4950.8   0.035       0
  5005.4   0.035       0  5009.4   0.035       0  5103.4    0.07       0
  5194.9    0.12       0  5356.2    0.07       0
Bank Sta=5005.4,5009.4
Exp/Cntr=0.3,0.1

Type RM Length L Ch R = 1,5532,246,246,246
BEGIN DESCRIPTION:
Stream0790 10.0
END DESCRIPTION:
XS GIS Cut Line= 3
      2440124.97     13594975.00      2440425.00     13594925.00
      2441025.00     13594325.00
#Sta/Elev= 30
  4696.4  307.19  4724.3  305.14  4729.4  305.63  4747.1  300.81  4757.3  300.08
  4919.5  298.72  5028.9  298.97  5097.6  297.88  5097.8  297.38  5101.3  297.38
  5101.6  297.88  5204.1  299.40  5226.8  300.00  5255.1  299.90  5293.6  301.81
  5340.0  303.04  5368.3  302.68  5424.8  305.02  5467.3  306.27  5523.8  309.14
  5530.9  309.06  5552.1  310.72  5594.5  312.54  5637.0  315.14  5665.2  316.33
  5750.1  322.10  5764.2  323.43  5792.5  325.17  5820.8  327.63  5849.1  329.48
#Mann=5,-1,0
  4696.4   0.035       0  5097.6   0.035       0  5101.6   0.035       0
  5204.1    0.12       0  5293.6    0.07       0
Bank Sta=5097.6,5101.6
Exp/Cntr=0.3,0.1

Type RM Length L Ch R = 1,5286,225,225,225
BEGIN DESCRIPTION:
H21061
END DESCRIPTION:
XS GIS Cut Line= 3
      2440484.06     13595405.20      2440708.84     13594851.27
      2441085.13     13594458.97
#Sta/Elev= 30
  4600.9  312.05  4622.7  310.98  4646.5  310.97  4694.7  306.81  4724.2  305.74
  4741.4  303.37  4748.2  301.64  4753.6  302.95  4763.0  301.06  4781.7  299.55
  4795.4  300.12  4825.9  298.57  5032.8  296.77  5040.2  296.61  5043.6  295.28
  5043.9  294.78  5047.6  295.28  5062.5  296.01  5086.8  295.41  5093.8  295.99
  5207.4  296.70  5306.4  298.22  5313.6  299.08  5320.6  298.45  5405.5  301.14
  5532.8  306.75  5547.0  308.26  5653.0  313.79  5737.9  319.10  5742.3  319.92
#Mann=6,-1,0
  4600.9    0.07       0  4781.7   0.035       0  5043.6   0.035       0
  5047.6   0.035       0  5062.5    0.12       0  5405.5    0.07       0
Bank Sta=5043.6,5047.6
Exp/Cntr=0.3,0.1

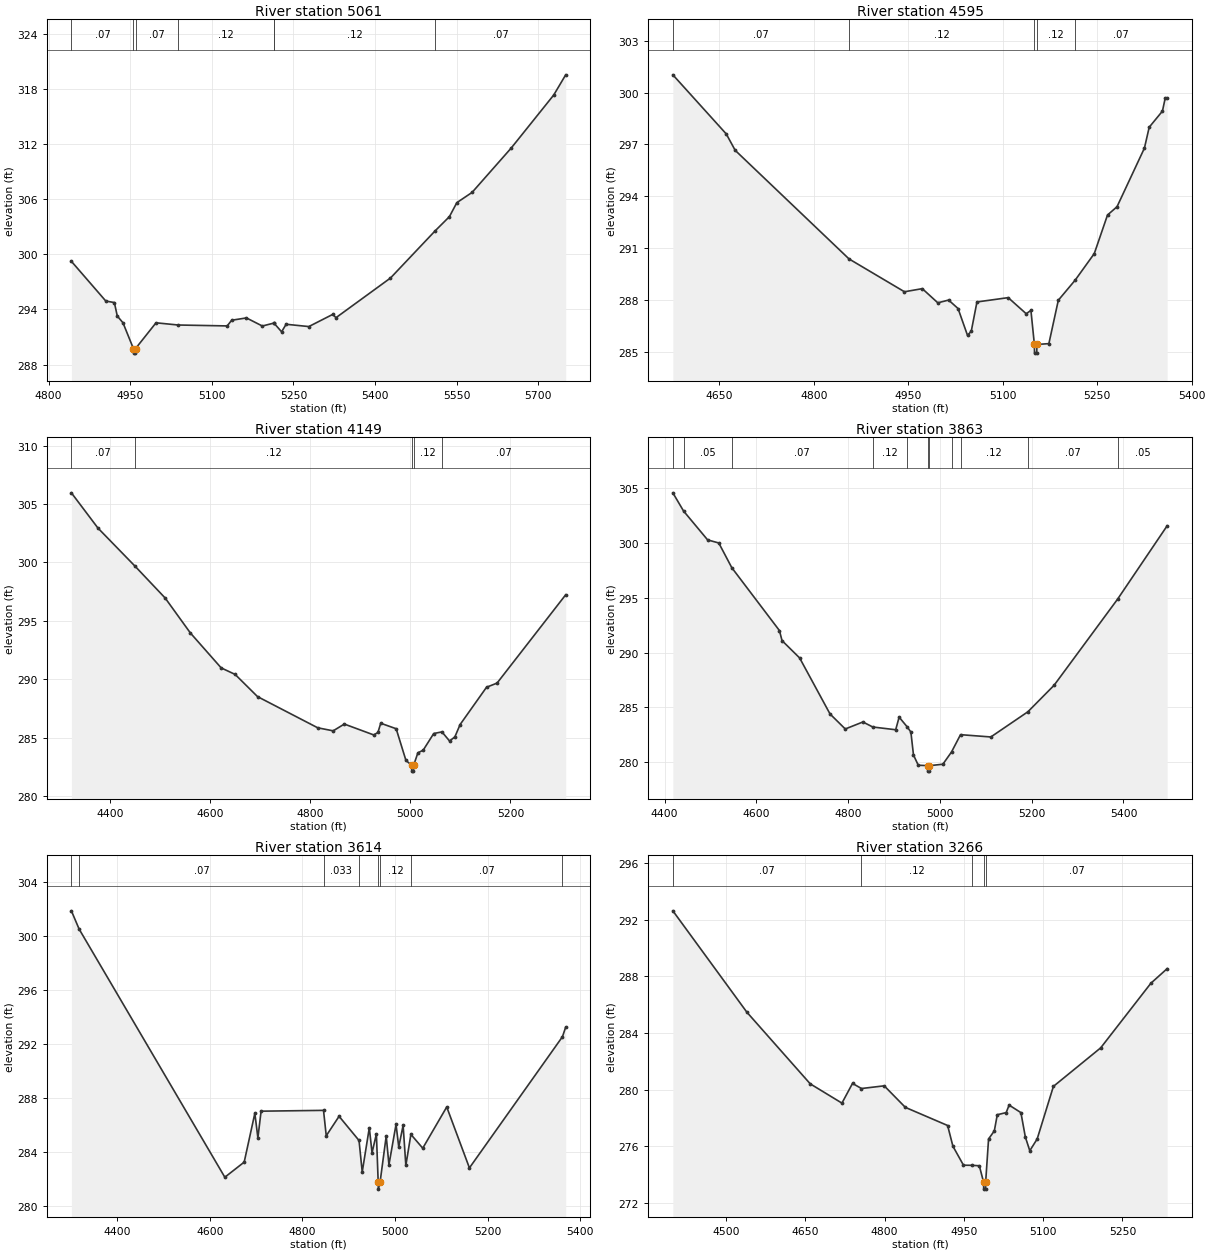
Type RM Length L Ch R = 1,5061,466,466,466
BEGIN DESCRIPTION:
Stream0790 9.0
END DESCRIPTION:
XS GIS Cut Line= 3
      2440775.01     13595274.98      2440825.00     13595125.00
      2441275.01     13594524.99
#Sta/Elev= 30
  4842.0  299.24  4905.2  294.92  4921.0  294.75  4926.3  293.29  4936.8  292.55
  4955.9  289.75  4956.2  289.25  4959.7  289.25  4959.9  289.75  4997.5  292.55
  5038.0  292.31  5128.2  292.21  5136.5  292.83  5163.6  293.08  5192.8  292.20
  5214.2  292.52  5214.4  292.50  5228.2  291.57  5236.5  292.39  5278.2  292.14
  5322.0  293.46  5328.2  293.11  5428.2  297.42  5510.2  302.55  5536.5  304.10
  5550.1  305.62  5578.2  306.74  5650.1  311.57  5728.2  317.34  5750.1  319.53
#Mann=7,-1,0
  4842.0    0.07       0  4955.9    0.05       0  4959.9    0.07       0
  5038.0    0.12       0  5214.2    0.07       0  5214.4    0.12       0
  5510.2    0.07       0
Bank Sta=4955.9,4959.9
Exp/Cntr=0.3,0.1

Type RM Length L Ch R = 1,4595,446,446,446
BEGIN DESCRIPTION:
Stream0790 8.0
END DESCRIPTION:
XS GIS Cut Line= 3
      2440975.02     13595474.98      2441275.00     13595175.00
      2441475.00     13594875.00
#Sta/Elev= 30
  4576.3  301.03  4661.1  297.61  4675.3  296.66  4856.0  290.38  4944.0  288.48
  4972.3  288.66  4997.0  287.84  5014.1  288.00  5029.1  287.51  5044.1  285.96
  5050.1  286.20  5059.1  287.89  5108.7  288.14  5137.3  287.21  5144.8  287.40
  5150.3  285.43  5150.5  284.93  5154.0  284.93  5154.3  285.43  5173.3  285.48
  5188.3  287.99  5215.0  289.15  5245.4  290.69  5266.4  292.92  5281.5  293.40
  5325.0  296.79  5332.6  298.00  5353.6  298.93  5358.1  299.70  5361.1  299.70
#Mann=5,-1,0
  4576.3    0.07       0  4856.0    0.12       0  5150.3    0.05       0
  5154.3    0.12       0  5215.0    0.07       0
Bank Sta=5150.3,5154.3
Exp/Cntr=0.3,0.1

Type RM Length L Ch R = 1,4149,286,286,286
BEGIN DESCRIPTION:
Stream0790 7.0
END DESCRIPTION:
XS GIS Cut Line= 3
      2441375.00     13595825.00      2441675.00     13595225.00
      2441575.01     13594925.04
#Sta/Elev= 30
  4323.4  305.96  4376.5  302.94  4450.7  299.67  4510.7  296.95  4561.0  293.96
  4622.5  290.97  4650.4  290.41  4695.1  288.51  4815.3  285.84  4846.1  285.58
  4868.4  286.16  4927.1  285.23  4935.5  285.44  4941.1  286.23  4971.9  285.76
  4991.4  283.05  5002.8  282.63  5003.0  282.13  5006.5  282.13  5006.8  282.63
  5015.3  283.70  5025.8  283.92  5046.9  285.35  5063.3  285.49  5078.5  284.71
  5089.1  285.06  5099.6  286.12  5152.3  289.31  5173.4  289.67  5310.4  297.23
#Mann=5,-1,0
  4323.4    0.07       0  4450.7    0.12       0  5002.8    0.05       0
  5006.8    0.12       0  5063.3    0.07       0
Bank Sta=5002.8,5006.8
Exp/Cntr=0.3,0.1

Type RM Length L Ch R = 1,3863,249,249,249
BEGIN DESCRIPTION:
Stream0790 6.0
END DESCRIPTION:
XS GIS Cut Line= 3
      2442118.11     13595757.60      2441953.90     13595206.77
      2441694.09     13594776.51
#Sta/Elev= 30
  4417.9  304.60  4441.2  302.94  4493.7  300.30  4518.0  300.02  4546.4  297.76
  4650.2  292.02  4655.9  291.10  4694.2  289.52  4760.5  284.40  4793.7  283.03
  4832.1  283.67  4853.7  283.21  4903.6  282.96  4911.1  284.11  4928.3  283.24
  4936.7  282.75  4942.4  280.65  4952.8  279.72  4973.1  279.68  4973.4  279.18
  4976.9  279.18  4977.1  279.68  5006.4  279.81  5025.3  280.93  5044.9  282.51
  5111.0  282.30  5191.7  284.60  5248.8  287.02  5387.1  294.88  5495.3  301.59
#Mann=11,-1,0
  4417.9   0.035       0  4441.2    0.05       0  4546.4    0.07       0
  4853.7    0.12       0  4928.3   0.033       0  4973.1   0.033       0
  4977.1   0.033       0  5025.3    0.07       0  5044.9    0.12       0
  5191.7    0.07       0  5387.1    0.05       0
Bank Sta=4973.1,4977.1
Exp/Cntr=0.3,0.1

Type RM Length L Ch R = 1,3614,348,348,348
BEGIN DESCRIPTION:
Stream0790 6.0a
END DESCRIPTION:
XS GIS Cut Line= 6
      2442240.75     13595662.00      2442128.50     13595294.06
      2442188.77     13595223.39      2442195.01     13595171.43
      2442178.38     13595111.15      2441925.48     13594709.00
#Sta/Elev= 30
  4301.2  301.86  4317.9  300.51  4632.6  282.14  4674.4  283.26  4697.4  286.87
  4704.0  285.05  4710.9  287.03  4845.7  287.09  4851.6  285.21  4879.3  286.65
  4922.4  284.86  4929.3  282.53  4944.6  285.80  4950.5  283.95  4959.9  285.35
  4963.8  281.76  4964.1  281.26  4967.8  281.76  4981.1  285.19  4987.0  283.06
  5002.3  286.05  5008.2  284.38  5017.6  285.98  5023.5  283.01  5034.4  285.31
  5060.0  284.29  5111.8  287.34  5160.8  282.83  5361.7  292.54  5368.7  293.25
#Mann=8,-1,0
  4301.2   0.035       0  4317.9    0.07       0  4845.7   0.033       0
  4922.4    0.12       0  4963.8    0.05       0  4967.8    0.12       0
  5034.4    0.07       0  5361.7    0.05       0
Bank Sta=4963.8,4967.8
Exp/Cntr=0.3,0.1

Type RM Length L Ch R = 1,3266,245,245,245
BEGIN DESCRIPTION:
Stream0790 5.0
END DESCRIPTION:
XS GIS Cut Line= 3
      2442375.00     13595425.04      2442375.00     13594825.00
      2442074.96     13594674.98
#Sta/Elev= 30
  4399.2  292.63  4539.2  285.48  4659.2  280.42  4719.2  279.06  4739.2  280.45
  4756.2  280.09  4799.2  280.28  4839.2  278.76  4919.2  277.48  4929.2  276.02
  4949.2  274.68  4964.6  274.67  4979.2  274.64  4987.2  273.49  4987.5  272.99
  4991.0  272.99  4991.2  273.49  4996.7  276.53  5007.6  277.10  5013.2  278.24
  5030.0  278.39  5035.6  278.92  5057.9  278.39  5066.3  276.67  5074.7  275.70
  5088.7  276.53  5119.4  280.24  5208.9  282.96  5303.9  287.52  5334.7  288.55
#Mann=5,-1,0
  4399.2    0.07       0  4756.2    0.12       0  4964.6    0.07       0
  4987.2    0.05       0  4991.2    0.07       0
Bank Sta=4987.2,4991.2
Exp/Cntr=0.3,0.1

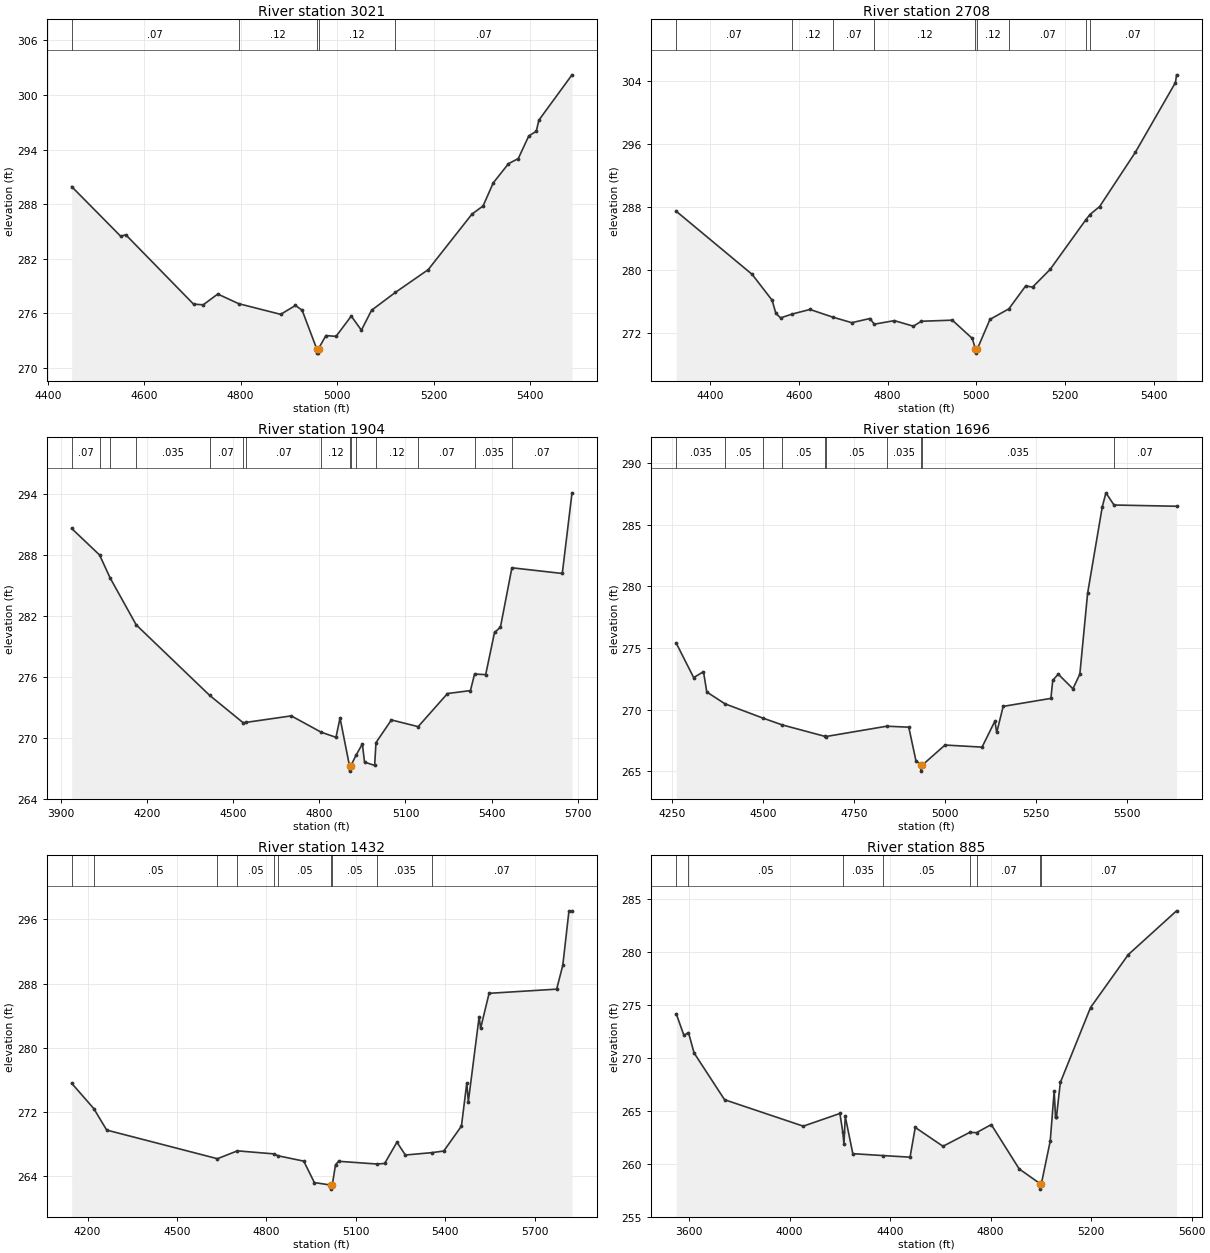
Type RM Length L Ch R = 1,3021,313,313,313
BEGIN DESCRIPTION:
H21060
END DESCRIPTION:
XS GIS Cut Line= 3
      2442591.50     13595296.83      2442627.63     13594847.26
      2442447.12     13594289.67
#Sta/Elev= 30
  4449.7  289.93  4551.3  284.48  4561.9  284.64  4702.3  277.02  4722.4  276.95
  4752.5  278.13  4795.9  277.07  4882.9  275.90  4913.6  276.88  4927.4  276.35
  4957.4  272.14  4957.7  271.64  4961.2  271.64  4961.4  272.14  4976.7  273.57
  4997.7  273.48  5029.2  275.71  5050.2  274.16  5071.3  276.35  5120.4  278.30
  5188.7  280.81  5279.4  286.91  5302.5  287.81  5323.5  290.34  5355.1  292.45
  5375.4  293.01  5397.1  295.49  5412.7  296.01  5418.1  297.23  5486.8  302.21
#Mann=5,-1,0
  4449.7    0.07       0  4795.9    0.12       0  4957.4    0.05       0
  4961.4    0.12       0  5120.4    0.07       0
Bank Sta=4957.4,4961.4
Exp/Cntr=0.3,0.1

Type RM Length L Ch R = 1,2708,804,804,804
BEGIN DESCRIPTION:
Stream0790 4.0
END DESCRIPTION:
XS GIS Cut Line= 3
      2442674.99     13595225.02      2442886.98     13594661.98
      2442658.28     13594188.99
#Sta/Elev= 30
  4323.9  287.47  4494.9  279.45  4539.9  276.16  4548.3  274.50  4559.0  273.92
  4585.3  274.41  4625.2  274.99  4676.2  274.02  4719.3  273.31  4760.2  273.84
  4770.0  273.12  4815.3  273.57  4858.2  272.86  4875.8  273.49  4945.7  273.63
  4990.9  271.30  4997.9  269.94  4998.2  269.44  5001.9  269.94  5030.6  273.73
  5073.2  275.07  5111.0  277.98  5126.5  277.83  5166.1  280.08  5246.5  286.39
  5255.7  287.05  5277.6  288.07  5358.0  294.96  5448.4  303.83  5450.9  304.81
#Mann=9,-1,0
  4323.9    0.07       0  4585.3    0.12       0  4676.2    0.07       0
  4770.0    0.12       0  4997.9    0.05       0  5001.9    0.12       0
  5073.2    0.07       0  5246.5    0.12       0  5255.7    0.07       0
Bank Sta=4997.9,5001.9
Exp/Cntr=0.3,0.1

Type RM Length L Ch R = 1,1904,208,208,208
BEGIN DESCRIPTION:
Stream0790 3.0
END DESCRIPTION:
XS GIS Cut Line= 3
      2442725.02     13595374.97      2443425.00     13594575.00
      2443579.69     13593911.98
#Sta/Elev= 30
  3936.7  290.60  4033.9  287.99  4070.7  285.73  4161.6  281.11  4417.1  274.18
  4534.0  271.48  4544.8  271.51  4702.1  272.15  4806.4  270.54  4857.8  270.04
  4872.0  271.94  4905.1  267.21  4905.4  266.71  4909.1  267.21  4928.0  268.29
  4949.8  269.38  4957.4  267.60  4992.6  267.27  4997.3  269.52  5051.0  271.75
  5144.3  271.09  5246.5  274.35  5326.5  274.64  5340.9  276.27  5379.6  276.21
  5410.4  280.36  5431.0  280.88  5471.0  286.73  5646.6  286.17  5680.5  294.11
#Mann=15,-1,0
  3936.7    0.07       0  4033.9   0.035       0  4070.7    0.07       0
  4161.6   0.035       0  4417.1    0.07       0  4534.0   0.035       0
  4544.8    0.07       0  4806.4    0.12       0  4905.1    0.05       0
  4909.1    0.12       0  4928.0    0.07       0  4997.3    0.12       0
  5144.3    0.07       0  5340.9   0.035       0  5471.0    0.07       0
Bank Sta=4905.1,4909.1
Exp/Cntr=0.3,0.1

Type RM Length L Ch R = 1,1696,264,264,264
BEGIN DESCRIPTION:
H21059
END DESCRIPTION:
XS GIS Cut Line= 4
      2442972.87     13595148.31      2443522.79     13594783.03
      2443635.19     13594642.53      2443703.44     13594112.62
#Sta/Elev= 30
  4261.4  275.40  4309.3  272.60  4336.3  273.08  4345.3  271.43  4395.2  270.47
  4498.5  269.32  4552.0  268.76  4669.2  267.83  4672.4  267.81  4839.9  268.65
  4900.2  268.57  4919.9  265.84  4933.7  265.50  4933.9  265.00  4937.7  265.50
  4999.7  267.12  5101.5  266.95  5136.7  269.06  5141.8  268.14  5159.5  270.26
  5290.6  270.91  5295.7  272.38  5310.8  272.88  5351.1  271.69  5370.1  272.88
  5391.4  279.44  5431.7  286.47  5441.8  287.61  5463.9  286.62  5635.8  286.52
#Mann=10,-1,0
  4261.4   0.035       0  4395.2    0.05       0  4498.5   0.035       0
  4552.0    0.05       0  4669.2   0.035       0  4672.4    0.05       0
  4839.9   0.035       0  4933.7   0.035       0  4937.7   0.035       0
  5463.9    0.07       0
Bank Sta=4933.7,4937.7
Exp/Cntr=0.3,0.1

Type RM Length L Ch R = 1,1432,547,547,547
BEGIN DESCRIPTION:
Stream0790 2.0
END DESCRIPTION:
XS GIS Cut Line= 3
      2442974.96     13595175.02      2443775.00     13594875.00
      2443975.01     13594074.97
#Sta/Elev= 30
  4146.8  275.57  4220.9  272.42  4264.3  269.74  4635.9  266.17  4703.0  267.15
  4826.0  266.77  4840.0  266.53  4925.6  265.87  4961.2  263.20  5017.3  262.88
  5017.5  262.38  5021.3  262.88  5032.2  265.42  5042.5  265.85  5170.9  265.51
  5197.1  265.58  5238.3  268.23  5266.7  266.63  5356.3  266.93  5395.5  267.13
  5454.8  270.23  5472.8  275.61  5478.0  273.28  5514.1  283.84  5519.2  282.43
  5547.6  286.78  5774.3  287.30  5794.9  290.26  5815.6  297.03  5825.9  297.06
#Mann=10,-1,0
  4146.8   0.035       0  4220.9    0.05       0  4635.9   0.035       0
  4703.0    0.05       0  4826.0   0.035       0  4840.0    0.05       0
  5017.3    0.05       0  5021.3    0.05       0  5170.9   0.035       0
  5356.3    0.07       0
Bank Sta=5017.3,5021.3
Exp/Cntr=0.3,0.1

Type RM Length L Ch R = 1,885,494,494,494
BEGIN DESCRIPTION:
H21058
END DESCRIPTION:
XS GIS Cut Line= 4
      2443004.93     13595308.90      2444064.71     13595031.91
      2444273.45     13594670.63      2444253.38     13594192.97
#Sta/Elev= 30
  3549.3  274.18  3579.8  272.15  3598.1  272.40  3620.3  270.48  3741.6  266.06
  4054.8  263.56  4200.5  264.76  4212.0  262.99  4216.6  261.85  4221.8  264.48
  4251.9  260.96  4373.0  260.78  4479.6  260.63  4500.3  263.44  4610.7  261.66
  4716.7  262.97  4744.3  262.95  4802.8  263.71  4913.8  259.52  4998.0  258.11
  4998.2  257.61  5002.0  258.11  5037.3  262.15  5053.1  266.87  5058.5  264.39
  5061.9  264.39  5077.6  267.69  5197.7  274.77  5347.8  279.77  5540.0  283.91
#Mann=8,-1,0
  3549.3    0.07       0  3598.1    0.05       0  4212.0   0.035       0
  4373.0    0.05       0  4716.7   0.035       0  4744.3    0.07       0
  4998.0    0.05       0  5002.0    0.07       0
Bank Sta=4998,5002
Exp/Cntr=0.3,0.1

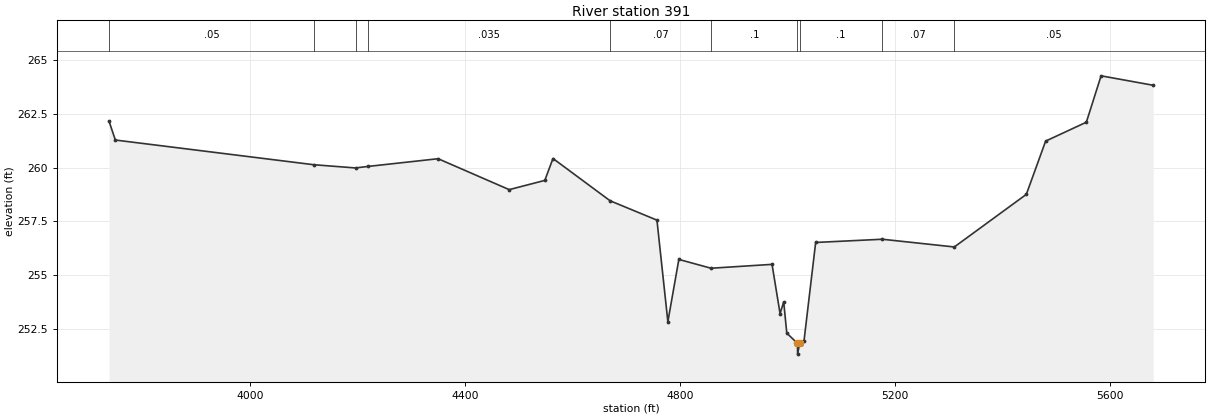
Type RM Length L Ch R = 1,391,0,0,0
BEGIN DESCRIPTION:
Stream0790 1.0
END DESCRIPTION:
XS GIS Cut Line= 4
      2443423.41     13595318.23      2444543.23     13595109.90
      2444767.19     13594708.85      2444601.43     13594408.42
#Sta/Elev= 30
  3738.4  262.17  3750.2  261.29  4119.1  260.14  4196.8  259.99  4219.7  260.06
  4350.3  260.42  4482.5  258.98  4548.7  259.41  4563.9  260.43  4670.2  258.46
  4757.2  257.56  4777.5  252.83  4797.9  255.73  4857.8  255.32  4971.2  255.50
  4986.1  253.21  4992.9  253.75  4998.6  252.30  5018.5  251.82  5018.7  251.32
  5022.5  251.82  5030.6  251.93  5052.3  256.52  5176.2  256.67  5310.1  256.31
  5444.0  258.76  5479.9  261.24  5555.6  262.12  5583.0  264.28  5679.9  263.84
#Mann=10,-1,0
  3738.4    0.05       0  4119.1   0.035       0  4196.8    0.05       0
  4219.7   0.035       0  4670.2    0.07       0  4857.8     0.1       0
  5018.5    0.05       0  5022.5     0.1       0  5176.2    0.07       0
  5310.1    0.05       0
Bank Sta=5018.5,5022.5
Exp/Cntr=0.3,0.1

Chan Stop Cuts=-1