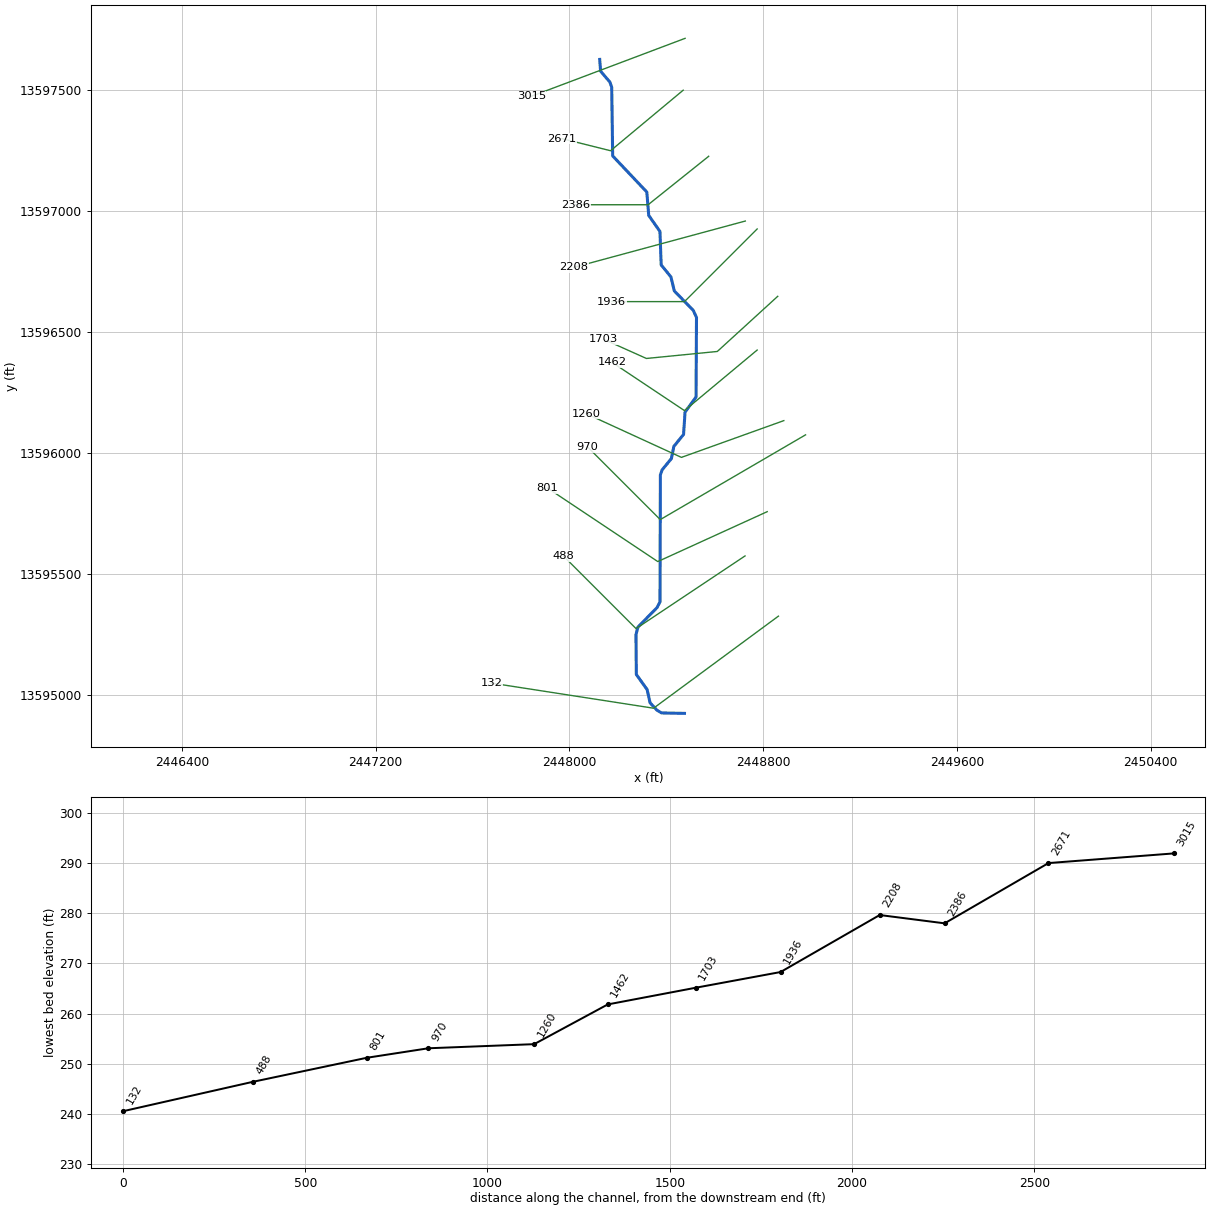
--- Stream0791.prj (project) ---

Proj Title=Stream0791 Base Level Engineering
Current Plan=p01
Default Exp/Contr=0.3,0.1
English Units
Geom File=g01
Flow File=f01
Plan File=p01
Y Axis Title=Elevation
X Axis Title(PF)=Main Channel Distance
X Axis Title(XS)=Station
BEGIN DESCRIPTION:
Stream0791
END DESCRIPTION:
DSS Export Rating Curves= 0
DSS Export Rating Curve Sorted= 0
DSS Export Volume Flow Curves= 0
DXF OffsetX= 0
DXF OffsetY= 0
DXF ScaleX= 1
DXF ScaleY= 10

--- Stream0791.p01 (plan) ---

Plan Title=Multiple Run
Short Identifier=Multiple
Geom File=g01
Flow File=f01
Subcritical Flow
K Sum by GR= 0
Std Step Tol= 0.01
Critical Tol= 0.01
Num of Std Step Trials= 20
Max Error Tol= 0.3
Flow Tol Ratio= 0.001
Split Flow NTrial= 30
Split Flow Tol= 0.02
Split Flow Ratio= 0.02
Log Output Level= 0
Friction Slope Method= 1
Unsteady Friction Slope Method= 2
Unsteady Bridges Friction Slope Method= 1
Parabolic Critical Depth
Global Vel Dist=  1 , 1 , 1
Global Log Level= 0
CheckData=True
Encroach Param= -1, 0, 0, 0
BEGIN DESCRIPTION:
Multiple Run
END DESCRIPTION:

--- Stream0791.f01 (steady flow) ---

Flow Title=Multiple
Number of Profiles=7
Profile Names=10-year,25-year,50-year,1pct_min,100-year,1pct_plu,500-year
River Rch & RM= Stream0791,Reach-1,3015
     302     470     617     395     787    1571    1265
Boundary for River Rch & Prof#=Stream0791,Reach-1,1
Up Type=0
Dn Type=3
Dn Slope=0.005
Boundary for River Rch & Prof#=Stream0791,Reach-1,2
Up Type=0
Dn Type=3
Dn Slope=0.005
Boundary for River Rch & Prof#=Stream0791,Reach-1,3
Up Type=0
Dn Type=3
Dn Slope=0.005
Boundary for River Rch & Prof#=Stream0791,Reach-1,4
Up Type=0
Dn Type=3
Dn Slope=0.005
Boundary for River Rch & Prof#=Stream0791,Reach-1,5
Up Type=0
Dn Type=3
Dn Slope=0.005
Boundary for River Rch & Prof#=Stream0791,Reach-1,6
Up Type=0
Dn Type=3
Dn Slope=0.005
Boundary for River Rch & Prof#=Stream0791,Reach-1,7
Up Type=0
Dn Type=3
Dn Slope=0.005

--- Stream0791.g01 (geometry) ---

Geom Title=Existing Conditions
Program Version=4.10

River Reach=Stream0791      ,Reach-1
Reach XY= 30
        2448125.       13597625.      2448128.65     13597576.51
      2448167.11     13597531.16      2448174.55     13597509.81
      2448178.54     13597226.46      2448319.48     13597077.43
      2448327.36     13596980.98      2448373.77     13596914.49
      2448378.76     13596776.56      2448418.86     13596727.17
      2448433.16     13596668.95       2448511.6     13596588.31
      2448524.61     13596559.84      2448522.74     13596230.94
      2448477.36     13596169.02      2448471.17     13596076.58
      2448431.11     13596027.18      2448420.81     13595976.74
      2448383.09     13595931.08      2448375.51     13595909.79
      2448373.94     13595385.44       2448361.6     13595361.69
      2448282.83     13595281.18      2448274.71     13595250.12
       2448276.2      13595085.5      2448320.77     13595023.22
      2448332.99     13594968.62      2448361.28     13594938.19
      2448380.55     13594926.77        2448475.       13594925.

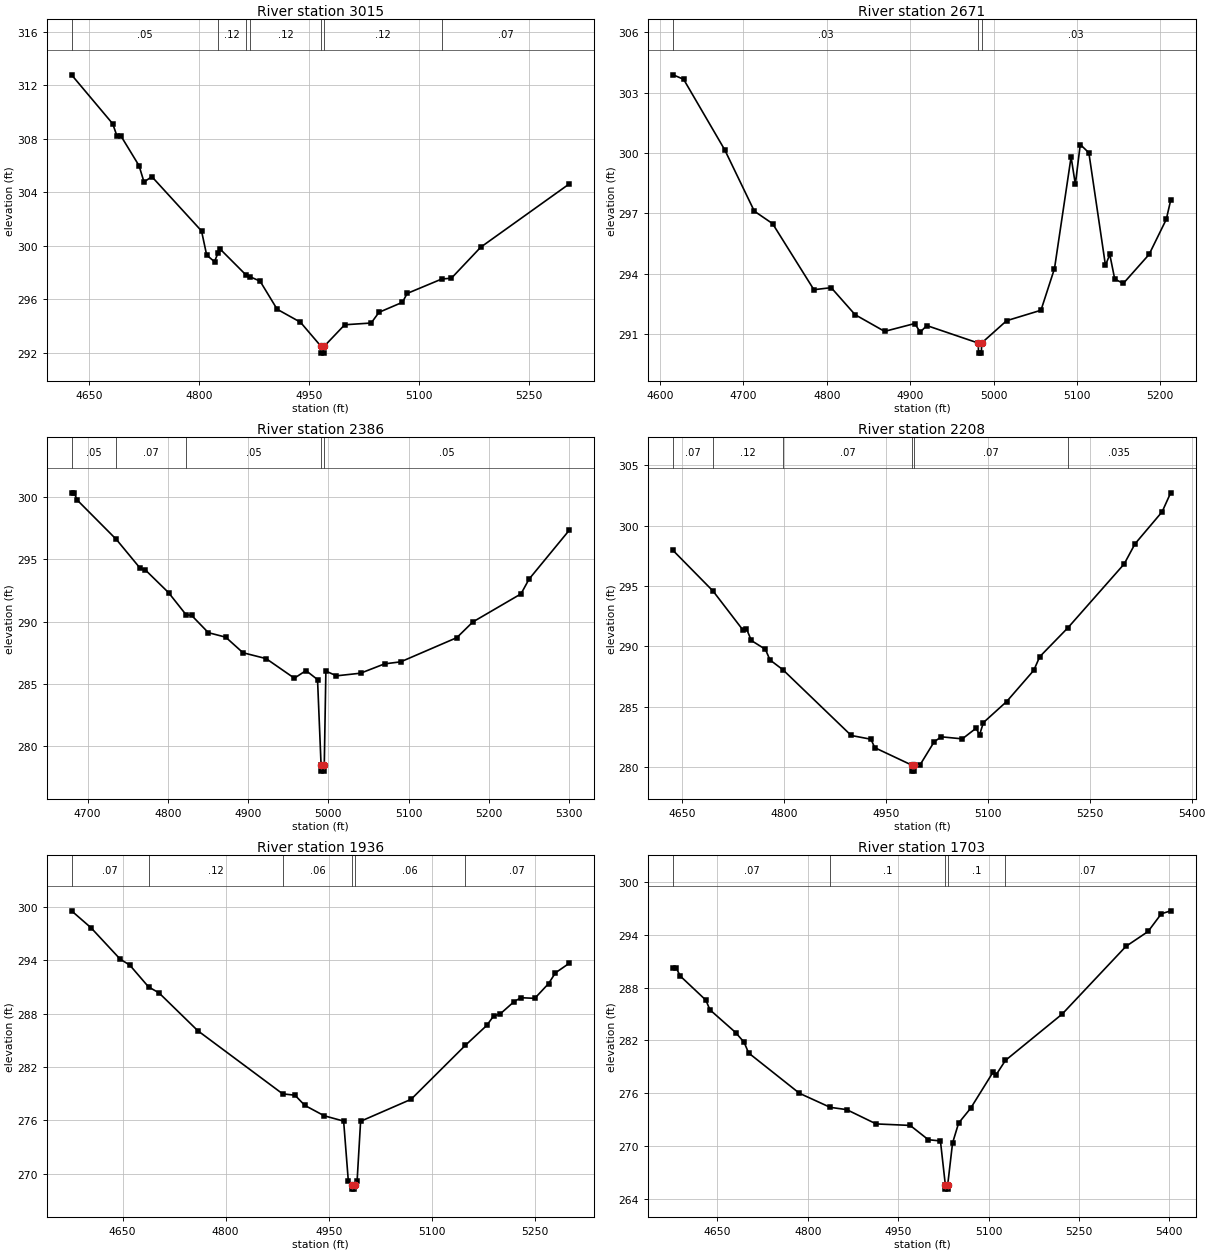
Type RM Length L Ch R = 1 ,3015    ,344,344,344
BEGIN DESCRIPTION:
XS7732
END DESCRIPTION:
XS GIS Cut Line= 2
      2448477.59     13597711.97      2447842.15     13597472.38
#Sta/Elev= 30
  4625.8  312.79    4682  309.13  4687.7  308.23  4693.1  308.23  4717.9     306
  4724.7  304.78  4735.4  305.18  4803.2  301.12  4810.2  299.32  4820.9  298.82
  4825.6  299.47    4828   299.8  4864.1  297.82  4869.3   297.7  4883.1  297.37
  4906.4  295.27  4938.2   294.3  4966.4  292.49  4966.6  291.99  4970.1  291.99
  4970.4  292.49  4998.6  294.11  5034.7  294.24  5045.4  295.04  5077.4  295.79
  5083.8  296.45  5131.1  297.53  5144.2  297.59  5184.3  299.91  5304.9  304.63
#Mann= 7 ,-1 , 0
  4625.8     .05       0  4825.6     .12       0  4864.1     .07       0
  4869.3     .12       0  4966.4     .05       0  4970.4     .12       0
  5131.1     .07       0
Bank Sta=4966.4,4970.4
XS Rating Curve= 0 ,0
Exp/Cntr=0.3,0.1

Type RM Length L Ch R = 1 ,2671    ,285,285,285
BEGIN DESCRIPTION:
Stream0791 6.0
END DESCRIPTION:
XS GIS Cut Line= 3
       2448469.8     13597497.92      2448169.79     13597247.92
      2447969.86      13597297.9
#Sta/Elev= 30
  4615.8  303.88  4628.4  303.66  4677.8  300.15  4713.2  297.11  4735.1  296.49
  4784.6  293.21  4805.4  293.31    4834  291.97  4869.4  291.14  4905.6  291.53
  4912.1   291.1  4919.9  291.43  4981.7  290.56    4982  290.06  4985.5  290.06
  4985.7  290.56  5015.7  291.67  5056.9  292.19  5073.1  294.26    5093   299.8
  5098.1  298.44    5104  300.42  5114.3  300.01  5134.2  294.42  5139.4  294.96
  5145.3  293.74  5155.6  293.52  5186.5  294.96  5207.1   296.7  5212.4  297.65
#Mann= 3 ,-1 , 0
  4615.8     .03       0  4981.7     .07       0  4985.7     .03       0
Bank Sta=4981.7,4985.7
XS Rating Curve= 0 ,0
Exp/Cntr=0.3,0.1

Type RM Length L Ch R = 1 ,2386    ,178,178,178
BEGIN DESCRIPTION:
Stream0791 5.0
END DESCRIPTION:
XS GIS Cut Line= 3
      2448575.01     13597225.01        2448325.       13597025.
      2448024.97       13597025.
#Sta/Elev= 30
  4679.9  300.33  4683.1  300.33  4687.1  299.74  4735.8  296.59  4765.6  294.27
    4772  294.14  4800.8  292.33  4822.6  290.56  4829.6   290.5  4850.4  289.12
    4872  288.76  4893.6  287.51  4922.4  287.04  4957.6  285.47  4972.1  286.08
  4986.5  285.36  4990.9  278.52  4991.1  278.02  4994.6  278.02  4994.9  278.52
  4996.9  286.04  5010.1  285.66  5040.1  285.87  5070.1  286.62  5090.1  286.78
  5160.1  288.72  5180.1  289.98  5240.1  292.23  5250.1  293.41  5300.1  297.32
#Mann= 5 ,-1 , 0
  4679.9     .05       0  4735.8     .07       0  4822.6     .05       0
  4990.9     .07       0  4994.9     .05       0
Bank Sta=4990.9,4994.9
XS Rating Curve= 0 ,0
Exp/Cntr=0.3,0.1

Type RM Length L Ch R = 1 ,2208    ,272,272,272
BEGIN DESCRIPTION:
H21064
END DESCRIPTION:
XS GIS Cut Line= 2
      2448726.17     13596957.68      2448018.87     13596766.42
#Sta/Elev= 30
  4636.4  297.94  4695.4  294.57  4739.2  291.36  4744.4  291.47  4751.6  290.49
  4772.3  289.76  4779.1  288.88  4798.1  288.07  4898.7  282.63  4927.7  282.32
  4933.4  281.62  4987.8  280.18  4988.1  279.68  4991.6  279.68  4991.8  280.18
  5000.2  280.21  5020.9  282.11  5031.3  282.52  5062.3  282.35  5082.5  283.23
  5087.7  282.69  5093.4   283.7  5127.6  285.44  5167.5  288.02  5176.3  289.15
  5217.9  291.55  5300.6  296.82  5316.6  298.49  5356.5  301.14  5369.1  302.71
#Mann= 6 ,-1 , 0
  4636.4     .07       0  4695.4     .12       0  4798.1     .07       0
  4987.8     .05       0  4991.8     .07       0  5217.9    .035       0
Bank Sta=4987.8,4991.8
XS Rating Curve= 0 ,0
Exp/Cntr=0.3,0.1

Type RM Length L Ch R = 1 ,1936    ,233,233,233
BEGIN DESCRIPTION:
Stream0791 4.0
END DESCRIPTION:
XS GIS Cut Line= 3
      2448774.98     13596924.98        2448475.       13596625.
      2448175.04       13596625.
#Sta/Elev= 30
  4575.8  299.55  4604.1  297.65  4646.5  294.13  4660.6  293.45  4687.8  291.01
  4703.1  290.33  4759.6  286.08  4883.1  278.99    4901  278.84  4915.2   277.7
  4943.5  276.53  4971.8  275.93 4978.67  269.15  4983.9  268.79  4984.1  268.29
  4987.6  268.29  4987.9  268.79 4991.43  269.24  4996.5  275.91    5070  278.38
  5148.8  284.43    5180  286.67    5190  287.73    5200  287.99    5220  289.36
    5230  289.79    5250  289.72    5270  291.37    5280  292.58    5300  293.65
#Mann= 6 ,-1 , 0
  4575.8     .07       0  4687.8     .12       0  4883.1     .06       0
  4983.9     .07       0  4987.9     .06       0  5148.8     .07       0
Bank Sta=4983.9,4987.9
XS Rating Curve= 0 ,0
Exp/Cntr=0.3,0.1

Type RM Length L Ch R = 1 ,1703    ,241,241,241
BEGIN DESCRIPTION:
H21063
END DESCRIPTION:
XS GIS Cut Line= 4
      2448859.97      13596646.9      2448610.56     13596419.18
      2448317.81     13596390.26      2448140.75     13596469.76
#Sta/Elev= 30
  4576.3  290.22  4581.4  290.22  4588.2   289.3  4630.7  286.57  4637.5  285.47
  4680.1   282.9  4694.2  281.79  4701.7  280.58  4786.1  276.01  4837.1  274.42
  4864.5  274.16  4913.4  272.54  4969.9  272.37    5000  270.75  5020.1  270.61
  5028.2  265.65  5028.4  265.15  5031.9  265.15  5032.2  265.65  5040.2  270.37
  5050.3  272.64  5070.3  274.32  5107.3  278.39  5112.4  278.09    5128  279.74
  5222.2  284.99    5328  292.66  5364.8  294.35  5386.7  296.35  5402.3  296.69
#Mann= 5 ,-1 , 0
  4576.3     .07       0  4837.1      .1       0  5028.2     .05       0
  5032.2      .1       0    5128     .07       0
Bank Sta=5028.2,5032.2
XS Rating Curve= 0 ,0
Exp/Cntr=0.3,0.1

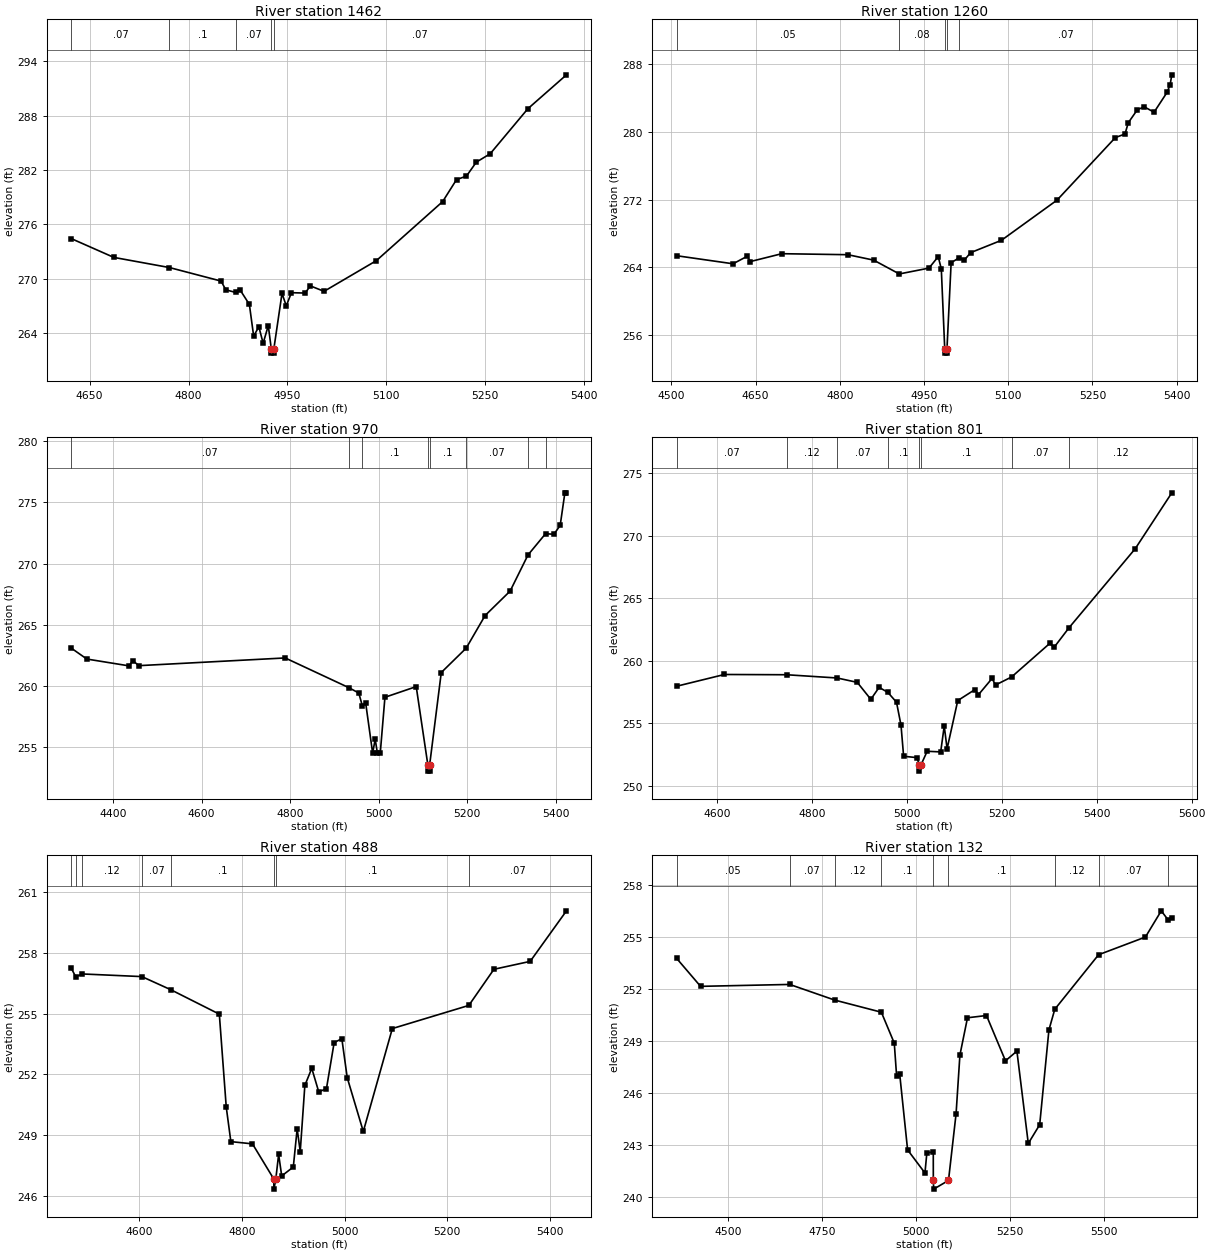
Type RM Length L Ch R = 1 ,1462    ,202,202,202
BEGIN DESCRIPTION:
Stream0791 3.0
END DESCRIPTION:
XS GIS Cut Line= 3
      2448775.02     13596425.02        2448475.       13596175.
        2448175.       13596375.
#Sta/Elev= 30
  4622.2  274.44  4686.7  272.37  4771.1  271.25  4849.4  269.76  4856.5   268.8
  4871.4  268.51    4878  268.81  4892.3  267.19  4898.8   263.7  4906.7  264.72
  4913.2  262.91    4921  264.85  4925.5  262.32  4925.7  261.82  4929.2  261.82
  4929.5  262.32  4941.8   268.4  4948.3  267.03  4956.1  268.48  4976.9  268.44
  4984.8  269.23  5005.6  268.63  5084.9  272.01  5185.5  278.52  5206.5  280.94
  5221.6  281.33  5236.6  282.87  5257.6  283.79  5314.7  288.75  5373.3  292.49
#Mann= 5 ,-1 , 0
  4622.2     .07       0  4771.1      .1       0  4871.4     .07       0
  4925.5     .05       0  4929.5     .07       0
Bank Sta=4925.5,4929.5
XS Rating Curve= 0 ,0
Exp/Cntr=0.3,0.1

Type RM Length L Ch R = 1 ,1260    ,290,290,290
BEGIN DESCRIPTION:
H21065
END DESCRIPTION:
XS GIS Cut Line= 3
      2448885.23     13596133.65      2448462.38     13595981.86
      2448069.24      13596162.2
#Sta/Elev= 30
  4509.5  265.37  4609.9  264.42  4635.3  265.31  4640.6  264.68  4696.8  265.61
  4814.4  265.49  4860.4  264.85    4906  263.22  4958.8  263.91  4975.3  265.26
  4980.8  263.82  4986.9  254.38  4987.1  253.88  4990.6  253.88  4990.9  254.38
  4998.3  264.54    5013  265.15  5021.3  264.81  5032.9  265.73  5087.9  267.19
  5186.9  271.93  5290.8  279.31  5307.9  279.73  5313.8  281.06    5330   282.6
  5342.3  282.93  5359.7   282.3  5382.7  284.63  5388.2  285.52  5391.3  286.71
#Mann= 5 ,-1 , 0
  4509.5     .05       0    4906     .08       0  4986.9     .07       0
  4990.9     .08       0    5013     .07       0
Bank Sta=4986.9,4990.9
XS Rating Curve= 0 ,0
Exp/Cntr=0.3,0.1

Type RM Length L Ch R = 1 ,970     ,169,169,169
BEGIN DESCRIPTION:
Stream0791 2.0
END DESCRIPTION:
XS GIS Cut Line= 3
      2448974.97     13596074.98        2448375.       13595725.
      2448074.97     13596025.03
#Sta/Elev= 30
  4305.4   263.1  4340.5  262.21  4436.4  261.65  4444.3  262.09  4457.9  261.67
  4788.7   262.3  4932.2  259.88  4954.9  259.44  4963.1  258.39  4970.6  258.62
  4986.3  254.54  4992.1  255.66  4997.1  254.52  5003.5  254.52  5014.1  259.09
  5084.8  259.96  5111.1  253.56  5111.4  253.06  5114.9  253.06  5115.1  253.56
  5141.4  261.11  5197.7   263.1  5240.4  265.76    5297  267.76  5337.4  270.71
    5377  272.44    5396   272.4  5410.1  273.12  5420.7  275.78  5424.3  275.78
#Mann= 8 ,-1 , 0
  4305.4     .07       0  4932.2     .12       0  4963.1      .1       0
  5111.1     .05       0  5115.1      .1       0  5197.7     .07       0
  5337.4     .12       0    5377     .07       0
Bank Sta=5111.1,5115.1
XS Rating Curve= 0 ,0
Exp/Cntr=0.3,0.1

Type RM Length L Ch R = 1 ,801     ,313,313,313
BEGIN DESCRIPTION:
H21066
END DESCRIPTION:
XS GIS Cut Line= 3
      2448816.59     13595757.79       2448364.8     13595551.77
       2447909.7     13595855.17
#Sta/Elev= 30
  4514.7  257.96  4615.4   258.9  4746.2  258.88  4852.9  258.62  4895.3  258.27
  4923.9  256.91  4941.4  257.87  4959.7  257.47    4978  256.68  4987.5  254.84
    4993  252.35  5021.5  252.24  5025.6  251.66  5025.8  251.16  5029.6  251.66
  5042.6  252.75  5071.1   252.7  5078.6  254.77  5084.6  252.95  5107.1  256.81
  5143.2  257.69  5150.7  257.28  5179.3  258.58  5186.8  258.06  5220.5   258.7
    5301  261.39    5310  261.07  5341.7  262.65  5481.2  268.98  5558.2  273.45
#Mann= 8 ,-1 , 0
  4514.7     .07       0  4746.2     .12       0  4852.9     .07       0
  4959.7      .1       0  5025.6     .05       0  5029.6      .1       0
  5220.5     .07       0  5341.7     .12       0
Bank Sta=5025.6,5029.6
XS Rating Curve= 0 ,0
Exp/Cntr=0.3,0.1

Type RM Length L Ch R = 1 ,488     ,356,356,356
BEGIN DESCRIPTION:
Stream0791 1.0
END DESCRIPTION:
XS GIS Cut Line= 3
      2448725.01     13595575.01        2448275.       13595275.
      2447975.01     13595574.99
#Sta/Elev= 30
  4467.3  257.23  4475.9  256.81  4488.8  256.95  4604.8  256.82  4661.5  256.17
  4755.8  254.97  4769.3  250.39  4778.3  248.69  4820.4  248.58  4861.9  246.85
  4862.2  246.35  4865.9  246.85  4871.4  248.06  4877.4     247    4900  247.44
  4907.5  249.32  4913.5   248.2  4922.5  251.46    4936   252.3  4949.6  251.14
  4964.6   251.3  4979.6  253.57  4994.6  253.76  5005.1  251.84  5036.4  249.19
    5093  254.26  5242.1   255.4    5291  257.18  5361.7  257.57  5432.4  260.06
#Mann= 8 ,-1 , 0
  4467.3     .12       0  4475.9     .07       0  4488.8     .12       0
  4604.8     .07       0  4661.5      .1       0  4861.9     .05       0
  4865.9      .1       0  5242.1     .07       0
Bank Sta=4861.9,4865.9
XS Rating Curve= 0 ,0
Exp/Cntr=0.3,0.1

Type RM Length L Ch R = 1 ,132     ,0,0,0
BEGIN DESCRIPTION:
XS7733
END DESCRIPTION:
XS GIS Cut Line= 3
      2448863.01     13595326.55       2448347.4     13594946.35
      2447677.23     13595050.26
#Sta/Elev= 30
    4363  253.77  4426.7  252.16  4664.1  252.27  4783.8  251.37  4908.2  250.67
  4942.6  248.89  4948.8     247  4956.9  247.14  4978.1  242.74  5024.3  241.41
  5029.4  242.57  5046.5  242.62  5046.6  240.98  5047.6  240.48    5087  240.98
  5107.2  244.82  5117.4   248.2  5137.6  250.35  5188.2  250.48  5238.8  247.87
  5269.2  248.43  5299.5  243.11  5329.9  244.19  5354.5  249.65  5370.1  250.84
  5486.7  253.98  5611.5     255  5653.7  256.51  5672.5  255.97  5681.8  256.11
#Mann= 9 ,-1 , 0
    4363     .05       0  4664.1     .07       0  4783.8     .12       0
  4908.2      .1       0  5046.6     .05       0    5087      .1       0
  5370.1     .12       0  5486.7     .07       0  5672.5     .12       0
Bank Sta=5046.6,5087
XS Rating Curve= 0 ,0
Exp/Cntr=0.3,0.1

Chan Stop Cuts=-1
Use User Specified Reach Order=0
Composite Channel Slope=5