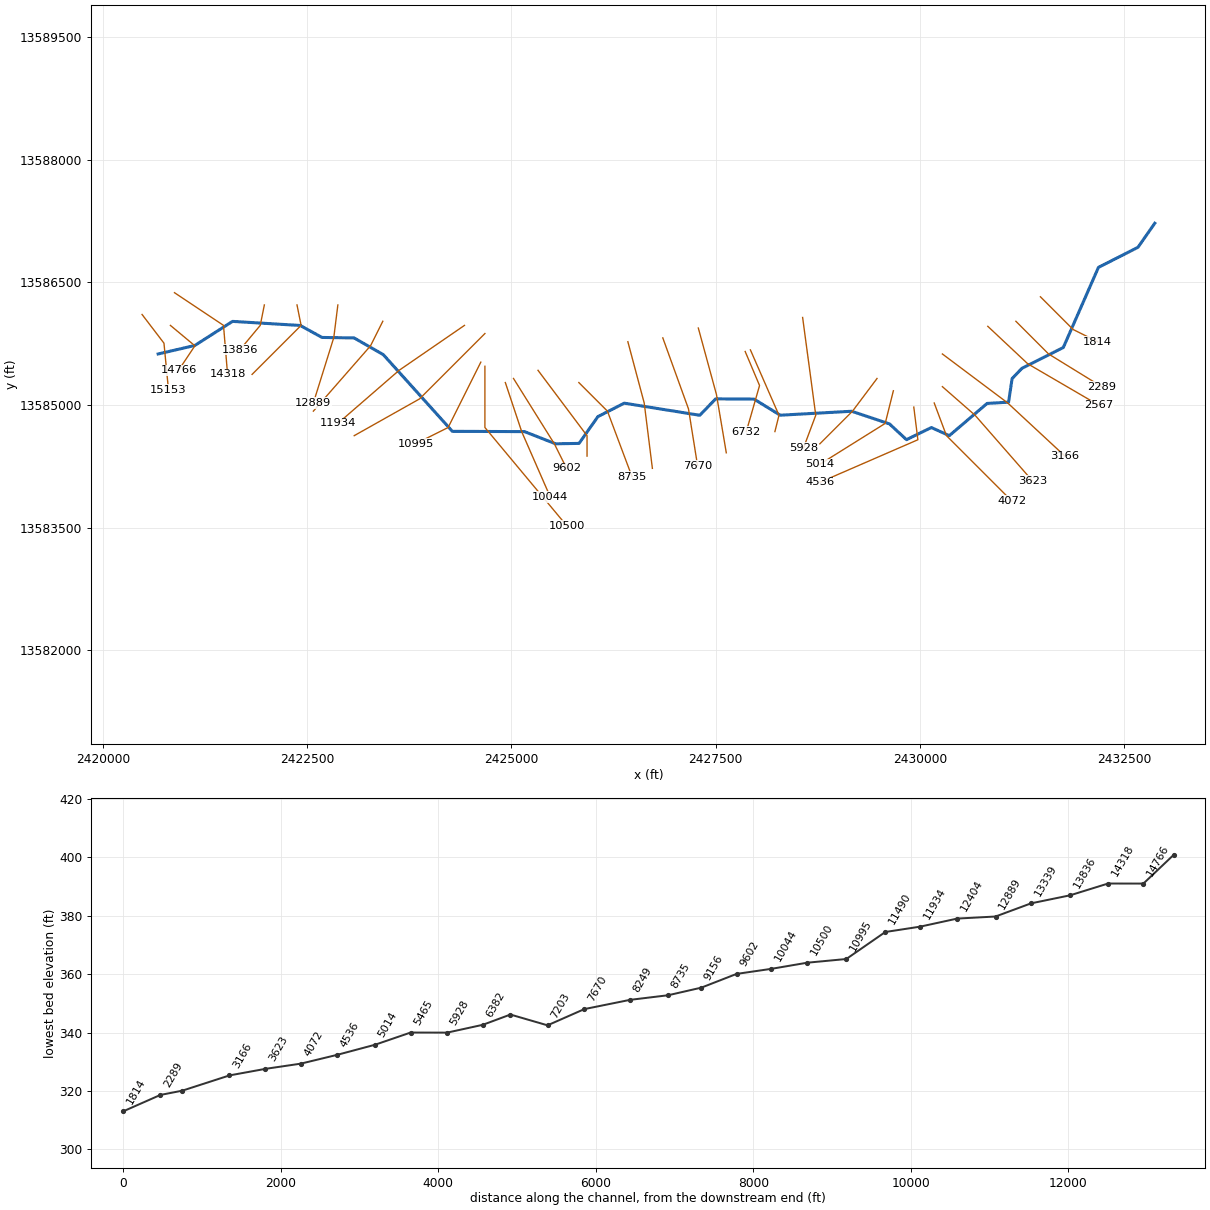
--- Stream0792.prj (project) ---

Proj Title=Stream0792 Base Level Engineering
Current Plan=p01
Default Exp/Contr=0.3,0.1
English Units
Geom File=g01
Flow File=f01
Plan File=p01
Y Axis Title=Elevation
X Axis Title(PF)=Main Channel Distance
X Axis Title(XS)=Station
BEGIN DESCRIPTION:
Stream0792
END DESCRIPTION:
DSS Export Rating Curves= 0
DSS Export Rating Curve Sorted= 0
DSS Export Volume Flow Curves= 0
DXF OffsetX= 0
DXF OffsetY= 0
DXF ScaleX= 1
DXF ScaleY= 10

--- Stream0792.p01 (plan) ---

Plan Title=Multiple Run
Short Identifier=Multiple
Geom File=g01
Flow File=f01
Subcritical Flow
K Sum by GR= 0
Std Step Tol= 0.01
Critical Tol= 0.01
Num of Std Step Trials= 20
Max Error Tol= 0.3
Flow Tol Ratio= 0.001
Split Flow NTrial= 30
Split Flow Tol= 0.02
Split Flow Ratio= 0.02
Log Output Level= 0
Friction Slope Method= 1
Unsteady Friction Slope Method= 2
Unsteady Bridges Friction Slope Method= 1
Parabolic Critical Depth
Global Vel Dist=  1 , 1 , 1
Global Log Level= 0
CheckData=True
Encroach Param= -1, 0, 0, 0
BEGIN DESCRIPTION:
Multiple Run
END DESCRIPTION:

--- Stream0792.f01 (steady flow) ---

Flow Title=Multiple
Number of Profiles=7
Profile Names=10-year,25-year,50-year,1pct_min,100-year,1pct_plu,500-year
River Rch & RM= Stream0792,Reach-1,15153
     879    1459    1998    1325    2644    5275    4586
River Rch & RM= Stream0792,Reach-1,10500
    1205    2032    2814    1884    3759    7501    6653
River Rch & RM= Stream0792,Reach-1,9156
    1371    2320    3216    2154    4298    8576    7616
River Rch & RM= Stream0792,Reach-1,3623
    1900    3257    4555    3075    6135   12240   11039
Boundary for River Rch & Prof#=Stream0792,Reach-1,1
Up Type=0
Dn Type=3
Dn Slope=0.005
Boundary for River Rch & Prof#=Stream0792,Reach-1,2
Up Type=0
Dn Type=3
Dn Slope=0.005
Boundary for River Rch & Prof#=Stream0792,Reach-1,3
Up Type=0
Dn Type=3
Dn Slope=0.005
Boundary for River Rch & Prof#=Stream0792,Reach-1,4
Up Type=0
Dn Type=3
Dn Slope=0.005
Boundary for River Rch & Prof#=Stream0792,Reach-1,5
Up Type=0
Dn Type=3
Dn Slope=0.005
Boundary for River Rch & Prof#=Stream0792,Reach-1,6
Up Type=0
Dn Type=3
Dn Slope=0.005
Boundary for River Rch & Prof#=Stream0792,Reach-1,7
Up Type=0
Dn Type=3
Dn Slope=0.005

--- Stream0792.g01 (geometry) ---

Geom Title=Existing Conditions
Program Version=4.10

River Reach=Stream0792      ,Reach-1
Reach XY= 30
        2420675.       13585625.      2421123.45     13585728.75
       2421585.5     13586023.78       2422414.5      13585973.8
      2422680.93     13585827.24      2423073.53     13585821.45
      2423431.05     13585616.84      2424276.36     13584678.27
      2425159.79     13584674.49      2425540.22     13584525.52
      2425827.47     13584530.45      2426058.32     13584858.36
      2426380.86     13585022.93      2427304.87      13584874.6
      2427499.79     13585075.33      2427969.07     13585072.76
      2428290.16     13584875.39       2429164.5     13584923.78
       2429627.3     13584769.17      2429835.44     13584576.03
      2430140.18     13584724.64      2430359.53     13584624.99
      2430822.55     13585019.54      2431085.18     13585035.32
      2431128.54     13585323.54      2431248.18     13585448.71
      2431755.57     13585704.36      2432185.52     13586684.79
      2432669.38     13586930.62        2432875.       13587225.

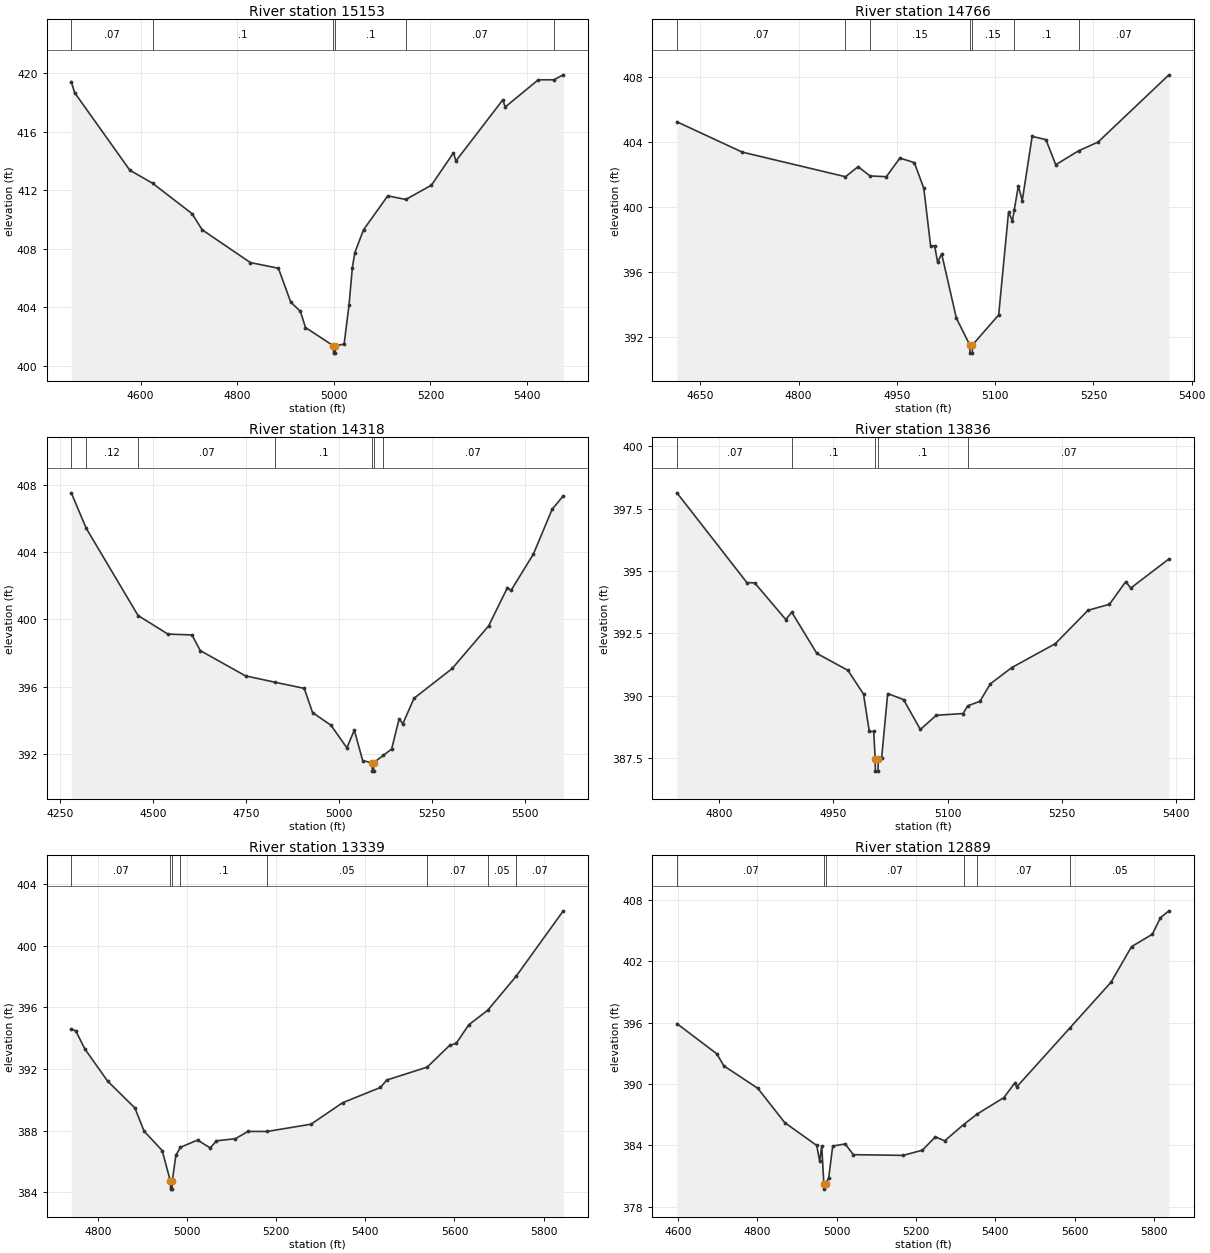
Type RM Length L Ch R = 1 ,15153   ,387,387,387
BEGIN DESCRIPTION:
XS7734
END DESCRIPTION:
XS GIS Cut Line= 3
      2420478.06     13586108.55      2420746.36     13585756.99
      2420801.87     13585183.42
#Sta/Elev= 30
  4456.4  419.43  4463.4  418.68  4577.7  413.38  4624.7  412.49  4706.5  410.41
  4727.3  409.31  4827.1  407.07  4885.2  406.68  4910.7  404.37  4930.8  403.73
  4941.2  402.63  4999.1  401.38  4999.4  400.88  5002.9  400.88  5003.1  401.38
  5021.2   401.5  5031.3  404.14  5038.3  406.73  5043.3  407.74  5061.4  409.31
  5111.6  411.63  5148.9  411.38    5202  412.36  5247.6  414.57  5252.6  414.01
  5349.7  418.19  5354.7   417.7  5423.1  419.56  5455.2  419.56  5474.9   419.9
#Mann= 6 ,-1 , 0
  4456.4     .07       0  4624.7      .1       0  4999.1     .05       0
  5003.1      .1       0  5148.9     .07       0  5455.2     .12       0
Bank Sta=4999.1,5003.1
XS Rating Curve= 0 ,0
Exp/Cntr=0.3,0.1

Type RM Length L Ch R = 1 ,14766   ,448,448,448
BEGIN DESCRIPTION:
Stream0792 32.0
END DESCRIPTION:
XS GIS Cut Line= 3
      2420824.99     13585975.01        2421125.       13585725.
      2420924.99     13585424.99
#Sta/Elev= 30
  4614.2  405.26  4713.8  403.39  4871.5  401.87  4890.8  402.49  4908.8  401.92
  4933.8  401.87  4954.6  403.02  4976.7  402.74  4991.1  401.15  5001.5   397.6
  5007.7   397.6  5012.2  396.58  5018.3  397.12  5040.8  393.14  5061.3  391.48
  5061.6  390.98  5065.1  390.98  5065.3  391.48  5105.4  393.34  5120.4  399.67
  5126.4  399.16  5129.1   399.8  5135.4   401.3  5141.4   400.4  5156.5  404.36
  5177.5  404.16  5192.5  402.61  5227.4  403.47  5257.1  404.01  5365.3  408.16
#Mann= 7 ,-1 , 0
  4614.2     .07       0  4871.5      .1       0  4908.8     .15       0
  5061.3     .05       0  5065.3     .15       0  5129.1      .1       0
  5227.4     .07       0
Bank Sta=5061.3,5065.3
XS Rating Curve= 0 ,0
Exp/Cntr=0.3,0.1

Type RM Length L Ch R = 1 ,14318   ,482,482,482
BEGIN DESCRIPTION:
Stream0792 31.0
END DESCRIPTION:
XS GIS Cut Line= 3
      2420875.01     13586374.99        2421475.       13585975.
        2421525.     13585374.98
#Sta/Elev= 30
    4279  407.51  4319.4   405.4  4458.7  400.23  4538.9  399.13  4603.5  399.08
    4626  398.15  4747.7  396.65  4827.8  396.27  4905.5  395.91    4928  394.47
  4977.6  393.72  5020.2  392.38  5040.2  393.43  5062.8  391.62  5088.4   391.5
  5088.7     391  5092.2     391  5092.4   391.5  5117.9  391.93  5140.6  392.31
  5160.7   394.1  5170.7  393.81  5200.8  395.32  5303.6  397.09  5401.5  399.62
  5451.7  401.87  5461.7  401.72  5521.9  403.88  5572.1  406.53  5602.2  407.33
#Mann= 7 ,-1 , 0
    4279     .07       0  4319.4     .12       0  4458.7     .07       0
  4827.8      .1       0  5088.4     .05       0  5092.4      .1       0
  5117.9     .07       0
Bank Sta=5088.4,5092.4
XS Rating Curve= 0 ,0
Exp/Cntr=0.3,0.1

Type RM Length L Ch R = 1 ,13836   ,497,497,497
BEGIN DESCRIPTION:
Stream0792 30.0
END DESCRIPTION:
XS GIS Cut Line= 3
        2421975.     13586225.02        2421925.       13585975.
      2421674.99     13585674.99
#Sta/Elev= 30
  4744.9  398.13  4836.7  394.53  4846.9  394.52  4887.7  393.05  4895.6  393.34
  4928.5  391.69  4969.3  391.01  4989.7  390.06  4997.3  388.56  5003.1  388.56
    5005  387.47  5005.3  386.97  5008.8  386.97    5009  387.47  5013.5  387.51
  5021.4  390.08  5042.2  389.84  5064.3  388.64  5085.1  389.21  5120.3  389.28
  5126.5  389.59  5142.4  389.77  5156.1  390.47  5184.1  391.12  5241.3  392.08
  5284.3  393.42  5312.3  393.66  5333.8  394.57  5340.3  394.31  5390.4  395.48
#Mann= 5 ,-1 , 0
  4744.9     .07       0  4895.6      .1       0    5005     .05       0
    5009      .1       0  5126.5     .07       0
Bank Sta=5005,5009
XS Rating Curve= 0 ,0
Exp/Cntr=0.3,0.1

Type RM Length L Ch R = 1 ,13339   ,450,450,450
BEGIN DESCRIPTION:
Stream0792 29.0
END DESCRIPTION:
XS GIS Cut Line= 3
      2422374.99     13586225.04        2422425.       13585975.
      2421825.02     13585375.02
#Sta/Elev= 30
  4740.5   394.6  4750.7  394.46  4771.1  393.29  4822.1  391.21  4883.3  389.47
  4903.7  387.97  4944.5  386.71  4962.9  384.71  4963.2  384.21  4966.7  384.21
  4966.9  384.71  4975.1   386.4  4985.2  386.92  5023.8  387.39  5052.1  386.88
  5066.2  387.34  5108.6  387.48  5136.9  387.95  5180.3  387.95  5278.3  388.42
    5349  389.81  5433.9   390.8    5448  391.28  5538.8  392.12  5589.5  393.54
  5603.6  393.65  5631.9  394.86  5674.4   395.8  5738.3  398.01    5844  402.25
#Mann= 8 ,-1 , 0
  4740.5     .07       0  4962.9     .05       0  4966.9     .07       0
  4985.2      .1       0  5180.3     .05       0  5538.8     .07       0
  5674.4     .05       0  5738.3     .07       0
Bank Sta=4962.9,4966.9
XS Rating Curve= 0 ,0
Exp/Cntr=0.3,0.1

Type RM Length L Ch R = 1 ,12889   ,485,485,485
BEGIN DESCRIPTION:
Stream0792 28.0
END DESCRIPTION:
XS GIS Cut Line= 3
        2422875.     13586224.97        2422825.       13585825.
      2422575.01     13585025.03
#Sta/Elev= 30
  4596.9  395.89  4697.6  392.94  4715.3  391.76  4800.9  389.57    4869  386.21
  4949.6  383.98  4957.1  382.42  4962.2  383.95  4967.6  380.21  4967.9  379.71
  4971.8  380.21  4979.8  380.82  4989.9  383.92  5021.5  384.13  5041.9  383.08
  5167.6  383.01  5216.3  383.52  5248.8  384.82  5272.4  384.43    5320  386.02
  5354.7  387.06  5421.7  388.66  5448.9  390.07  5454.2  389.71  5588.5  395.48
    5692  399.94  5743.8  403.42  5796.2  404.63  5816.7  406.25  5838.1  406.92
#Mann= 6 ,-1 , 0
  4596.9     .07       0  4967.6     .05       0  4971.8     .07       0
    5320     .05       0  5354.7     .07       0  5588.5     .05       0
Bank Sta=4967.6,4971.8
XS Rating Curve= 0 ,0
Exp/Cntr=0.3,0.1

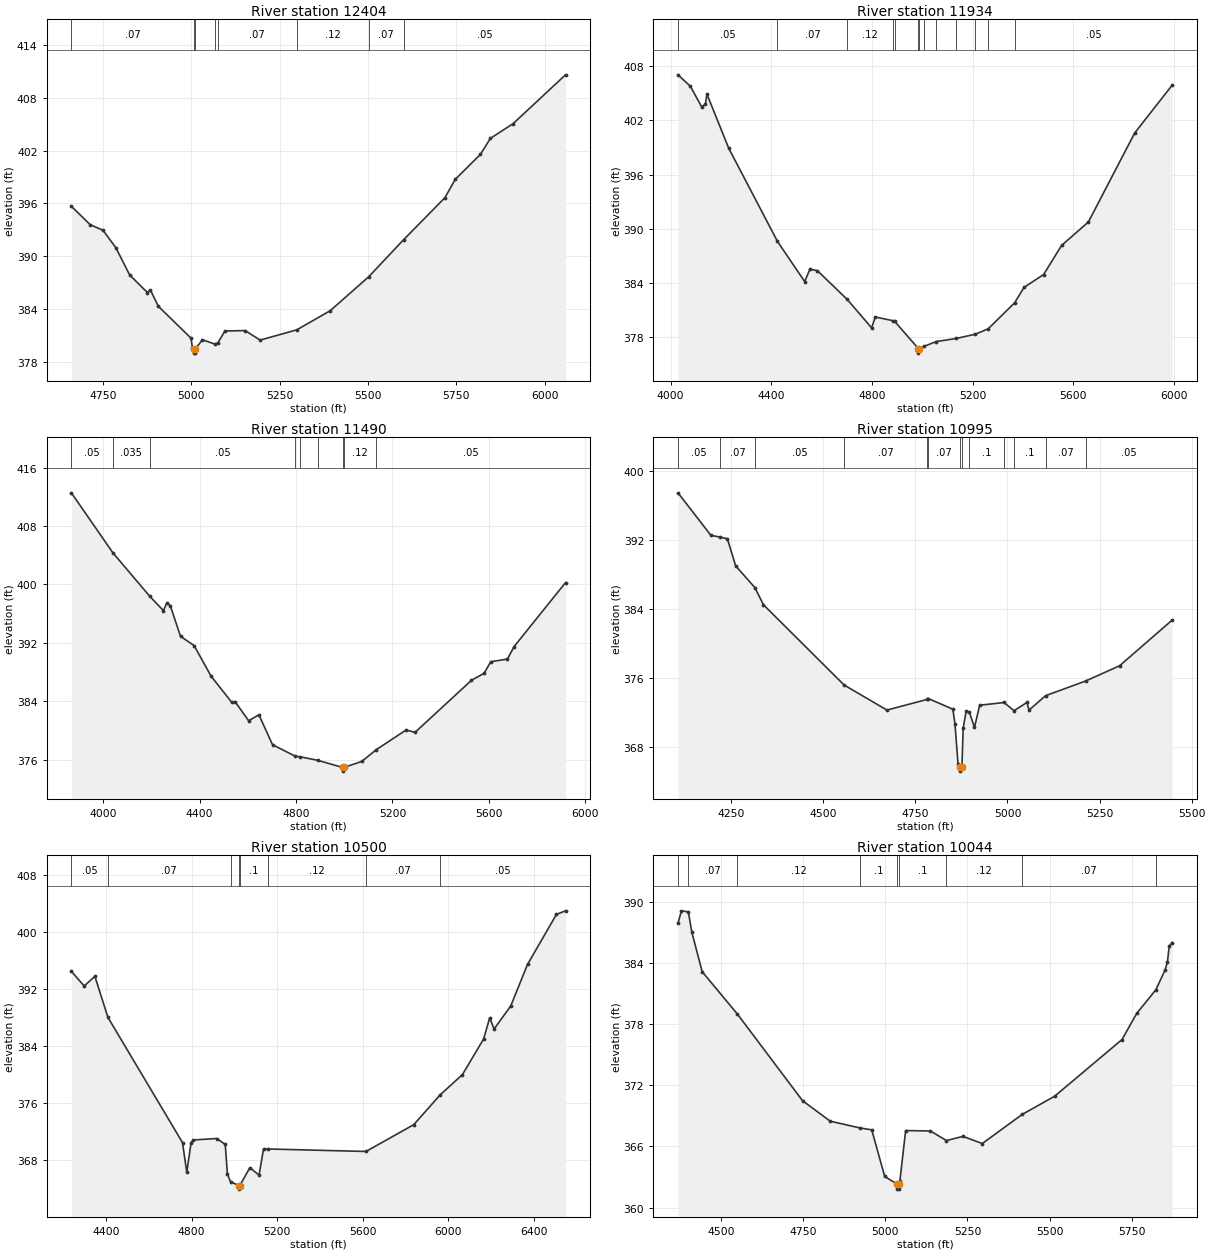
Type RM Length L Ch R = 1 ,12404   ,470,470,470
BEGIN DESCRIPTION:
Stream0792 27.0
END DESCRIPTION:
XS GIS Cut Line= 3
      2423425.02     13586025.04        2423275.       13585725.
      2422574.98     13584924.98
#Sta/Elev= 30
  4660.3  395.67  4713.5  393.59  4749.8  392.95  4786.1  390.98  4825.3  387.88
  4875.6  385.88    4884  386.17  4906.3  384.33  4999.1   380.7  5002.9  379.61
  5007.4  379.51  5007.7  379.01  5011.3  379.01  5011.6  379.51  5031.3  380.53
  5066.1  380.04  5074.7  380.16  5094.9  381.52  5151.9  381.57  5194.6  380.49
  5298.3  381.65    5393  383.83  5501.4  387.66  5600.6  391.88  5717.1  396.63
    5747  398.74  5818.2  401.57  5846.2  403.38  5910.2  405.04  6058.8  410.59
#Mann= 8 ,-1 , 0
  4660.3     .07       0  5007.4     .05       0  5011.6     .07       0
  5066.1      .1       0  5074.7     .07       0  5298.3     .12       0
  5501.4     .07       0  5600.6     .05       0
Bank Sta=5007.4,5011.6
XS Rating Curve= 0 ,0
Exp/Cntr=0.3,0.1

Type RM Length L Ch R = 1 ,11934   ,444,444,444
BEGIN DESCRIPTION:
Stream0792 26.0
END DESCRIPTION:
XS GIS Cut Line= 3
      2424425.01     13585975.01        2423625.       13585425.
      2422875.01     13584775.01
#Sta/Elev= 30
  4029.4  407.05  4078.8  405.78  4123.5  403.49  4138.4  403.83  4144.4  404.91
    4231  398.92  4424.7  388.61  4532.8  384.17  4553.7  385.55  4583.5  385.37
  4701.8  382.19  4798.6  379.05  4813.5  380.25  4883.3  379.84  4890.2  379.77
  4984.6  376.75  4984.9  376.25  4988.9  376.75  5007.8  377.01  5055.6  377.53
  5134.8  377.87  5211.3  378.35  5261.8  378.94  5366.9  381.82  5404.4  383.53
  5482.2  384.95  5553.5  388.17  5659.9  390.76  5844.1  400.62  5992.7   405.9
#Mann= 13 ,-1 , 0
  4029.4     .05       0  4424.7     .07       0  4701.8     .12       0
  4883.3     .07       0  4890.2     .12       0  4984.6     .05       0
  4988.9     .12       0  5007.8      .1       0  5055.6     .07       0
  5134.8     .12       0  5211.3     .07       0  5261.8     .12       0
  5366.9     .05       0
Bank Sta=4984.6,4988.9
XS Rating Curve= 0 ,0
Exp/Cntr=0.3,0.1

Type RM Length L Ch R = 1 ,11490   ,495,495,495
BEGIN DESCRIPTION:
Stream0792 25.0
END DESCRIPTION:
XS GIS Cut Line= 3
        2424675.       13585875.        2423875.       13585075.
      2423074.96     13584624.98
#Sta/Elev= 30
  3868.4  412.54  4040.4  404.33  4193.6  398.36  4250.2   396.4  4264.4  397.47
  4278.5   397.1    4321  392.88  4377.5  391.61  4448.2   387.4  4533.1  383.85
  4547.2  383.93  4603.8  381.31  4646.2  382.13  4702.8  378.02  4796.8  376.46
  4817.7  376.37  4890.2  375.89    4994  374.91  4994.3  374.41  4998.4  374.91
  5072.8  375.74  5133.8  377.37  5256.3  380.04  5293.9  379.73  5527.6  386.85
  5580.1  387.82  5607.9   389.4  5676.7  389.76  5704.4  391.47  5917.7  400.24
#Mann= 9 ,-1 , 0
  3868.4     .05       0  4040.4    .035       0  4193.6     .05       0
  4796.8     .12       0  4817.7     .05       0  4890.2     .12       0
    4994     .05       0  4998.4     .12       0  5133.8     .05       0
Bank Sta=4994,4998.4
XS Rating Curve= 0 ,0
Exp/Cntr=0.3,0.1

Type RM Length L Ch R = 1 ,10995   ,495,495,495
BEGIN DESCRIPTION:
Stream0792 24.0
END DESCRIPTION:
XS GIS Cut Line= 3
        2424625.     13585524.99        2424225.       13584725.
      2423825.03     13584525.01
#Sta/Elev= 30
  4105.4  397.49  4194.8  392.55    4220  392.35  4239.6  392.15  4261.9  389.01
  4314.2  386.48  4337.4  384.49  4556.4  375.17  4672.8  372.26    4781  373.49
  4784.9   373.6  4851.7  372.36  4857.3  370.69  4865.7  366.04  4871.7  365.67
    4872  365.17  4876.3  365.67  4879.6  370.15    4888  372.17  4896.7  371.98
  4910.4  370.25  4924.4  372.82  4990.5  373.14  5017.8  372.19  5052.9  373.15
  5058.5  372.26  5103.4  373.93  5211.8  375.63  5304.5  377.41    5447  382.71
#Mann= 13 ,-1 , 0
  4105.4     .05       0    4220     .07       0  4314.2     .05       0
  4556.4     .07       0    4781     .05       0  4784.9     .07       0
  4871.7     .05       0  4876.3     .07       0  4896.7      .1       0
  4990.5     .05       0  5017.8      .1       0  5103.4     .07       0
  5211.8     .05       0
Bank Sta=4871.7,4876.3
XS Rating Curve= 0 ,0
Exp/Cntr=0.3,0.1

Type RM Length L Ch R = 1 ,10500   ,456,456,456
BEGIN DESCRIPTION:
Stream0792 23.0
END DESCRIPTION:
XS GIS Cut Line= 3
        2424675.     13585474.97        2424675.       13584725.
      2425674.99     13583525.01
#Sta/Elev= 30
  4237.5  394.45  4297.5   392.4  4347.5  393.75  4408.5     388  4757.5  370.43
  4777.5  366.26  4797.5  370.41  4807.5   370.8  4917.5  371.01  4957.5  370.18
  4967.5  366.03  4982.1  364.95    5021  364.41  5021.3  363.91  5025.6  364.41
  5072.7  366.92  5115.7  365.87  5136.5  369.54  5157.3  369.54  5615.9  369.19
  5839.4  372.95    5964  377.16  6067.2  379.97  6166.2  384.96  6194.8  387.93
  6215.6  386.37  6293.7  389.62  6371.8  395.43  6507.2  402.44  6549.5  402.94
#Mann= 8 ,-1 , 0
  4237.5     .05       0  4408.5     .07       0  4982.1      .1       0
    5021     .05       0  5025.6      .1       0  5157.3     .12       0
  5615.9     .07       0    5964     .05       0
Bank Sta=5021,5025.6
XS Rating Curve= 0 ,0
Exp/Cntr=0.3,0.1

Type RM Length L Ch R = 1 ,10044   ,442,442,442
BEGIN DESCRIPTION:
Stream0792 22.0
END DESCRIPTION:
XS GIS Cut Line= 3
      2424925.01     13585274.96        2425125.       13584675.
      2425474.99     13583875.02
#Sta/Elev= 30
    4368  387.88  4378.5  389.09  4399.6  388.99  4410.1     387  4441.7  383.12
  4548.8  378.98  4747.4  370.48  4831.8  368.47  4921.9  367.81  4958.3  367.62
  4997.8  363.05  5035.3  362.31  5035.8  361.81  5040.7  361.81  5041.1  362.31
  5044.1  362.61  5061.6  367.55  5137.2  367.51  5186.1  366.57  5236.3  366.98
  5295.1  366.28  5416.6  369.13  5515.4  370.91  5720.8  376.47  5765.6  379.03
    5824  381.35  5851.8  383.27  5859.2  384.05  5864.7  385.62  5873.6  385.98
#Mann= 9 ,-1 , 0
    4368     .05       0  4399.6     .07       0  4548.8     .12       0
  4921.9      .1       0  5035.3     .05       0  5041.1      .1       0
  5186.1     .12       0  5416.6     .07       0    5824     .05       0
Bank Sta=5035.3,5041.1
XS Rating Curve= 0 ,0
Exp/Cntr=0.3,0.1

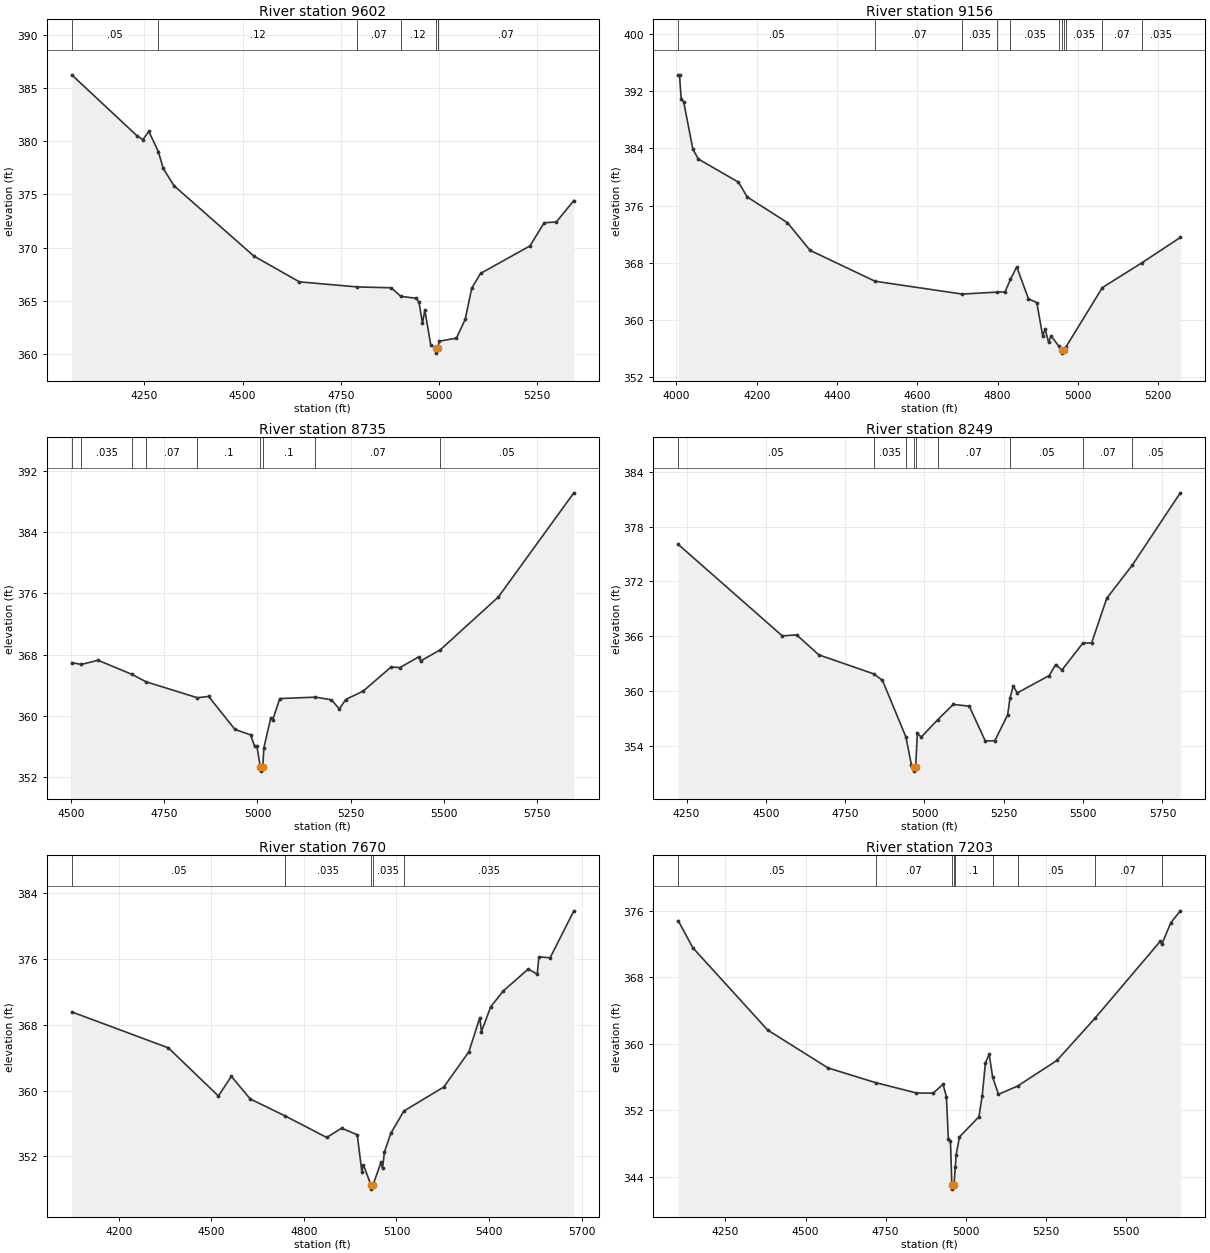
Type RM Length L Ch R = 1 ,9602    ,446,446,446
BEGIN DESCRIPTION:
Stream0792 21.0
END DESCRIPTION:
XS GIS Cut Line= 3
      2425025.01     13585324.98        2425525.       13584525.
      2425675.01     13584224.98
#Sta/Elev= 30
    4065  386.26  4230.7  380.54    4246  380.16  4261.3  380.93  4285.5  379.04
  4297.9  377.46    4325  375.84    4529   369.2  4644.6  366.78  4791.9   366.3
  4878.7  366.22  4903.1  365.41  4942.9  365.23  4949.4  364.84  4958.3  362.89
  4964.2  364.13  4979.5  360.81  4991.8  360.57  4992.3  360.07  4997.8  360.57
  4997.9  360.59  5000.7  361.19  5044.7  361.48  5067.1  363.25  5083.8  366.19
  5106.2  367.57    5232  370.16  5268.3  372.34  5299.1  372.41  5343.8  374.43
#Mann= 7 ,-1 , 0
    4065     .05       0  4285.5     .12       0  4791.9     .07       0
  4903.1     .12       0  4991.8     .05       0  4997.8     .12       0
  4997.9     .07       0
Bank Sta=4991.8,4997.8
XS Rating Curve= 0 ,0
Exp/Cntr=0.3,0.1

Type RM Length L Ch R = 1 ,9156    ,421,421,421
BEGIN DESCRIPTION:
Stream0792 20.0
END DESCRIPTION:
XS GIS Cut Line= 3
      2425324.98     13585425.03        2425925.       13584625.
        2425925.     13584375.04
#Sta/Elev= 30
  4004.7  394.29  4007.9  394.29    4012  390.91  4018.3   390.5  4041.2  383.88
  4054.7  382.52  4154.7  379.28  4176.6  377.21  4276.6  373.62  4332.9  369.75
  4494.7  365.43  4711.2  363.64  4798.7  363.91  4818.3  363.94  4831.8  365.69
  4847.4  367.45  4876.6  362.98  4897.4  362.44    4912  357.83  4918.3  358.71
  4926.6  356.92  4932.9  357.79  4952.4  356.34    4959  355.88  4959.5  355.38
  4965.1  355.88  4969.2  356.17  5060.5  364.53    5159  368.01  5254.7  371.55
#Mann= 11 ,-1 , 0
  4004.7     .05       0  4494.7     .07       0  4711.2    .035       0
  4798.7     .07       0  4831.8    .035       0  4952.4     .07       0
    4959    .035       0  4965.1     .07       0  4969.2    .035       0
  5060.5     .07       0    5159    .035       0
Bank Sta=4959,4965.1
XS Rating Curve= 0 ,0
Exp/Cntr=0.3,0.1

Type RM Length L Ch R = 1 ,8735    ,486,486,486
BEGIN DESCRIPTION:
Stream0792 19.0
END DESCRIPTION:
XS GIS Cut Line= 3
      2425825.02     13585274.98        2426175.       13584925.
      2426474.98     13584125.04
#Sta/Elev= 30
  4500.9  366.94  4526.7  366.71  4571.6  367.25  4662.2  365.42  4700.3  364.45
  4838.3  362.36  4868.6  362.53  4939.3  358.23  4981.7  357.51  4992.3     356
  4998.5     356  5007.8  353.28  5008.3  352.78  5014.2  353.28  5017.2  355.84
  5035.9  359.76  5041.2  359.51  5059.9  362.25  5155.9  362.44  5198.8  362.09
  5220.1  360.89    5237  362.13  5284.2  363.23    5359  366.37    5383   366.3
  5432.8  367.68  5438.2  367.16  5491.1  368.61  5647.3  375.51  5850.2  389.11
#Mann= 9 ,-1 , 0
  4500.9     .05       0  4526.7    .035       0  4662.2     .05       0
  4700.3     .07       0  4838.3      .1       0  5007.8     .05       0
  5014.2      .1       0  5155.9     .07       0  5491.1     .05       0
Bank Sta=5007.8,5014.2
XS Rating Curve= 0 ,0
Exp/Cntr=0.3,0.1

Type RM Length L Ch R = 1 ,8249    ,579,579,579
BEGIN DESCRIPTION:
Stream0792 18.0
END DESCRIPTION:
XS GIS Cut Line= 3
      2426424.99     13585775.03        2426625.       13585025.
        2426725.     13584224.96
#Sta/Elev= 30
  4223.8  376.07  4551.8  366.03  4597.1  366.14  4666.9  363.95  4840.2  361.86
  4867.4  361.16  4941.4  354.94  4958.6  351.91  4965.8  351.69  4966.3  351.19
  4972.2  351.69  4977.4  355.32  4989.7  354.93  5041.6  356.83  5090.7  358.51
  5141.1  358.32  5191.5   354.5  5221.7  354.53  5262.1  357.37  5269.4   359.2
  5279.7  360.54  5292.3  359.77  5393.1  361.68  5413.2  362.88  5433.4  362.29
  5499.5  365.26  5526.6  365.24  5574.5  370.16  5654.9  373.79  5806.3  381.73
#Mann= 9 ,-1 , 0
  4223.8     .05       0  4840.2    .035       0  4941.4     .12       0
  4965.8     .05       0  4972.2     .12       0  5041.6     .07       0
  5269.4     .05       0  5499.5     .07       0  5654.9     .05       0
Bank Sta=4965.8,4972.2
XS Rating Curve= 0 ,0
Exp/Cntr=0.3,0.1

Type RM Length L Ch R = 1 ,7670    ,467,467,467
BEGIN DESCRIPTION:
Stream0792 17.0
END DESCRIPTION:
XS GIS Cut Line= 3
      2426852.65     13585821.78      2427167.22     13584952.07
      2427278.09     13584259.13
#Sta/Elev= 30
  4048.1  369.54    4361  365.18  4523.2  359.33    4565  361.72  4626.3  358.98
    4740   356.9  4874.1   354.3  4922.1  355.43    4973  354.63  4987.8  350.16
  4992.9  350.98  5017.3  348.53  5017.8  348.03  5023.9  348.53  5049.9  351.28
  5054.9  350.58  5061.1  352.53  5081.4  354.79  5124.1  357.51  5253.5  360.43
  5334.6   364.7  5370.1  368.85  5375.2  367.14  5405.5  370.17    5446  372.08
    5527  374.74  5556.2  374.13  5561.3  376.23  5597.9  376.11  5674.7  381.81
#Mann= 5 ,-1 , 0
  4048.1     .05       0    4740    .035       0  5017.3    .035       0
  5023.9    .035       0  5124.1    .035       0
Bank Sta=5017.3,5023.9
XS Rating Curve= 0 ,0
Exp/Cntr=0.3,0.1

Type RM Length L Ch R = 1 ,7203    ,471,471,471
BEGIN DESCRIPTION:
Stream0792 16.0
END DESCRIPTION:
XS GIS Cut Line= 3
      2427287.49     13585942.08      2427509.55     13585127.85
      2427629.82     13584415.49
#Sta/Elev= 30
  4102.9  374.81  4148.5  371.55  4381.7  361.65    4570  357.08  4718.4  355.31
  4846.2  354.06    4898  354.04  4929.1   355.1  4939.5  353.63  4945.7  348.46
  4952.2  348.33  4956.5  342.98    4957  342.48  4963.3  342.98  4967.3  345.16
    4970  346.63  4980.2  348.76    5041   351.2  5051.2  353.73  5061.3  357.68
  5073.1  358.73  5083.8  355.97  5101.9   353.9  5161.5  354.89  5284.4  357.98
  5402.5  363.04  5607.1  372.35  5611.3  371.95  5639.4  374.55  5669.3     376
#Mann= 9 ,-1 , 0
  4102.9     .05       0  4718.4     .07       0  4956.5     .05       0
  4963.3     .07       0  4967.3      .1       0  5083.8     .07       0
  5161.5     .05       0  5402.5     .07       0  5611.3    .035       0
Bank Sta=4956.5,4963.3
XS Rating Curve= 0 ,0
Exp/Cntr=0.3,0.1

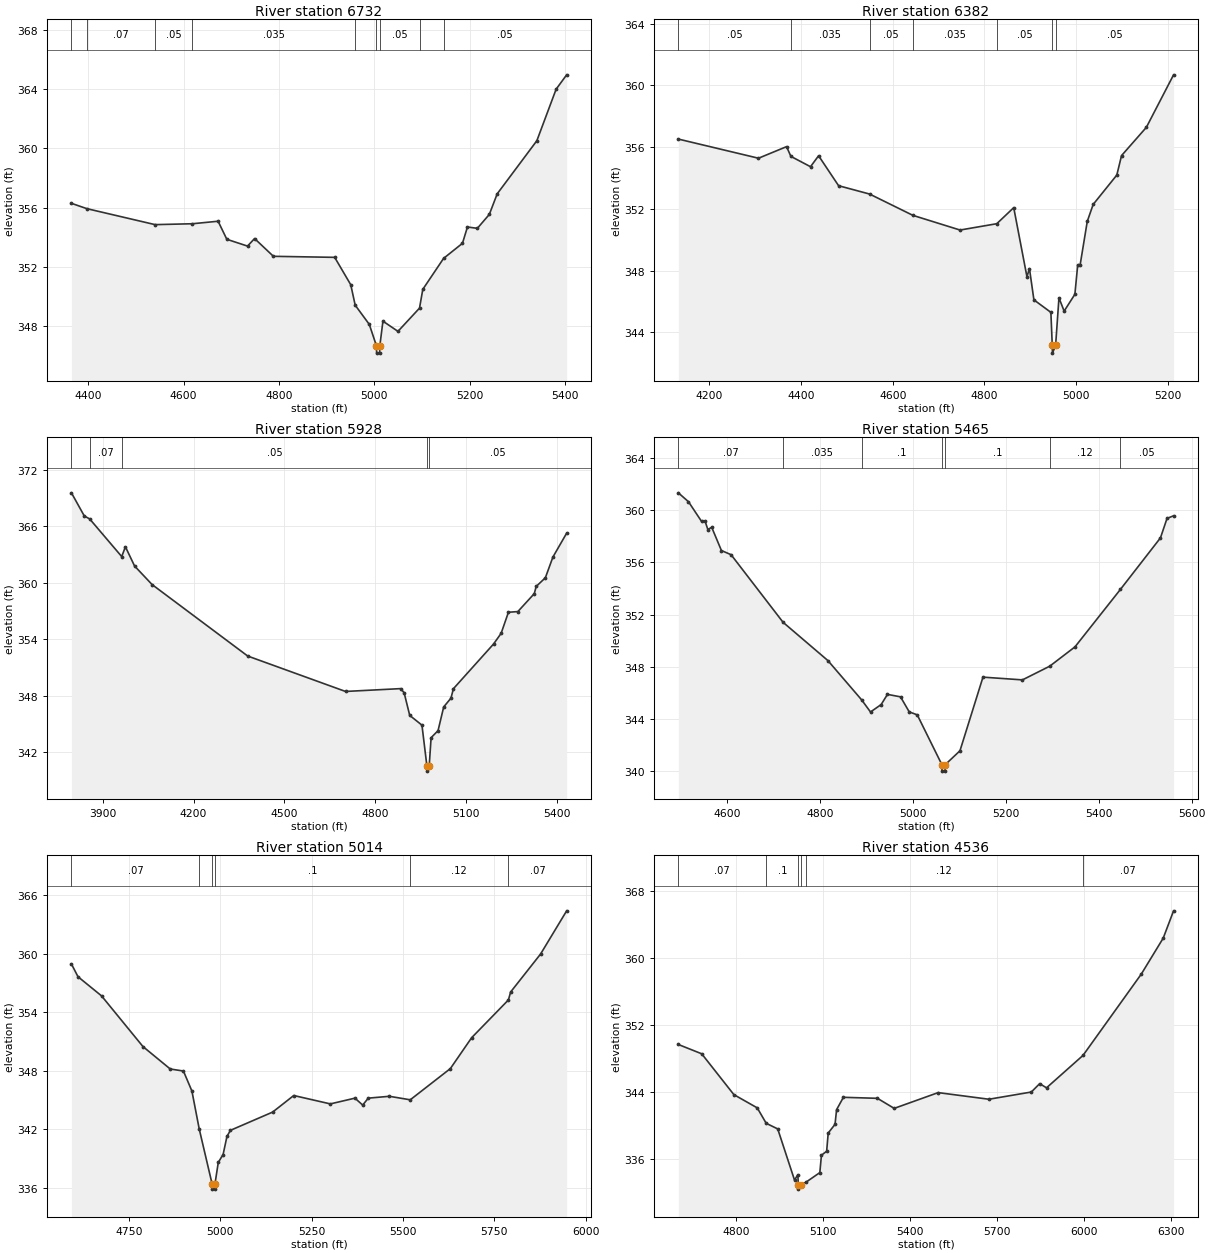
Type RM Length L Ch R = 1 ,6732    ,350,350,350
BEGIN DESCRIPTION:
Stream0792 15.0
END DESCRIPTION:
XS GIS Cut Line= 3
      2427861.13      13585655.2      2428036.91     13585238.88
      2427874.99     13584674.97
#Sta/Elev= 30
  4364.9  356.29  4397.2  355.93  4540.4  354.85  4618.6  354.91  4672.5  355.08
  4690.8  353.86  4734.2   353.4    4749  353.91  4788.5  352.71    4917  352.64
  4950.7  350.79    4960  349.41  4989.6  348.11  5004.5  346.67    5005  346.17
  5011.2  346.17  5011.7  346.67  5018.2  348.33  5049.7  347.64  5094.9  349.21
  5101.8  350.48  5145.4  352.57    5185  353.59  5195.4  354.69  5216.2   354.6
  5241.3  355.54  5257.8  356.93    5341  360.52  5381.4     364  5403.5  364.97
#Mann= 9 ,-1 , 0
  4364.9     .05       0  4397.2     .07       0  4540.4     .05       0
  4618.6    .035       0    4960     .05       0  5004.5     .05       0
  5011.7     .05       0  5094.9    .035       0  5145.4     .05       0
Bank Sta=5004.5,5011.7
XS Rating Curve= 0 ,0
Exp/Cntr=0.3,0.1

Type RM Length L Ch R = 1 ,6382    ,454,454,454
BEGIN DESCRIPTION:
Stream0792 14.0
END DESCRIPTION:
XS GIS Cut Line= 3
      2427924.99     13585675.02        2428275.       13584875.
        2428225.     13584674.99
#Sta/Elev= 30
  4132.7  356.52  4307.4  355.28  4368.6  356.03    4378   355.4  4420.8  354.73
  4438.4  355.44    4482   353.5  4549.6  352.96    4644  351.58  4746.7  350.63
  4826.8  351.04  4863.7  352.08  4892.5  347.61    4898  348.13  4907.7  346.11
  4944.7   345.3  4947.7  343.16  4948.2  342.66    4955  343.16  4962.3  346.24
  4973.6  345.38    4997  346.47  5003.2  348.38  5008.5  348.38    5024  351.19
  5036.9  352.29  5088.4  354.19  5098.7  355.45  5152.8  357.28  5212.1  360.68
#Mann= 7 ,-1 , 0
  4132.7     .05       0    4378    .035       0  4549.6     .05       0
    4644    .035       0  4826.8     .05       0  4947.7     .05       0
    4955     .05       0
Bank Sta=4947.7,4955
XS Rating Curve= 0 ,0
Exp/Cntr=0.3,0.1

Type RM Length L Ch R = 1 ,5928    ,463,463,463
BEGIN DESCRIPTION:
Stream0792 13.0
END DESCRIPTION:
XS GIS Cut Line= 3
      2428564.27     13586071.57        2428725.       13584875.
      2428575.01     13584475.02
#Sta/Elev= 30
    3797  369.53  3839.5  367.07  3857.2  366.76    3963  362.76  3975.2   363.8
  4005.4  361.76  4063.2  359.79  4378.8   352.2  4701.6  348.44  4883.2  348.74
    4895  348.31  4913.5   345.9  4953.9  344.86  4970.4  340.48  4970.9  339.98
  4977.7  340.48  4984.1  343.53    5007  344.28  5025.7   346.8  5049.7  347.73
  5057.7  348.73  5190.3  353.48  5215.2  354.61  5239.3  356.85  5270.4  356.92
  5324.7  358.83  5330.9  359.59  5361.2  360.51  5386.1  362.71  5431.5  365.25
#Mann= 5 ,-1 , 0
    3797     .05       0  3857.2     .07       0    3963     .05       0
  4970.4     .05       0  4977.7     .05       0
Bank Sta=4970.4,4977.7
XS Rating Curve= 0 ,0
Exp/Cntr=0.3,0.1

Type RM Length L Ch R = 1 ,5465    ,451,451,451
BEGIN DESCRIPTION:
Stream0792 12.0
END DESCRIPTION:
XS GIS Cut Line= 3
      2429474.98     13585324.97        2429175.       13584925.
      2428775.03     13584525.03
#Sta/Elev= 30
  4495.5  361.33  4517.3  360.65  4545.5  359.14  4552.8  359.18    4559  358.52
  4567.3  358.69  4588.2  356.91    4609  356.59  4720.9  351.41  4817.3  348.48
  4889.9  345.47    4909  344.54  4931.9  345.11  4945.5  345.89  4973.6   345.7
  4992.3  344.55  5009.6  344.32  5062.5  340.51    5063  340.01  5069.4  340.01
  5069.9  340.51  5101.5  341.57    5151  347.21  5235.9     347  5294.7  348.05
    5349  349.53  5446.7  353.93  5532.9  357.88    5547  359.37  5561.1  359.57
#Mann= 7 ,-1 , 0
  4495.5     .07       0  4720.9    .035       0  4889.9      .1       0
  5062.5     .05       0  5069.9      .1       0  5294.7     .12       0
  5446.7     .05       0
Bank Sta=5062.5,5069.9
XS Rating Curve= 0 ,0
Exp/Cntr=0.3,0.1

Type RM Length L Ch R = 1 ,5014    ,478,478,478
BEGIN DESCRIPTION:
Stream0792 11.0
END DESCRIPTION:
XS GIS Cut Line= 3
      2429674.99     13585174.95        2429575.       13584775.
      2428774.97     13584274.98
#Sta/Elev= 30
  4592.4  358.93  4610.4  357.62  4674.8  355.66  4788.2  350.46  4862.9  348.16
    4899  347.95  4922.2   345.9  4942.4  341.98  4977.7  336.34  4978.2  335.84
  4984.7  335.84  4985.2  336.34  4994.4  338.58  5007.6  339.39  5018.2  341.25
  5027.7  341.87  5143.2  343.74    5201  345.44  5301.2  344.58  5368.5  345.17
  5389.7  344.46    5405  345.17  5462.8  345.36  5519.9     345  5629.7   348.2
    5688  351.37  5788.6  355.24  5794.8  356.06  5876.7  359.95  5948.1  364.38
#Mann= 6 ,-1 , 0
  4592.4     .07       0  4942.4      .1       0  4977.7     .05       0
  4985.2      .1       0  5519.9     .12       0  5788.6     .07       0
Bank Sta=4977.7,4985.2
XS Rating Curve= 0 ,0
Exp/Cntr=0.3,0.1

Type RM Length L Ch R = 1 ,4536    ,464,464,464
BEGIN DESCRIPTION:
Stream0792 10.0
END DESCRIPTION:
XS GIS Cut Line= 3
        2429925.     13584975.02        2429975.       13584575.
      2428778.54     13584055.27
#Sta/Elev= 30
  4600.9  349.65  4681.5  348.54  4792.4  343.67    4873  342.09  4903.9  340.25
  4943.6  339.58  5001.5  333.48    5013  334.12  5014.7   332.9  5015.2   332.4
  5022.3   332.9  5039.9   333.2  5088.8  334.37  5094.3  336.44  5112.3  336.92
  5117.7  339.09  5141.2  340.13  5146.6  341.88  5170.1  343.35  5287.4  343.23
  5345.2  342.03  5496.8  343.91  5671.9  343.12    5818  343.98  5846.9  344.98
  5870.4  344.48  5996.3  348.35  6197.1  358.04  6272.9  362.34  6308.5  365.59
#Mann= 6 ,-1 , 0
  4600.9     .07       0  4903.9      .1       0  5014.7     .05       0
  5022.3      .1       0  5039.9     .12       0  5996.3     .07       0
Bank Sta=5014.7,5022.3
XS Rating Curve= 0 ,0
Exp/Cntr=0.3,0.1

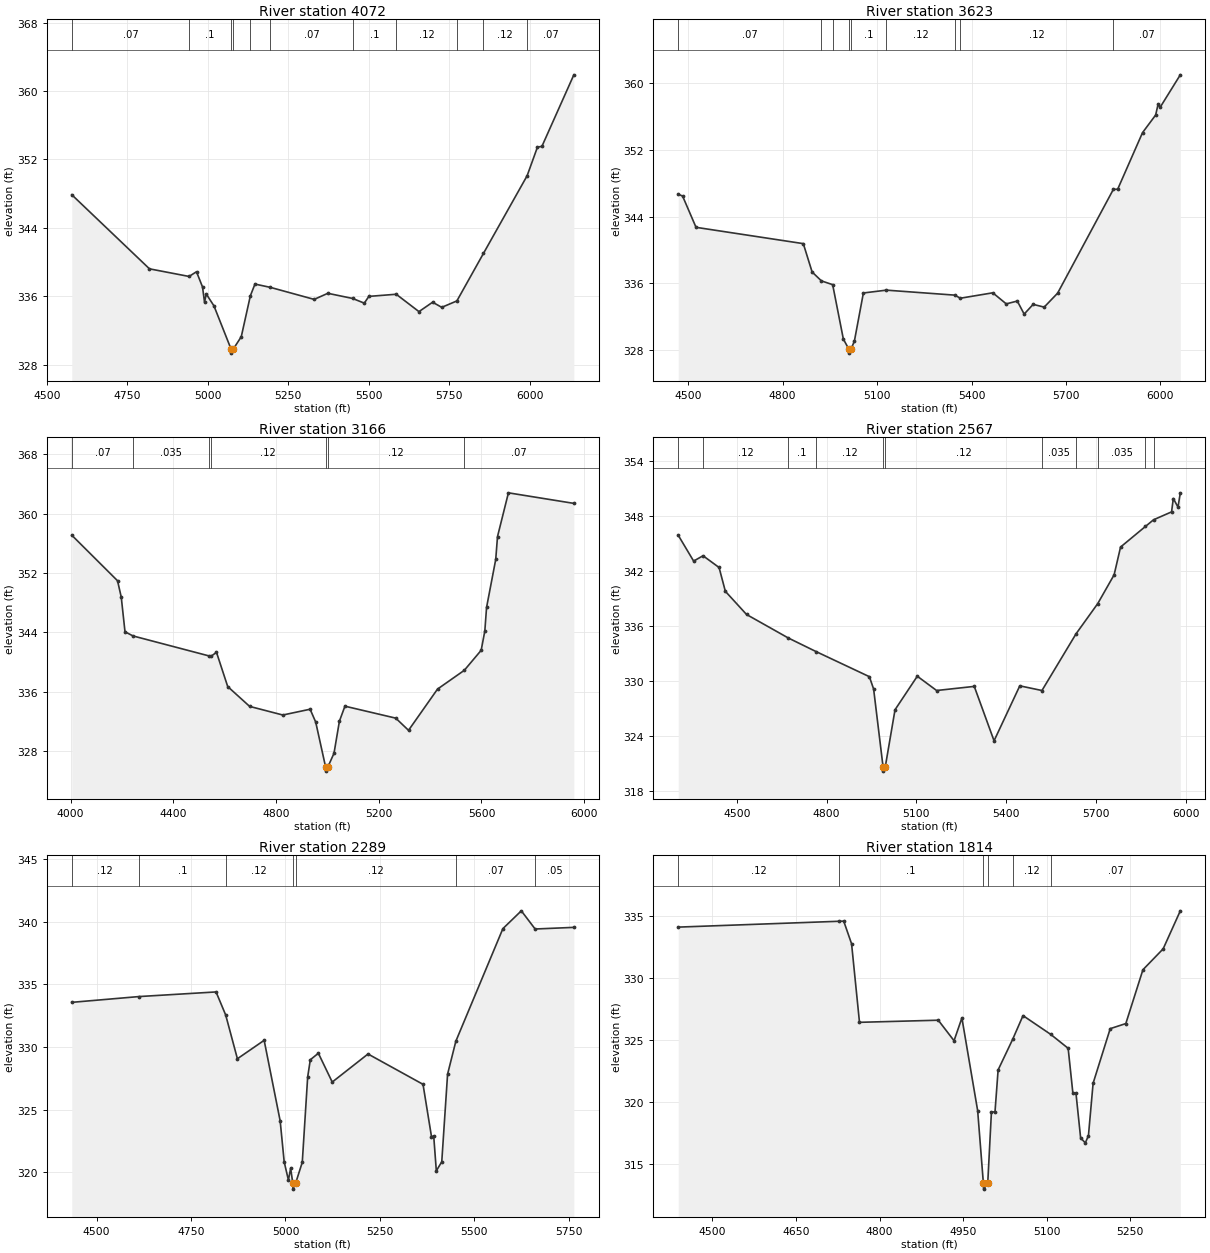
Type RM Length L Ch R = 1 ,4072    ,449,449,449
BEGIN DESCRIPTION:
Stream0792 9.0
END DESCRIPTION:
XS GIS Cut Line= 3
      2430174.98     13585025.04        2430325.       13584625.
      2431124.99     13583825.01
#Sta/Elev= 30
  4577.7  347.88  4818.9  339.22  4941.8  338.33  4964.9  338.88  4983.6   337.1
  4989.8  335.33  4995.2  336.28  5019.1  334.89  5071.9  329.87  5072.4  329.37
  5079.5  329.87  5103.9  331.29  5132.1  336.07  5146.4  337.44  5194.6  337.05
  5330.2  335.65  5372.6  336.36  5449.4  335.76  5485.8  335.21  5499.9     336
  5584.9  336.25  5655.5  334.22  5697.9  335.32  5726.2  334.72  5773.2  335.47
  5855.8  341.03  5991.3   350.1  6023.2  353.43  6037.3  353.54  6136.3  361.89
#Mann= 11 ,-1 , 0
  4577.7     .07       0  4941.8      .1       0  5071.9     .05       0
  5079.5      .1       0  5132.1     .12       0  5194.6     .07       0
  5449.4      .1       0  5584.9     .12       0  5773.2      .1       0
  5855.8     .12       0  5991.3     .07       0
Bank Sta=5071.9,5079.5
XS Rating Curve= 0 ,0
Exp/Cntr=0.3,0.1

Type RM Length L Ch R = 1 ,3623    ,457,457,457
BEGIN DESCRIPTION:
Stream0792 8.0
END DESCRIPTION:
XS GIS Cut Line= 3
      2430274.99     13585225.01        2430675.       13584875.
      2431374.98     13584075.03
#Sta/Elev= 30
  4468.5  346.69  4482.3  346.47    4525  342.71  4865.7  340.75  4893.7  337.34
  4923.3  336.27  4958.9  335.82  4992.9  329.28    5010  328.09  5010.5  327.59
  5017.6  328.09    5028  329.05  5056.5  334.82  5129.6  335.16  5346.9  334.56
  5364.4  334.19  5467.5  334.84  5510.2  333.51  5545.3  333.85  5567.1  332.28
  5595.6  333.45  5630.7  333.12  5673.4   334.8  5850.2  347.26  5864.2   347.3
    5943  354.09  5984.7  356.21  5992.3  357.48    5999  357.14    6063  361.04
#Mann= 9 ,-1 , 0
  4468.5     .07       0  4923.3     .12       0  4958.9      .1       0
    5010     .05       0  5017.6      .1       0  5129.6     .12       0
  5346.9     .07       0  5364.4     .12       0  5850.2     .07       0
Bank Sta=5010,5017.6
XS Rating Curve= 0 ,0
Exp/Cntr=0.3,0.1

Type RM Length L Ch R = 1 ,3166    ,599,599,599
BEGIN DESCRIPTION:
Stream0792 7.0
END DESCRIPTION:
XS GIS Cut Line= 3
      2430274.97     13585625.02        2431075.       13585025.
      2431775.01     13584374.99
#Sta/Elev= 30
  4004.4  357.09  4182.6  350.96  4197.1  348.76  4211.7  344.09  4243.1  343.53
  4540.3  340.83  4546.3  340.78    4568  341.33  4611.7  336.72  4697.1  334.05
  4826.3  332.89  4932.6  333.67  4954.4  331.94  4993.3  325.84  4993.8  325.34
    5001  325.84  5025.7  327.75  5046.7  332.06  5068.2  334.08  5266.1  332.47
  5315.9  330.83  5428.8  336.38  5533.2  338.91  5598.8   341.6    5613  344.19
  5619.8  347.37  5655.5  353.83  5662.4   356.9  5704.9  362.79  5959.7  361.37
#Mann= 7 ,-1 , 0
  4004.4     .07       0  4243.1    .035       0  4540.3     .07       0
  4546.3     .12       0  4993.3     .05       0    5001     .12       0
  5533.2     .07       0
Bank Sta=4993.3,5001
XS Rating Curve= 0 ,0
Exp/Cntr=0.3,0.1

Type RM Length L Ch R = 1 ,2567    ,278,278,278
BEGIN DESCRIPTION:
Stream0792 6.0
END DESCRIPTION:
XS GIS Cut Line= 3
      2430830.79      13585963.5      2431320.17     13585504.71
      2432189.63     13584997.89
#Sta/Elev= 30
  4304.3  345.87  4355.7  343.05  4387.2  343.63  4440.7  342.35  4461.7  339.75
  4532.5  337.22  4671.6  334.66  4765.4  333.16  4942.8  330.43    4957  329.08
  4988.4  320.62  4988.9  320.12  4996.1  320.62  5028.5  326.82  5102.9  330.48
  5167.4  328.92  5293.2  329.37  5359.3  323.43  5445.3  329.43  5519.3  328.92
  5633.4  335.12  5705.7  338.41  5760.4  341.55  5781.9  344.58    5865  346.83
  5892.2  347.56  5952.3  348.42  5958.1  349.88  5973.8  348.94  5981.5   350.5
#Mann= 11 ,-1 , 0
  4304.3     .07       0  4387.2     .12       0  4671.6      .1       0
  4765.4     .12       0  4988.4     .05       0  4996.1     .12       0
  5519.3    .035       0  5633.4     .07       0  5705.7    .035       0
    5865     .05       0  5892.2    .035       0
Bank Sta=4988.4,4996.1
XS Rating Curve= 0 ,0
Exp/Cntr=0.3,0.1

Type RM Length L Ch R = 1 ,2289    ,475,475,475
BEGIN DESCRIPTION:
Stream0792 5.0
END DESCRIPTION:
XS GIS Cut Line= 3
      2431174.97     13586025.03        2431575.       13585625.
      2432224.96     13585225.02
#Sta/Elev= 30
  4434.3  333.56    4612  334.02  4816.2  334.39  4841.7  332.55  4872.7  329.06
  4943.5  330.53  4985.9   324.1  4996.5  320.84  5007.7  319.38  5013.6  320.32
  5019.2  319.16  5019.7  318.66  5027.1  319.16  5044.4   320.8  5058.7  327.61
  5065.7  328.98    5087   329.5  5123.7   327.2  5218.4  329.44    5364  327.02
  5386.4  322.85  5392.3   322.9  5399.2  320.12  5413.6  320.84    5429  327.83
  5450.9  330.46  5575.4  339.44  5624.2  340.86  5660.7  339.41  5763.2  339.54
#Mann= 7 ,-1 , 0
  4434.3     .12       0    4612      .1       0  4841.7     .12       0
  5019.2     .05       0  5027.1     .12       0  5450.9     .07       0
  5660.7     .05       0
Bank Sta=5019.2,5027.1
XS Rating Curve= 0 ,0
Exp/Cntr=0.3,0.1

Type RM Length L Ch R = 1 ,1814    ,424,424,424
BEGIN DESCRIPTION:
Stream0792 4.0
END DESCRIPTION:
XS GIS Cut Line= 3
      2431475.01     13586324.99        2431875.       13585925.
      2432175.01     13585774.99
#Sta/Elev= 30
  4438.7  334.09  4727.3  334.56  4735.7  334.57  4749.8  332.75    4764  326.43
  4905.4   326.6  4933.7  324.95  4947.8  326.78  4976.1  319.32  4986.3  313.51
  4986.8  313.01  4994.2  313.51  5000.8  319.22  5007.2  319.22  5012.8   322.6
  5038.9  325.06  5057.5  326.97  5107.2  325.46  5138.5  324.34  5146.9  320.77
  5152.5  320.74  5160.9  317.13  5169.3  316.73  5174.9  317.31  5183.3  321.53
    5214  325.92    5242  326.33  5272.7  330.66    5309  332.34  5339.8   335.4
#Mann= 6 ,-1 , 0
  4438.7     .12       0  4727.3      .1       0  4986.3     .05       0
  4994.2      .1       0  5038.9     .12       0  5107.2     .07       0
Bank Sta=4986.3,4994.2
XS Rating Curve= 0 ,0
Exp/Cntr=0.3,0.1