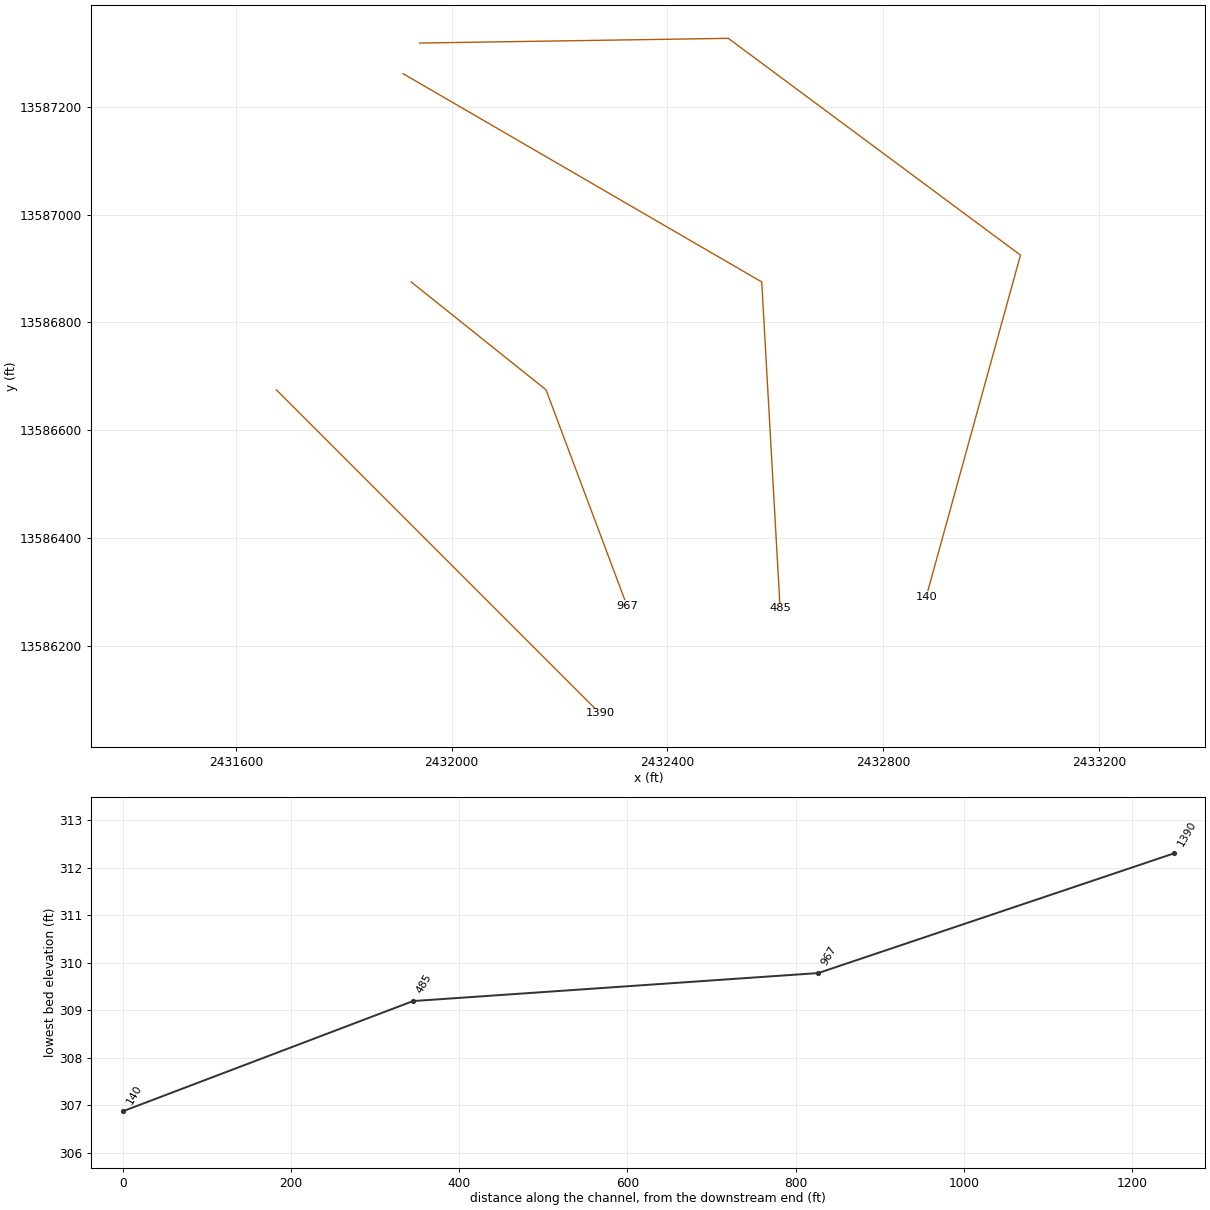
HEC-RAS study Stream0792.prj: Stream0792 Base Level Engineering

--- Stream0792.g01 (geometry) --- (continued)

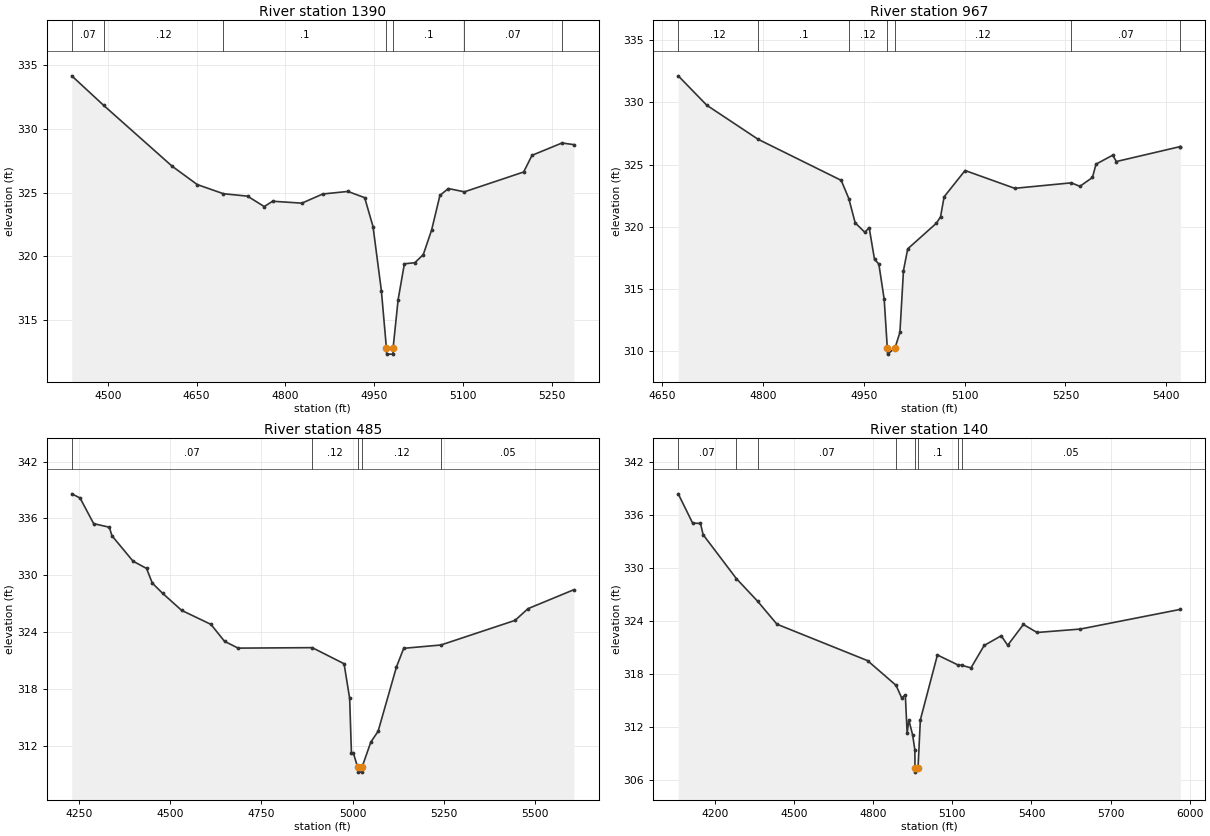
Type RM Length L Ch R = 1 ,1390    ,423,423,423
BEGIN DESCRIPTION:
Stream0792 3.0
END DESCRIPTION:
XS GIS Cut Line= 3
      2431675.01     13586674.99        2432075.       13586275.
      2432274.99     13586075.01
#Sta/Elev= 30
  4439.1  334.18  4493.2  331.85  4608.8  327.07  4651.2  325.63  4695.5  324.91
  4736.1  324.72  4764.4   323.9  4778.5  324.32    4828  324.17  4863.3  324.89
  4905.8  325.09  4934.1   324.6  4948.2  322.33  4962.3   317.3  4970.8   312.8
  4971.3   312.3  4981.7   312.3  4982.2   312.8  4990.6  316.57  5001.2   319.4
  5018.9  319.49  5033.1  320.12  5047.2  322.05  5061.3  324.78  5075.5  325.32
  5102.6  325.06  5202.8  326.62  5216.9  327.93  5267.6   328.9  5287.6  328.77
#Mann= 7 ,-1 , 0
  4439.1     .07       0  4493.2     .12       0  4695.5      .1       0
  4970.8     .05       0  4982.2      .1       0  5102.6     .07       0
  5267.6     .05       0
Bank Sta=4970.8,4982.2
XS Rating Curve= 0 ,0
Exp/Cntr=0.3,0.1

Type RM Length L Ch R = 1 ,967     ,482,482,482
BEGIN DESCRIPTION:
Stream0792 2.0
END DESCRIPTION:
XS GIS Cut Line= 3
      2431924.97     13586875.03        2432175.       13586675.
        2432325.       13586275.
#Sta/Elev= 30
  4673.6  332.12  4716.1  329.76  4792.4  327.03  4916.2  323.73  4927.5  322.27
    4937  320.32  4951.4  319.56  4957.8  319.94  4965.8  317.38  4972.2  317.02
  4980.2  314.18  4984.8  310.28  4985.3  309.78  4996.3  310.28  5003.6  311.52
  5008.9  316.49  5015.2  318.23  5057.9  320.29  5064.1  320.81  5069.4  322.41
  5100.6  324.52  5174.5  323.09  5258.8  323.53  5271.5  323.25  5290.2  323.96
  5295.5  325.03  5320.4  325.75  5325.8  325.24  5420.9  326.44    5421  326.44
#Mann= 7 ,-1 , 0
  4673.6     .12       0  4792.4      .1       0  4927.5     .12       0
  4984.8     .05       0  4996.3     .12       0  5258.8     .07       0
  5420.9     .05       0
Bank Sta=4984.8,4996.3
XS Rating Curve= 0 ,0
Exp/Cntr=0.3,0.1

Type RM Length L Ch R = 1 ,485     ,345,345,345
BEGIN DESCRIPTION:
Stream0792 1.0
END DESCRIPTION:
XS GIS Cut Line= 3
      2431909.98     13587261.19        2432575.       13586875.
      2432609.09     13586269.68
#Sta/Elev= 30
  4230.9  338.59  4253.6  338.15  4290.9  335.44  4333.9  335.06  4340.8  334.17
  4398.6  331.48  4435.7  330.71  4451.5  329.16  4479.5  328.09  4531.8  326.28
  4612.1   324.8  4649.3  323.01  4686.6  322.29  4889.6  322.34  4976.8  320.64
  4992.1  316.97    4997  311.18  5002.4  311.18  5014.2  309.69  5014.7  309.19
  5025.3  309.19  5025.8  309.69    5050  312.36    5070   313.5  5120.1  320.28
  5140.1  322.27  5242.1  322.62  5445.1  325.22  5480.7  326.46  5606.2  328.46
#Mann= 5 ,-1 , 0
  4230.9     .07       0  4889.6     .12       0  5014.2     .05       0
  5025.8     .12       0  5242.1     .05       0
Bank Sta=5014.2,5025.8
XS Rating Curve= 0 ,0
Exp/Cntr=0.3,0.1

Type RM Length L Ch R = 1 ,140     ,0,0,0
BEGIN DESCRIPTION:
XS7735
END DESCRIPTION:
XS GIS Cut Line= 4
      2431940.65     13587317.97      2432512.99     13587326.71
      2433054.78     13586924.73      2432880.02     13586291.22
#Sta/Elev= 30
  4060.3  338.42  4114.7  335.11  4144.7  335.06  4154.7  333.79  4280.8  328.81
  4361.2  326.25  4434.7  323.64  4778.3  319.51  4886.4  316.71  4907.7  315.29
  4921.6  315.62  4928.5  311.28  4934.8  312.79  4949.4  311.07  4957.8  309.37
  4958.2  307.37  4958.7  306.87  4969.8  307.37  4978.6   312.8  5043.3  320.15
  5119.8  319.04  5136.7  318.97  5170.6  318.69  5220.6  321.23  5285.3  322.33
  5309.8  321.25  5369.3  323.61  5421.2   322.7  5585.2  323.09  5964.5  325.32
#Mann= 8 ,-1 , 0
  4060.3     .07       0  4280.8     .12       0  4361.2     .07       0
  4886.4      .1       0  4958.2     .05       0  4969.8      .1       0
  5119.8     .07       0  5136.7     .05       0
Bank Sta=4958.2,4969.8
XS Rating Curve= 0 ,0
Exp/Cntr=0.3,0.1

Chan Stop Cuts=-1
Use User Specified Reach Order=0
Composite Channel Slope=5