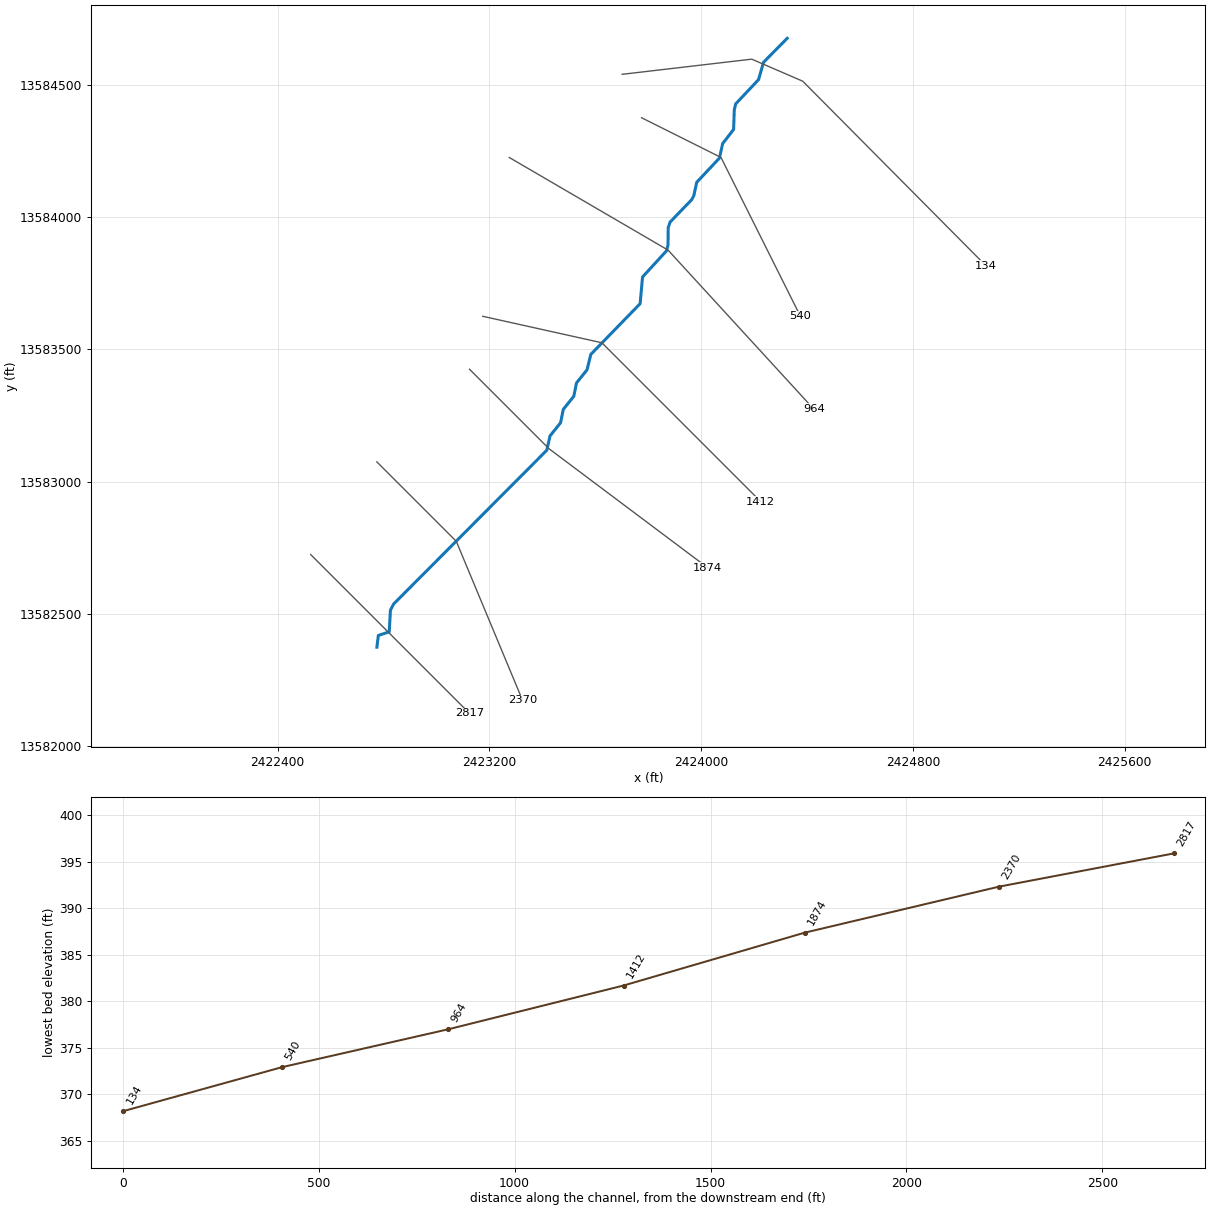
--- Stream0793.prj (project) ---

Proj Title=Stream0793 Base Level Engineering
Current Plan=p01
Default Exp/Contr=0.3,0.1
English Units
Geom File=g01
Flow File=f01
Plan File=p01
BEGIN DESCRIPTION:
Stream0793
END DESCRIPTION:

--- Stream0793.p01 (plan) ---

Plan Title=Multiple Run
Short Identifier=Multiple
Geom File=g01
Flow File=f01
Subcritical Flow
K Sum by GR= 0
Std Step Tol= 0.01
Critical Tol= 0.01
Num of Std Step Trials= 20
Max Error Tol= 0.3
Flow Tol Ratio= 0.001
Split Flow NTrial= 30
Split Flow Tol= 0.02
Split Flow Ratio= 0.02
Log Output Level= 0
Friction Slope Method= 1
Unsteady Friction Slope Method= 2
Unsteady Bridges Friction Slope Method= 1
Parabolic Critical Depth
Global Vel Dist=  1 , 1 , 1
Global Log Level= 0
CheckData=True
Encroach Param= -1, 0, 0, 0
BEGIN DESCRIPTION:
Multiple Run
END DESCRIPTION:

--- Stream0793.f01 (steady flow) ---

Flow Title=Multiple
Number of Profiles=7
Profile Names=10-year,25-year,50-year,1pct_min,100-year,1pct_plu,500-year
River Rch & RM= Stream0793,Reach-1,2817
     490     785    1051     683    1362    2718    2266
Boundary for River Rch & Prof#=Stream0793,Reach-1,1
Up Type=0
Dn Type=3
Dn Slope=0.005
Boundary for River Rch & Prof#=Stream0793,Reach-1,2
Up Type=0
Dn Type=3
Dn Slope=0.005
Boundary for River Rch & Prof#=Stream0793,Reach-1,3
Up Type=0
Dn Type=3
Dn Slope=0.005
Boundary for River Rch & Prof#=Stream0793,Reach-1,4
Up Type=0
Dn Type=3
Dn Slope=0.005
Boundary for River Rch & Prof#=Stream0793,Reach-1,5
Up Type=0
Dn Type=3
Dn Slope=0.005
Boundary for River Rch & Prof#=Stream0793,Reach-1,6
Up Type=0
Dn Type=3
Dn Slope=0.005
Boundary for River Rch & Prof#=Stream0793,Reach-1,7
Up Type=0
Dn Type=3
Dn Slope=0.005

--- Stream0793.g01 (geometry) ---

Geom Title=Existing Conditions

River Reach=Stream0793,Reach-1
Reach XY= 30
      2422775.00     13582375.00      2422780.60     13582419.39
      2422821.77     13582433.16      2422826.19     13582514.42
      2422838.41     13582538.28      2423416.86     13583118.94
      2423429.19     13583173.26      2423468.92     13583222.80
      2423479.16     13583273.28      2423518.92     13583322.80
      2423529.16     13583373.28      2423568.90     13583422.81
      2423583.14     13583481.06      2423769.48     13583672.57
      2423778.63     13583773.50      2423869.46     13583872.58
      2423874.86     13583895.06      2423875.53     13583959.78
      2423882.88     13583981.16      2423964.20     13584065.33
      2423972.46     13584081.05      2423983.18     13584131.04
      2424069.16     13584222.71      2424081.14     13584277.17
      2424122.67     13584330.97      2424125.13     13584404.95
      2424130.54     13584427.42      2424216.83     13584518.96
      2424235.72     13584584.70      2424325.00     13584675.00

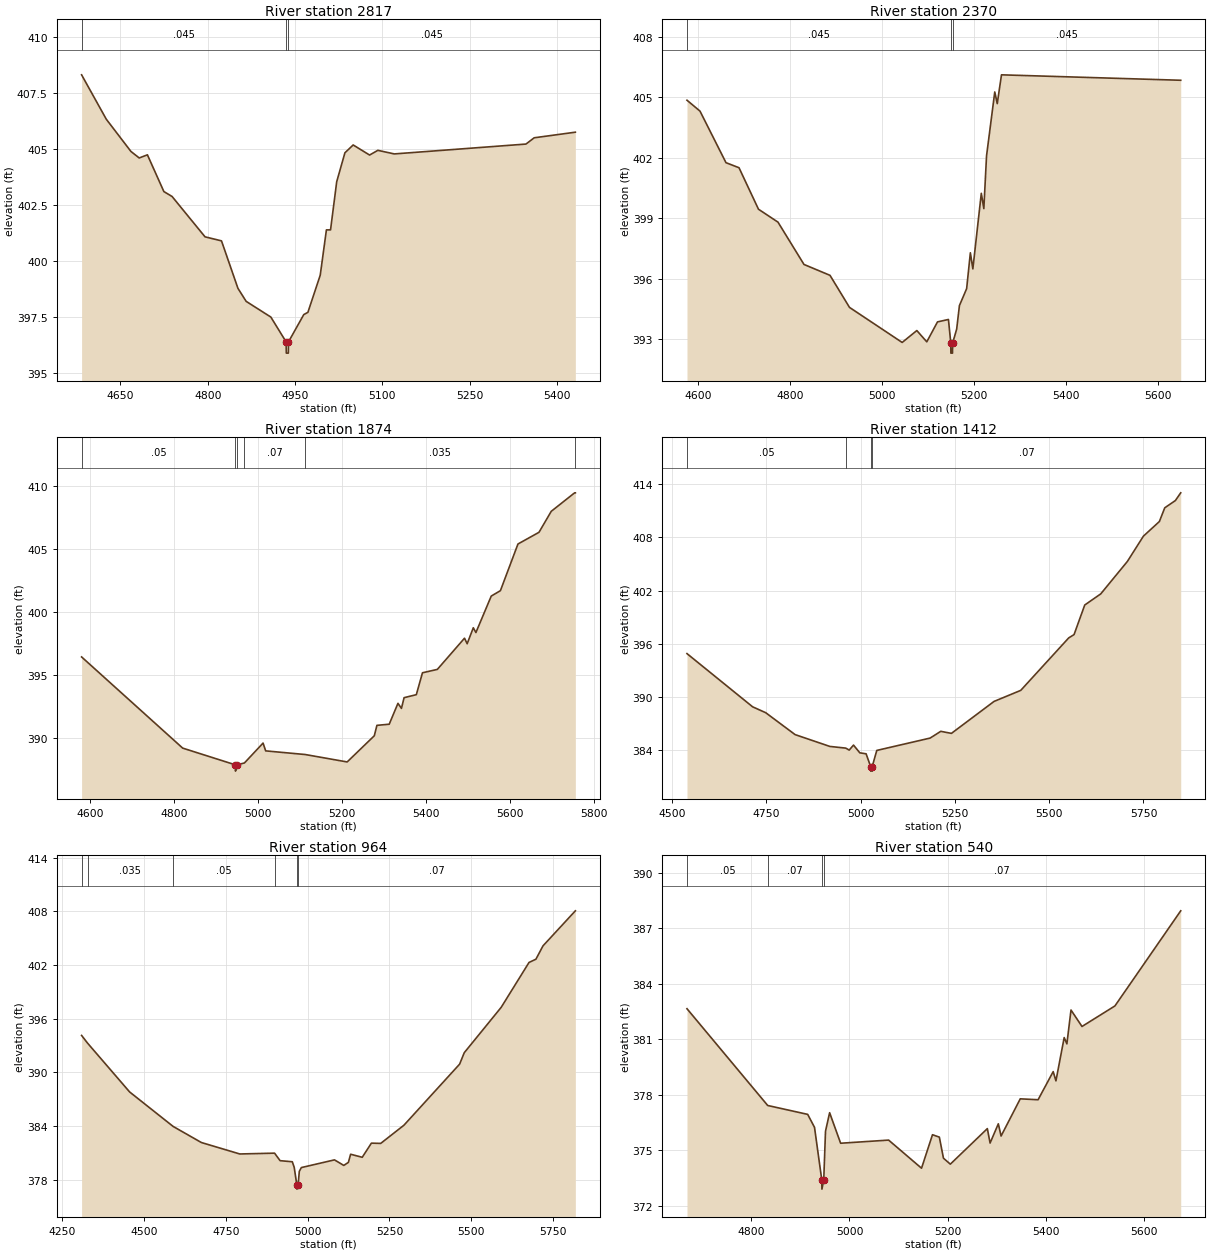
Type RM Length L Ch R = 1,2817,447,447,447
BEGIN DESCRIPTION:
Stream0793 6.0
END DESCRIPTION:
XS GIS Cut Line= 3
      2422525.02     13582724.98      2422825.00     13582425.00
      2423125.00     13582125.00
#Sta/Elev= 30
  4583.2  408.30  4625.6  406.32  4668.0  404.88  4682.2  404.59  4696.3  404.73
  4724.6  403.09  4738.7  402.87  4795.3  401.07  4823.6  400.89  4851.9  398.77
  4866.0  398.19  4908.4  397.49  4934.7  396.38  4935.0  395.88  4938.5  395.88
  4938.7  396.38  4965.0  397.60  4972.1  397.70  4993.3  399.36  5003.9  401.38
  5011.0  401.38  5021.6  403.53  5035.7  404.82  5049.9  405.17  5078.1  404.72
  5092.3  404.93  5120.6  404.77  5346.8  405.21  5361.0  405.49  5431.7  405.74
#Mann=3,-1,0
  4583.2   0.045       0  4934.7   0.045       0  4938.7   0.045       0
Bank Sta=4934.7,4938.7
Exp/Cntr=0.3,0.1

Type RM Length L Ch R = 1,2370,496,496,496
BEGIN DESCRIPTION:
Stream0793 5.0
END DESCRIPTION:
XS GIS Cut Line= 3
      2422774.97     13583075.03      2423075.00     13582775.00
      2423325.00     13582175.01
#Sta/Elev= 30
  4575.7  404.85  4604.0  404.31  4660.6  401.75  4688.9  401.50  4731.3  399.44
  4773.7  398.80  4830.3  396.70  4886.9  396.16  4929.3  394.57  5043.9  392.83
  5075.8  393.42  5097.5  392.86  5120.8  393.85  5144.6  393.97  5149.7  392.80
  5149.9  392.30  5153.4  392.30  5153.7  392.80  5162.5  393.49  5168.5  394.66
  5184.2  395.50  5192.3  397.28  5197.7  396.48  5216.1  400.23  5221.6  399.47
  5227.5  402.09  5245.4  405.26  5250.8  404.68  5260.0  406.11  5650.0  405.84
#Mann=3,-1,0
  4575.7   0.045       0  5149.7   0.045       0  5153.7   0.045       0
Bank Sta=5149.7,5153.7
Exp/Cntr=0.3,0.1

Type RM Length L Ch R = 1,1874,462,462,462
BEGIN DESCRIPTION:
Stream0793 4.0
END DESCRIPTION:
XS GIS Cut Line= 3
      2423124.99     13583425.01      2423425.00     13583125.00
      2424025.02     13582674.98
#Sta/Elev= 30
  4580.5  396.43  4820.9  389.18  4946.2  387.85  4946.5  387.35  4950.2  387.85
  4967.8  388.00  5012.1  389.58  5018.3  388.96  5112.4  388.67  5212.1  388.08
  5276.6  390.16  5282.9  390.99  5312.1  391.08  5332.9  392.74  5341.2  392.34
  5347.5  393.19  5376.6  393.43  5391.2  395.17  5426.6  395.44  5491.2  397.92
  5497.5  397.48  5512.1  398.75  5518.3  398.37  5554.8  401.27  5576.6  401.70
  5618.3  405.41  5668.3  406.34  5697.5  408.01  5753.1  409.48  5754.8  409.48
#Mann=6,-1,0
  4580.5    0.05       0  4946.2    0.05       0  4950.2    0.05       0
  4967.8    0.07       0  5112.4   0.035       0  5753.1    0.12       0
Bank Sta=4946.2,4950.2
Exp/Cntr=0.3,0.1

Type RM Length L Ch R = 1,1412,448,448,448
BEGIN DESCRIPTION:
Stream0793 3.0
END DESCRIPTION:
XS GIS Cut Line= 3
      2423175.02     13583624.99      2423625.00     13583525.00
      2424225.01     13582924.99
#Sta/Elev= 30
  4539.3  394.90  4713.4  388.91  4748.0  388.25  4826.1  385.78  4918.3  384.45
  4960.4  384.26  4969.5  384.04  4981.0  384.60  4997.7  383.73  5014.4  383.62
  5026.5  382.17  5026.8  381.67  5030.3  381.67  5030.5  382.17  5042.7  384.00
  5184.1  385.39  5212.4  386.15  5240.7  385.92  5353.8  389.52  5424.5  390.76
  5551.8  396.67  5565.9  397.04  5594.2  400.37  5636.6  401.62  5707.4  405.28
  5749.8  408.12  5792.2  409.77  5806.4  411.31  5834.6  412.13  5848.8  413.00
#Mann=4,-1,0
  4539.3    0.05       0  4960.4    0.07       0  5026.5    0.05       0
  5030.5    0.07       0
Bank Sta=5026.5,5030.5
Exp/Cntr=0.3,0.1

Type RM Length L Ch R = 1,964,424,424,424
BEGIN DESCRIPTION:
Stream0793 2.0
END DESCRIPTION:
XS GIS Cut Line= 3
      2423275.02     13584224.99      2423875.00     13583875.00
      2424424.97     13583275.03
#Sta/Elev= 30
  4309.4  394.14  4327.6  393.28  4456.2  387.82  4589.0  383.97  4675.3  382.17
  4792.7  380.89  4899.0  380.98  4915.9  380.14  4953.1  380.02  4958.9  379.41
  4966.9  377.46  4967.1  376.96  4970.9  377.46  4974.6  378.95  4980.8  379.37
  5082.0  380.23  5110.4  379.61  5124.5  379.95  5131.3  380.86  5166.8  380.52
  5194.8  382.10  5223.2  382.07  5294.1  384.10  5464.3  390.93  5478.5  392.21
  5591.3  397.28  5676.4  402.30  5697.4  402.66  5719.0  404.15  5817.9  408.07
#Mann=6,-1,0
  4309.4    0.05       0  4327.6   0.035       0  4589.0    0.05       0
  4899.0    0.07       0  4966.9    0.05       0  4970.9    0.07       0
Bank Sta=4966.9,4970.9
Exp/Cntr=0.3,0.1

Type RM Length L Ch R = 1,540,406,406,406
BEGIN DESCRIPTION:
Stream0793 1.0
END DESCRIPTION:
XS GIS Cut Line= 3
      2423775.00     13584375.00      2424075.00     13584225.00
      2424374.98     13583625.03
#Sta/Elev= 30
  4668.9  382.64  4833.4  377.41  4914.9  376.93  4928.8  376.23  4943.6  373.39
  4943.9  372.89  4947.6  373.39  4951.2  376.02  4959.6  377.02  4982.0  375.37
  5079.8  375.54  5146.9  374.02  5169.2  375.83  5183.2  375.70  5191.6  374.56
  5205.6  374.24  5281.0  376.16  5286.6  375.38  5303.4  376.42  5309.0  375.76
  5348.1  377.77  5384.4  377.72  5415.2  379.24  5420.8  378.74  5437.6  381.08
  5443.1  380.74  5451.5  382.57  5473.9  381.68  5541.0  382.79  5675.1  387.93
#Mann=4,-1,0
  4668.9    0.05       0  4833.4    0.07       0  4943.6    0.05       0
  4947.6    0.07       0
Bank Sta=4943.6,4947.6
Exp/Cntr=0.3,0.1

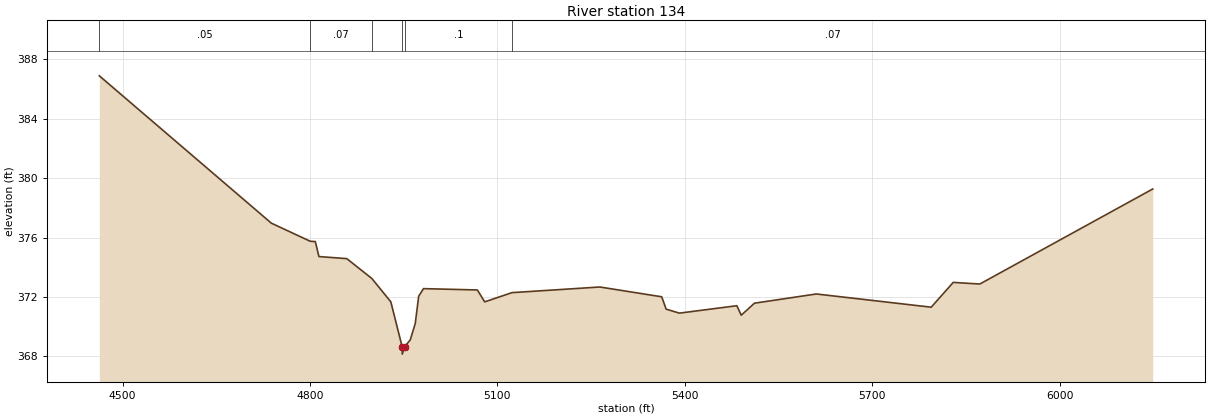
Type RM Length L Ch R = 1,134,0,0,0
BEGIN DESCRIPTION:
XS7736
END DESCRIPTION:
XS GIS Cut Line= 4
      2423701.60     13584539.07      2424191.15     13584596.35
      2424383.85     13584513.02      2425076.59     13583815.08
#Sta/Elev= 30
  4462.9  386.89  4738.2  376.97  4800.5  375.75  4808.6  375.73  4814.4  374.72
  4859.0  374.58  4899.2  373.24  4929.5  371.67  4947.6  368.65  4947.8  368.15
  4951.6  368.65  4960.6  369.11  4968.6  370.21  4974.1  372.05  4981.8  372.56
  5068.0  372.47  5079.8  371.67  5123.4  372.29  5264.1  372.67  5363.1  372.01
  5370.2  371.18  5391.4  370.91  5483.4  371.41  5490.4  370.77  5511.6  371.58
  5610.6  372.20  5794.5  371.31  5829.8  372.98  5872.3  372.87  6149.1  379.27
#Mann=6,-1,0
  4462.9    0.05       0  4800.5    0.07       0  4899.2     0.1       0
  4947.6    0.05       0  4951.6     0.1       0  5123.4    0.07       0
Bank Sta=4947.6,4951.6
Exp/Cntr=0.3,0.1

Chan Stop Cuts=-1