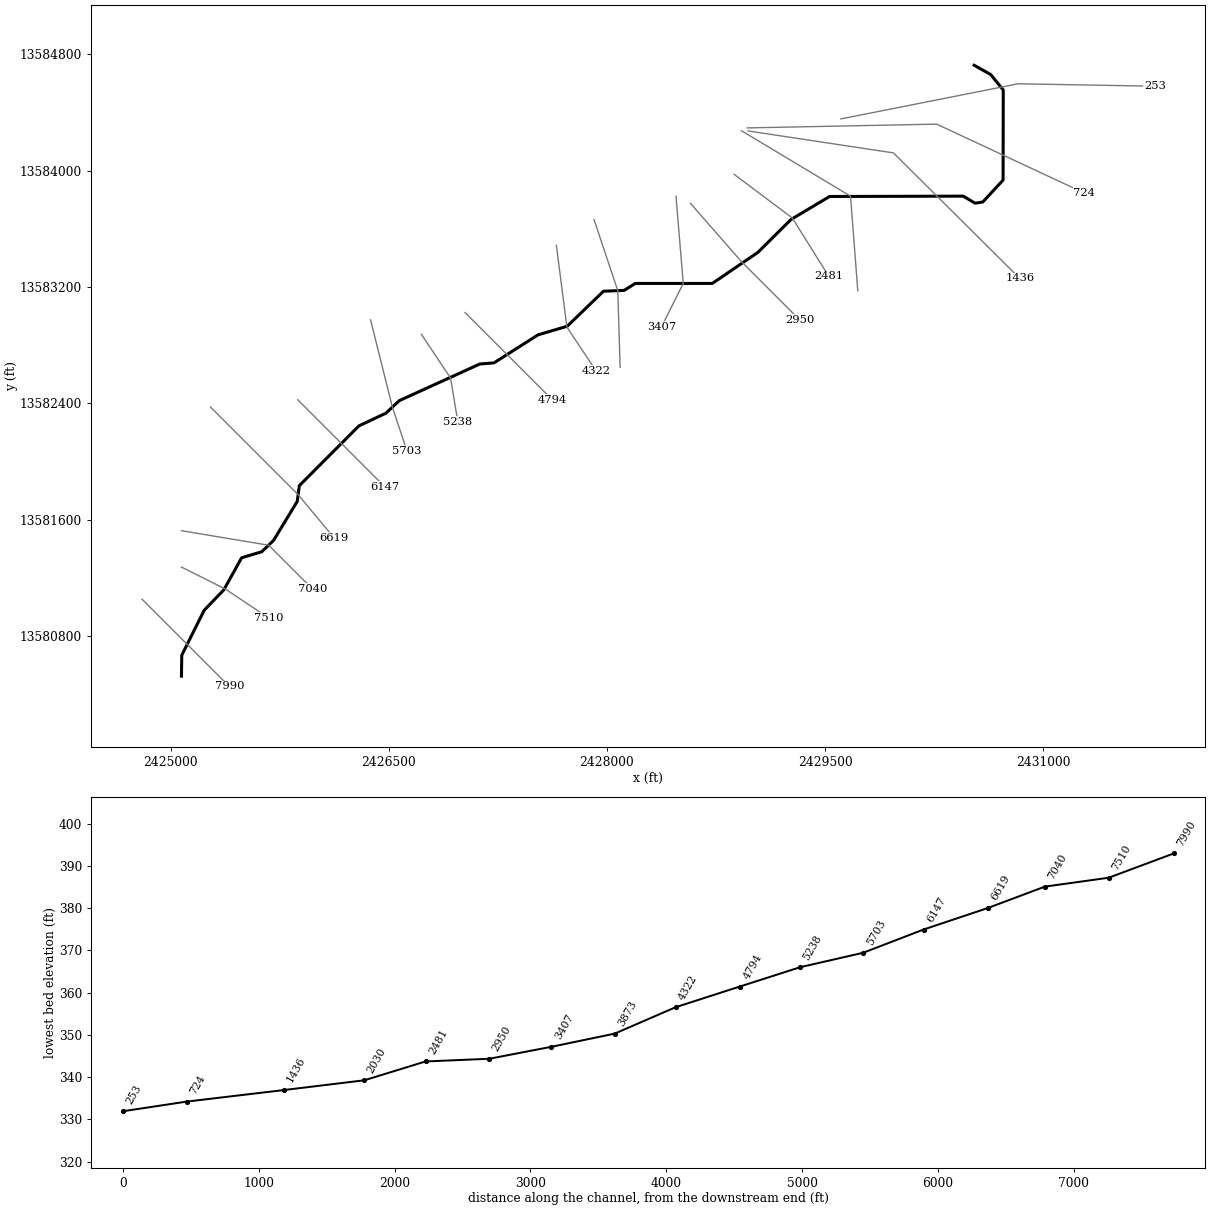
--- Stream0794.prj (project) ---

Proj Title=Stream0794 Base Level Engineering
Current Plan=p01
Default Exp/Contr=0.3,0.1
English Units
Geom File=g01
Flow File=f01
Plan File=p01
BEGIN DESCRIPTION:
Stream0794
END DESCRIPTION:

--- Stream0794.p01 (plan) ---

Plan Title=Multiple Run
Short Identifier=Multiple
Geom File=g01
Flow File=f01
Subcritical Flow
K Sum by GR= 0
Std Step Tol= 0.01
Critical Tol= 0.01
Num of Std Step Trials= 20
Max Error Tol= 0.3
Flow Tol Ratio= 0.001
Split Flow NTrial= 30
Split Flow Tol= 0.02
Split Flow Ratio= 0.02
Log Output Level= 0
Friction Slope Method= 1
Unsteady Friction Slope Method= 2
Unsteady Bridges Friction Slope Method= 1
Parabolic Critical Depth
Global Vel Dist=  1 , 1 , 1
Global Log Level= 0
CheckData=True
Encroach Param= -1, 0, 0, 0
BEGIN DESCRIPTION:
Multiple Run
END DESCRIPTION:

--- Stream0794.f01 (steady flow) ---

Flow Title=Multiple
Number of Profiles=7
Profile Names=10-year,25-year,50-year,1pct_min,100-year,1pct_plu,500-year
River Rch & RM= Stream0794,Reach-1,7990
     565     914    1231     804    1603    3199    2694
River Rch & RM= Stream0794,Reach-1,2950
     931    1550    2127    1414    2821    5628    4914
Boundary for River Rch & Prof#=Stream0794,Reach-1,1
Up Type=0
Dn Type=3
Dn Slope=0.005
Boundary for River Rch & Prof#=Stream0794,Reach-1,2
Up Type=0
Dn Type=3
Dn Slope=0.005
Boundary for River Rch & Prof#=Stream0794,Reach-1,3
Up Type=0
Dn Type=3
Dn Slope=0.005
Boundary for River Rch & Prof#=Stream0794,Reach-1,4
Up Type=0
Dn Type=3
Dn Slope=0.005
Boundary for River Rch & Prof#=Stream0794,Reach-1,5
Up Type=0
Dn Type=3
Dn Slope=0.005
Boundary for River Rch & Prof#=Stream0794,Reach-1,6
Up Type=0
Dn Type=3
Dn Slope=0.005
Boundary for River Rch & Prof#=Stream0794,Reach-1,7
Up Type=0
Dn Type=3
Dn Slope=0.005

--- Stream0794.g01 (geometry) ---

Geom Title=Existing Conditions

River Reach=Stream0794,Reach-1
Reach XY= 30
      2425075.00     13580525.00      2425077.20     13580669.09
      2425230.83     13580977.30      2425366.84     13581118.95
      2425488.46     13581338.63      2425627.44     13581380.52
      2425708.36     13581458.29      2425871.17     13581726.59
      2425885.52     13581834.79      2426294.84     13582245.39
      2426481.05     13582333.16      2426572.71     13582419.15
      2427126.58     13582671.17      2427223.42     13582678.83
      2427526.50     13582871.38      2427727.30     13582930.83
      2427976.47     13583171.46      2428119.06     13583177.27
      2428195.03     13583224.93      2428725.00     13583225.00
      2429038.21     13583438.63      2429265.32     13583664.22
      2429530.93     13583822.76      2430450.09     13583825.19
      2430531.14     13583776.78      2430584.68     13583785.19
      2430723.95     13583935.43      2430725.04     13584555.02
      2430638.26     13584661.44      2430525.00     13584725.00

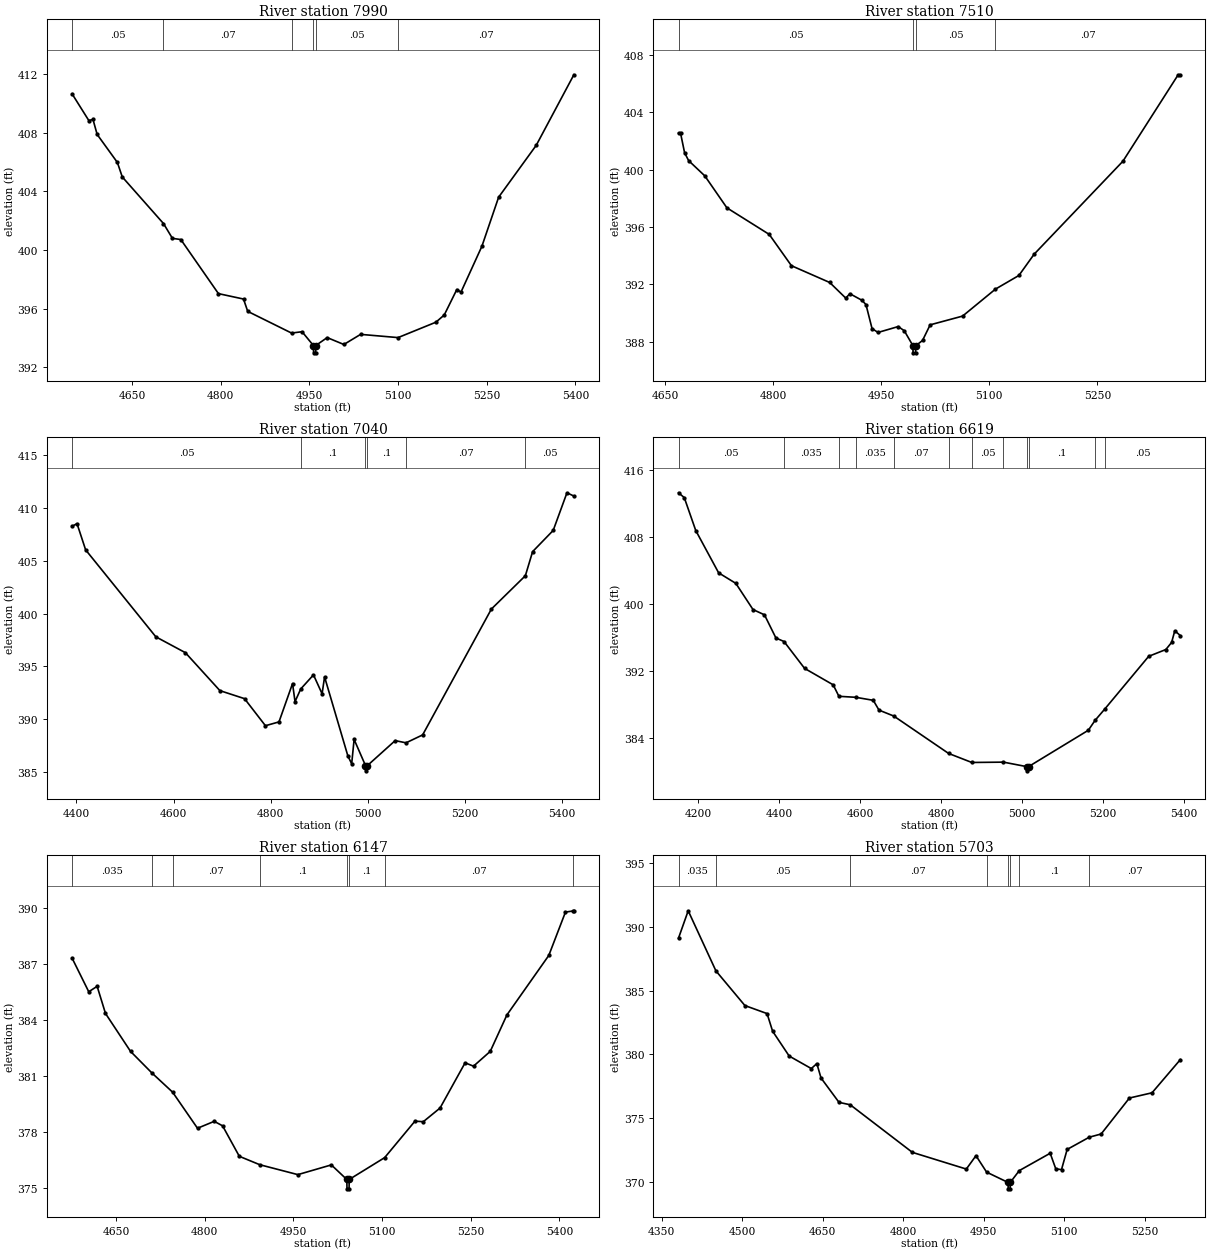
Type RM Length L Ch R = 1,7990,480,480,480
BEGIN DESCRIPTION:
Stream0794 14.0
END DESCRIPTION:
XS GIS Cut Line= 3
      2424804.15     13581054.18      2425104.17     13580754.17
      2425404.13     13580454.20
#Sta/Elev= 30
  4548.8  410.66  4577.1  408.84  4584.2  408.91  4591.2  407.89  4625.4  405.98
  4633.7  404.99  4703.4  401.81  4718.5  400.80  4732.7  400.72  4796.3  397.03
  4838.7  396.66  4845.8  395.82  4919.9  394.34  4937.7  394.43  4956.9  393.49
  4957.2  392.99  4960.7  392.99  4960.9  393.49  4980.2  394.03  5008.4  393.56
  5036.7  394.25  5100.0  394.03  5164.0  395.08  5178.1  395.57  5199.4  397.31
  5206.4  397.13  5241.8  400.26  5270.1  403.61  5333.7  407.15  5397.3  411.96
#Mann=6,-1,0
  4548.8    0.05       0  4703.4    0.07       0  4919.9    0.05       0
  4956.9    0.05       0  4960.9    0.05       0  5100.0    0.07       0
Bank Sta=4956.9,4960.9
Exp/Cntr=0.3,0.1

Type RM Length L Ch R = 1,7510,470,470,470
BEGIN DESCRIPTION:
Stream0794 13.0
END DESCRIPTION:
XS GIS Cut Line= 3
      2425074.98     13581275.01      2425375.00     13581125.00
      2425675.01     13580925.00
#Sta/Elev= 30
  4668.9  402.53  4671.7  402.53  4677.3  401.17  4682.9  400.62  4705.3  399.56
  4736.0  397.33  4794.7  395.48  4825.5  393.30  4878.6  392.13  4900.9  391.04
  4906.5  391.35  4923.3  390.89  4928.9  390.59  4937.3  388.92  4945.6  388.65
  4973.6  389.06  4982.0  388.77  4994.0  387.73  4994.2  387.23  4997.7  387.23
  4998.0  387.73  5007.3  388.09  5017.9  389.18  5062.9  389.79  5108.5  391.67
  5141.0  392.62  5162.1  394.10  5285.3  400.58  5361.9  406.60  5364.9  406.60
#Mann=4,-1,0
  4668.9    0.05       0  4994.0    0.05       0  4998.0    0.05       0
  5108.5    0.07       0
Bank Sta=4994,4998
Exp/Cntr=0.3,0.1

Type RM Length L Ch R = 1,7040,421,421,421
BEGIN DESCRIPTION:
Stream0794 12.0
END DESCRIPTION:
XS GIS Cut Line= 3
      2425074.98     13581525.00      2425675.00     13581425.00
      2425975.03     13581124.97
#Sta/Elev= 30
  4391.2  408.26  4401.4  408.51  4419.1  406.03  4563.6  397.80  4624.4  396.30
  4695.4  392.71  4746.1  391.95  4789.1  389.39  4817.0  389.75  4844.9  393.38
  4850.0  391.67  4861.8  392.87  4888.0  394.20  4905.7  392.41  4910.8  394.01
  4958.9  386.51  4966.6  385.79  4971.6  388.09  4995.0  385.62  4995.2  385.12
  4999.0  385.62  5056.1  387.98  5078.4  387.77  5112.6  388.52  5254.1  400.43
  5324.0  403.58  5338.9  405.86  5381.3  407.87  5409.6  411.43  5423.8  411.12
#Mann=6,-1,0
  4391.2    0.05       0  4861.8     0.1       0  4995.0    0.05       0
  4999.0     0.1       0  5078.4    0.07       0  5324.0    0.05       0
Bank Sta=4995,4999
Exp/Cntr=0.3,0.1

Type RM Length L Ch R = 1,6619,472,472,472
BEGIN DESCRIPTION:
Stream0794 11.0
END DESCRIPTION:
XS GIS Cut Line= 3
      2425274.97     13582375.03      2425875.00     13581775.00
      2426125.01     13581474.99
#Sta/Elev= 30
  4151.5  413.28  4165.7  412.70  4194.0  408.77  4250.5  403.71  4293.0  402.45
  4335.4  399.32  4363.7  398.69  4392.0  395.92  4412.0  395.50  4462.7  392.29
  4533.4  390.32  4547.5  388.95  4589.3  388.83  4632.4  388.47  4646.5  387.30
  4683.0  386.59  4818.4  382.12  4875.7  381.04  4953.9  381.08  5011.7  380.54
  5012.0  380.04  5015.7  380.54  5163.4  384.89  5180.2  386.08  5203.9  387.42
  5312.5  393.73  5354.8  394.54  5369.1  395.39  5376.9  396.78  5390.6  396.21
#Mann=12,-1,0
  4151.5    0.05       0  4412.0   0.035       0  4547.5    0.07       0
  4589.3   0.035       0  4683.0    0.07       0  4818.4    0.12       0
  4875.7    0.05       0  4953.9     0.1       0  5011.7    0.05       0
  5015.7     0.1       0  5180.2    0.07       0  5203.9    0.05       0
Bank Sta=5011.7,5015.7
Exp/Cntr=0.3,0.1

Type RM Length L Ch R = 1,6147,444,444,444
BEGIN DESCRIPTION:
Stream0794 10.0
END DESCRIPTION:
XS GIS Cut Line= 3
      2425875.03     13582424.97      2426175.00     13582125.00
      2426475.01     13581824.99
#Sta/Elev= 30
  4575.8  387.30  4604.0  385.50  4618.2  385.79  4632.3  384.34  4674.7  382.31
  4710.7  381.16  4745.8  380.13  4787.9  378.20  4816.2  378.57  4830.3  378.33
  4858.6  376.70  4893.2  376.25  4957.6  375.72  5014.2  376.24  5040.4  375.46
  5040.7  374.96  5044.2  374.96  5044.4  375.46  5104.4  376.63  5155.6  378.58
  5169.7  378.55  5198.0  379.28  5240.4  381.70  5254.6  381.52  5282.9  382.31
  5311.1  384.26  5381.9  387.44  5410.1  389.76  5423.1  389.82  5424.3  389.83
#Mann=8,-1,0
  4575.8   0.035       0  4710.7    0.05       0  4745.8    0.07       0
  4893.2     0.1       0  5040.4    0.05       0  5044.4     0.1       0
  5104.4    0.07       0  5423.1   0.035       0
Bank Sta=5040.4,5044.4
Exp/Cntr=0.3,0.1

Type RM Length L Ch R = 1,5703,465,465,465
BEGIN DESCRIPTION:
Stream0794 9.0
END DESCRIPTION:
XS GIS Cut Line= 3
      2426375.01     13582974.95      2426525.00     13582375.00
      2426624.99     13582075.04
#Sta/Elev= 30
  4381.6  389.12  4399.6  391.26  4451.2  386.55  4505.2  383.83  4546.5  383.20
  4556.8  381.82  4587.7  379.87  4628.9  378.89  4639.2  379.28  4647.0  378.15
  4680.5  376.24  4701.4  376.05  4817.1  372.32  4917.6  371.01  4935.6  372.06
  4955.4  370.77  4995.4  369.96  4995.7  369.46  4999.2  369.46  4999.4  369.96
  5016.3  370.89  5073.8  372.25  5084.3  371.02  5094.9  370.97  5105.4  372.55
  5146.7  373.51  5168.7  373.76  5221.4  376.58  5263.5  376.99  5316.2  379.59
#Mann=8,-1,0
  4381.6   0.035       0  4451.2    0.05       0  4701.4    0.07       0
  4955.4    0.05       0  4995.4    0.05       0  4999.4    0.05       0
  5016.3     0.1       0  5146.7    0.07       0
Bank Sta=4995.4,4999.4
Exp/Cntr=0.3,0.1

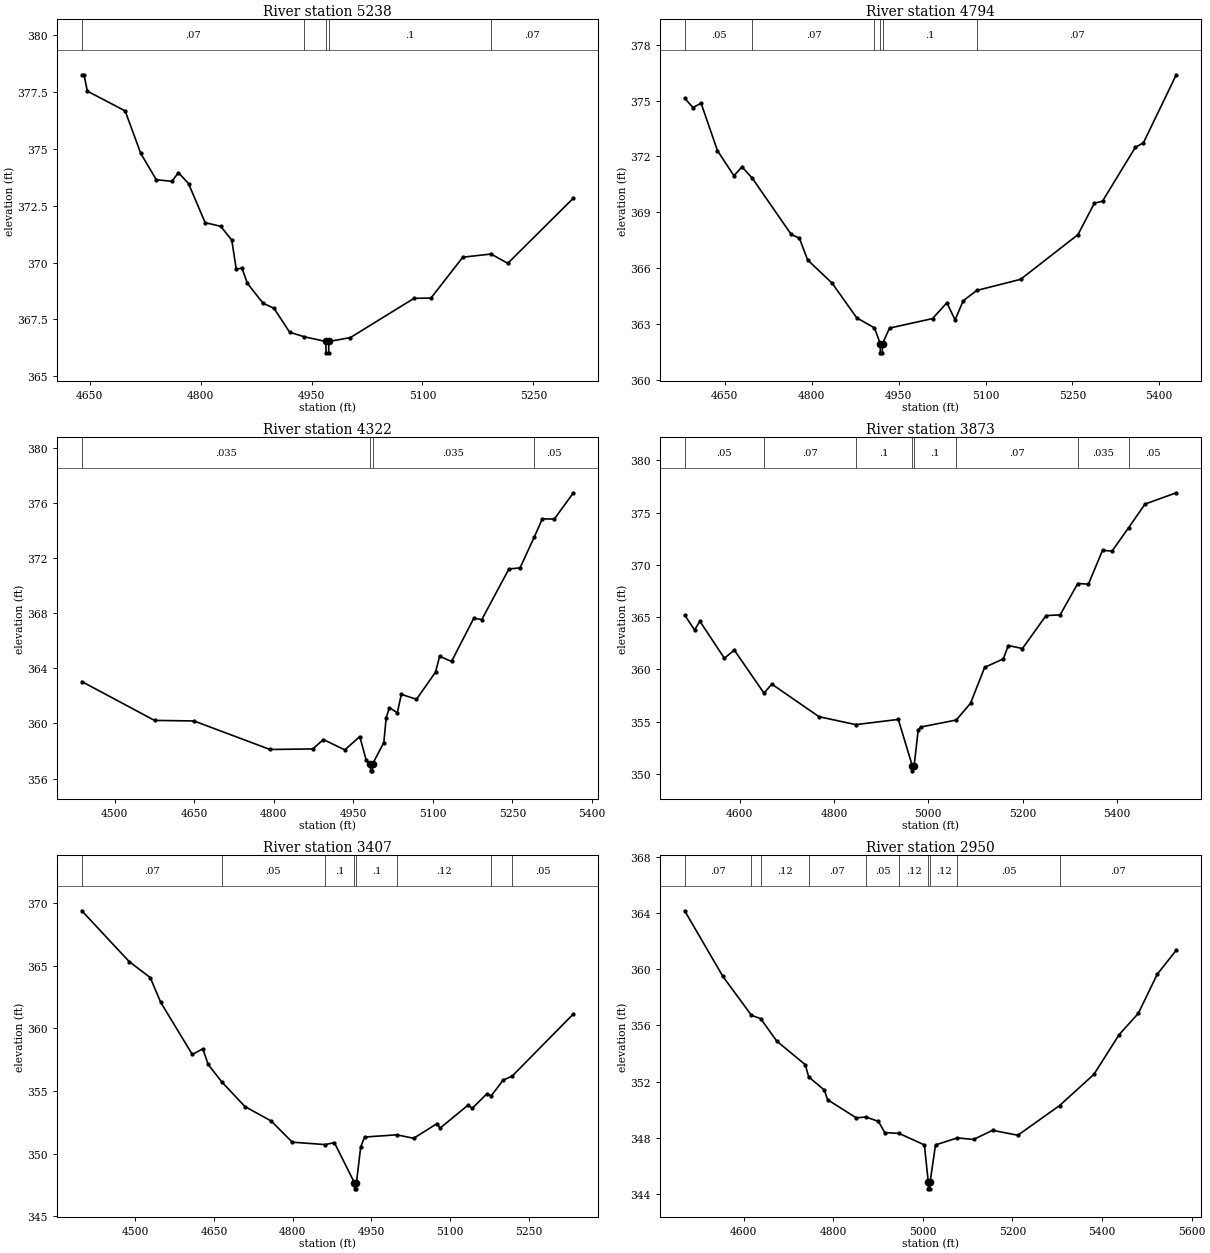
Type RM Length L Ch R = 1,5238,444,444,444
BEGIN DESCRIPTION:
Stream0794 8.0
END DESCRIPTION:
XS GIS Cut Line= 3
      2426724.98     13582875.02      2426925.00     13582575.00
      2426975.00     13582275.02
#Sta/Elev= 30
  4639.4  378.27  4642.4  378.27  4646.9  377.55  4698.0  376.68  4719.1  374.81
  4740.1  373.65  4761.1  373.58  4770.1  373.96  4783.7  373.48  4806.2  371.76
  4827.2  371.60  4842.2  370.99  4848.3  369.70  4855.8  369.77  4863.3  369.09
  4884.3  368.22  4899.3  367.99  4920.4  366.94  4939.9  366.74  4969.4  366.53
  4969.7  366.03  4973.2  366.03  4973.4  366.53  5002.5  366.70  5088.7  368.43
  5111.5  368.44  5154.6  370.24  5192.7  370.38  5215.4  369.97  5304.1  372.84
#Mann=5,-1,0
  4639.4    0.07       0  4939.9     0.1       0  4969.4    0.05       0
  4973.4     0.1       0  5192.7    0.07       0
Bank Sta=4969.4,4973.4
Exp/Cntr=0.3,0.1

Type RM Length L Ch R = 1,4794,472,472,472
BEGIN DESCRIPTION:
Stream0794 7.0
END DESCRIPTION:
XS GIS Cut Line= 3
      2427024.97     13583025.03      2427325.00     13582725.00
      2427625.02     13582424.98
#Sta/Elev= 30
  4580.7  375.13  4594.9  374.63  4609.0  374.86  4637.3  372.31  4665.6  370.97
  4679.7  371.44  4697.7  370.82  4764.6  367.81  4778.7  367.61  4792.9  366.44
  4835.3  365.19  4877.7  363.33  4908.3  362.79  4918.2  361.95  4918.4  361.45
  4921.9  361.45  4922.2  361.95  4934.3  362.78  5008.5  363.29  5033.3  364.14
  5047.4  363.22  5061.6  364.25  5084.7  364.80  5160.6  365.40  5259.6  367.80
  5287.9  369.49  5302.0  369.60  5358.6  372.49  5372.7  372.74  5429.3  376.39
#Mann=6,-1,0
  4580.7    0.05       0  4697.7    0.07       0  4908.3     0.1       0
  4918.2    0.05       0  4922.2     0.1       0  5084.7    0.07       0
Bank Sta=4918.2,4922.2
Exp/Cntr=0.3,0.1

Type RM Length L Ch R = 1,4322,449,449,449
BEGIN DESCRIPTION:
Stream0794 6.0
END DESCRIPTION:
XS GIS Cut Line= 3
      2427652.61     13583486.95      2427725.00     13582925.00
      2427924.98     13582625.04
#Sta/Elev= 30
  4437.9  363.04  4575.0  360.22  4649.4  360.18  4792.8  358.11  4873.4  358.15
  4893.6  358.83  4933.9  358.08  4962.2  359.05  4974.2  357.34  4982.3  357.06
  4982.6  356.56  4986.1  356.56  4986.3  357.06  5007.5  358.61  5012.0  360.42
  5018.0  361.14  5033.0  360.78  5040.5  362.11  5069.1  361.75  5105.1  363.73
  5112.7  364.87  5135.2  364.50  5177.3  367.64  5192.3  367.54  5243.4  371.21
  5264.4  371.29  5291.3  373.53  5306.5  374.85  5329.0  374.83  5365.0  376.74
#Mann=4,-1,0
  4437.9   0.035       0  4982.3   0.035       0  4986.3   0.035       0
  5291.3    0.05       0
Bank Sta=4982.3,4986.3
Exp/Cntr=0.3,0.1

Type RM Length L Ch R = 1,3873,466,466,466
BEGIN DESCRIPTION:
Stream0794 5.0
END DESCRIPTION:
XS GIS Cut Line= 3
      2427911.22     13583664.81      2428075.00     13583175.00
      2428091.04     13582648.72
#Sta/Elev= 30
  4483.2  365.20  4504.1  363.77  4515.4  364.61  4567.4  361.07  4588.4  361.85
  4651.5  357.73  4668.0  358.60  4768.1  355.48  4846.2  354.72  4936.4  355.22
  4966.0  350.80  4966.3  350.30  4970.0  350.80  4978.6  354.19  4983.9  354.49
  5059.3  355.16  5089.7  356.77  5119.7  360.20  5159.2  361.01  5169.8  362.29
  5199.8  362.00  5249.8  365.15  5279.8  365.22  5317.2  368.22  5339.8  368.16
  5369.8  371.40  5389.9  371.32  5425.3  373.57  5459.9  375.82  5526.2  376.90
#Mann=8,-1,0
  4483.2    0.05       0  4651.5    0.07       0  4846.2     0.1       0
  4966.0    0.05       0  4970.0     0.1       0  5059.3    0.07       0
  5317.2   0.035       0  5425.3    0.05       0
Bank Sta=4966,4970
Exp/Cntr=0.3,0.1

Type RM Length L Ch R = 1,3407,457,457,457
BEGIN DESCRIPTION:
Stream0794 4.0
END DESCRIPTION:
XS GIS Cut Line= 3
      2428475.00     13583825.03      2428525.00     13583225.00
      2428375.01     13582925.02
#Sta/Elev= 30
  4397.9  369.41  4488.2  365.35  4528.4  364.07  4548.4  362.09  4608.7  357.92
  4628.7  358.38  4638.8  357.13  4664.6  355.74  4709.0  353.76  4759.2  352.60
  4799.3  350.91  4861.9  350.72  4879.6  350.87  4917.7  347.68  4918.0  347.18
  4921.5  347.18  4921.7  347.68  4929.8  350.53  4937.3  351.32  4998.7  351.50
  5030.8  351.22  5075.5  352.40  5081.1  352.03  5134.2  353.86  5142.6  353.62
  5170.5  354.78  5178.8  354.62  5201.3  355.86  5219.1  356.21  5335.4  361.16
#Mann=8,-1,0
  4397.9    0.07       0  4664.6    0.05       0  4861.9     0.1       0
  4917.7    0.05       0  4921.7     0.1       0  4998.7    0.12       0
  5178.8    0.07       0  5219.1    0.05       0
Bank Sta=4917.7,4921.7
Exp/Cntr=0.3,0.1

Type RM Length L Ch R = 1,2950,469,469,469
BEGIN DESCRIPTION:
Stream0794 3.0
END DESCRIPTION:
XS GIS Cut Line= 3
      2428575.00     13583775.01      2428925.00     13583375.00
      2429325.00     13582975.00
#Sta/Elev= 30
  4468.5  364.17  4553.5  359.50  4617.5  356.72  4638.1  356.48  4674.0  354.88
  4737.6  353.20  4745.2  352.33  4780.3  351.39  4787.4  350.70  4851.5  349.41
  4872.9  349.47  4900.8  349.16  4915.1  348.36  4947.0  348.30  5003.5  347.48
  5012.1  344.85  5012.3  344.35  5016.0  344.35  5016.3  344.85  5028.3  347.48
  5076.9  347.98  5113.2  347.87  5155.6  348.52  5212.1  348.17  5305.4  350.29
  5381.9  352.51  5438.4  355.35  5480.8  356.85  5523.3  359.65  5565.7  361.36
#Mann=10,-1,0
  4468.5    0.07       0  4617.5    0.05       0  4638.1    0.12       0
  4745.2    0.07       0  4872.9    0.05       0  4947.0    0.12       0
  5012.1    0.05       0  5016.3    0.12       0  5076.9    0.05       0
  5305.4    0.07       0
Bank Sta=5012.1,5016.3
Exp/Cntr=0.3,0.1

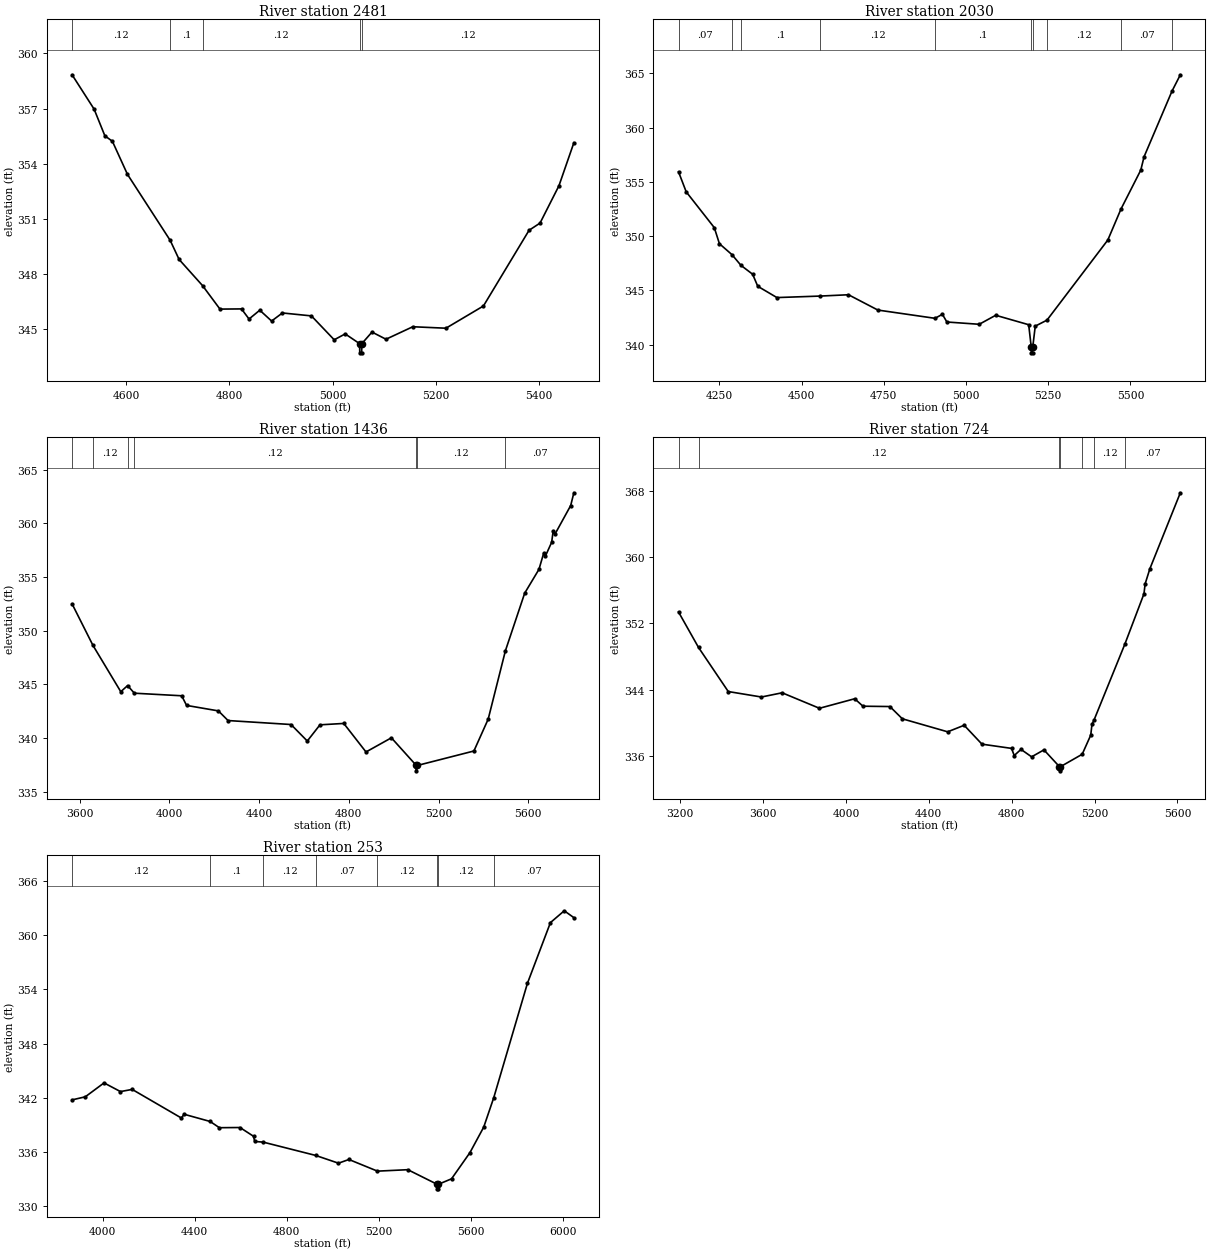
Type RM Length L Ch R = 1,2481,451,451,451
BEGIN DESCRIPTION:
Stream0794 2.0
END DESCRIPTION:
XS GIS Cut Line= 3
      2428875.01     13583974.99      2429275.00     13583675.00
      2429525.01     13583274.98
#Sta/Elev= 30
  4495.6  358.84  4538.3  356.97  4559.1  355.52  4573.7  355.22  4602.9  353.42
  4685.6  349.83  4702.9  348.79  4748.2  347.37  4782.0  346.09  4823.7  346.10
  4838.3  345.55  4859.1  346.03  4882.0  345.44  4902.9  345.88  4959.1  345.72
  5003.2  344.42  5024.5  344.74  5052.4  344.21  5052.7  343.71  5056.4  343.71
  5056.7  344.21  5076.4  344.84  5103.5  344.45  5155.4  345.13  5219.6  345.05
  5292.2  346.26  5380.6  350.38  5401.8  350.77  5438.4  352.80  5467.3  355.14
#Mann=5,-1,0
  4495.6    0.12       0  4685.6     0.1       0  4748.2    0.12       0
  5052.4    0.05       0  5056.7    0.12       0
Bank Sta=5052.4,5056.7
Exp/Cntr=0.3,0.1

Type RM Length L Ch R = 1,2030,594,594,594
BEGIN DESCRIPTION:
Stream0794 1.0
END DESCRIPTION:
XS GIS Cut Line= 3
      2428925.01     13584274.99      2429675.00     13583825.00
      2429725.00     13583175.05
#Sta/Elev= 30
  4125.4  355.92  4148.7  354.08  4234.2  350.78  4249.8  349.30  4288.1  348.29
  4315.2  347.31  4350.8  346.49  4366.4  345.38  4424.7  344.34  4557.1  344.48
  4642.4  344.60  4731.8  343.19  4905.6  342.43  4928.1  342.80  4941.7  342.09
  5040.1  341.88  5090.3  342.71  5190.6  341.84  5198.5  339.75  5198.8  339.25
  5202.5  339.25  5202.8  339.75  5210.6  341.71  5246.2  342.26  5431.3  349.64
  5471.3  352.49  5531.6  356.08  5541.6  357.31  5626.5  363.35  5651.9  364.86
#Mann=10,-1,0
  4125.4    0.07       0  4288.1    0.12       0  4315.2     0.1       0
  4557.1    0.12       0  4905.6     0.1       0  5198.5    0.05       0
  5202.8     0.1       0  5246.2    0.12       0  5471.3    0.07       0
  5626.5    0.05       0
Bank Sta=5198.5,5202.8
Exp/Cntr=0.3,0.1

Type RM Length L Ch R = 1,1436,712,712,712
BEGIN DESCRIPTION:
XS7739
END DESCRIPTION:
XS GIS Cut Line= 3
      2428970.29     13584273.44      2429970.31     13584122.40
      2430838.93     13583258.98
#Sta/Elev= 30
  3566.8  352.50  3660.1  348.62  3783.9  344.31  3814.3  344.88  3844.3  344.17
  4055.2  343.93  4077.2  343.03  4218.8  342.52  4261.9  341.62  4542.5  341.25
  4615.0  339.71  4671.5  341.22  4777.6  341.35  4876.6  338.69  4989.8  340.01
  5100.8  337.43  5101.0  336.93  5105.1  337.43  5357.5  338.78  5421.1  341.75
  5497.9  348.13  5583.8  353.50  5647.4  355.72  5668.6  357.24  5675.7  356.94
  5703.9  358.24  5711.0  359.33  5718.1  358.98  5788.8  361.67  5802.9  362.86
#Mann=7,-1,0
  3566.8    0.07       0  3660.1    0.12       0  3814.3     0.1       0
  3844.3    0.12       0  5100.8    0.05       0  5105.1    0.12       0
  5497.9    0.07       0
Bank Sta=5100.8,5105.1
Exp/Cntr=0.3,0.1

Type RM Length L Ch R = 1,724,471,471,471
BEGIN DESCRIPTION:
XS7738
END DESCRIPTION:
XS GIS Cut Line= 3
      2428965.09     13584294.27      2430267.19     13584320.31
      2431281.42     13583847.00
#Sta/Elev= 30
  3192.4  353.38  3288.9  349.10  3432.4  343.78  3592.4  343.12  3692.4  343.63
  3872.5  341.76  4042.5  342.91  4082.5  342.01  4212.5  341.97  4272.5  340.49
  4491.2  338.92  4570.8  339.71  4656.7  337.43  4799.4  336.92  4812.4  336.06
  4845.1  336.80  4896.3  335.90  4955.8  336.74  5030.8  334.71  5031.1  334.21
  5035.4  334.71  5140.4  336.21  5181.7  338.52  5187.6  339.82  5198.5  340.40
  5345.8  349.47  5438.6  355.58  5444.1  356.77  5467.0  358.60  5614.0  367.77
#Mann=7,-1,0
  3192.4    0.07       0  3288.9    0.12       0  5030.8    0.05       0
  5035.4    0.12       0  5140.4     0.1       0  5198.5    0.12       0
  5345.8    0.07       0
Bank Sta=5030.8,5035.4
Exp/Cntr=0.3,0.1

Type RM Length L Ch R = 1,253,0,0,0
BEGIN DESCRIPTION:
H21067
END DESCRIPTION:
XS GIS Cut Line= 3
      2429608.61     13584356.10      2430828.24     13584597.77
      2431766.84     13584580.91
#Sta/Elev= 30
  3866.9  341.77  3924.4  342.11  4005.9  343.65  4077.3  342.69  4128.3  342.93
  4342.4  339.76  4353.8  340.18  4467.3  339.38  4507.5  338.69  4597.2  338.71
  4656.0  337.74  4661.1  337.17  4698.4  337.09  4926.1  335.62  5025.4  334.76
  5070.8  335.17  5194.9  333.88  5327.0  334.04  5454.7  332.42  5455.0  331.92
  5459.1  331.92  5459.5  332.42  5517.1  333.03  5597.1  335.93  5657.1  338.76
  5700.6  342.01  5847.1  354.68  5947.1  361.40  6007.2  362.71  6049.0  361.95
#Mann=8,-1,0
  3866.9    0.12       0  4467.3     0.1       0  4698.4    0.12       0
  4926.1    0.07       0  5194.9    0.12       0  5454.7    0.05       0
  5459.5    0.12       0  5700.6    0.07       0
Bank Sta=5454.7,5459.5
Exp/Cntr=0.3,0.1

Chan Stop Cuts=-1