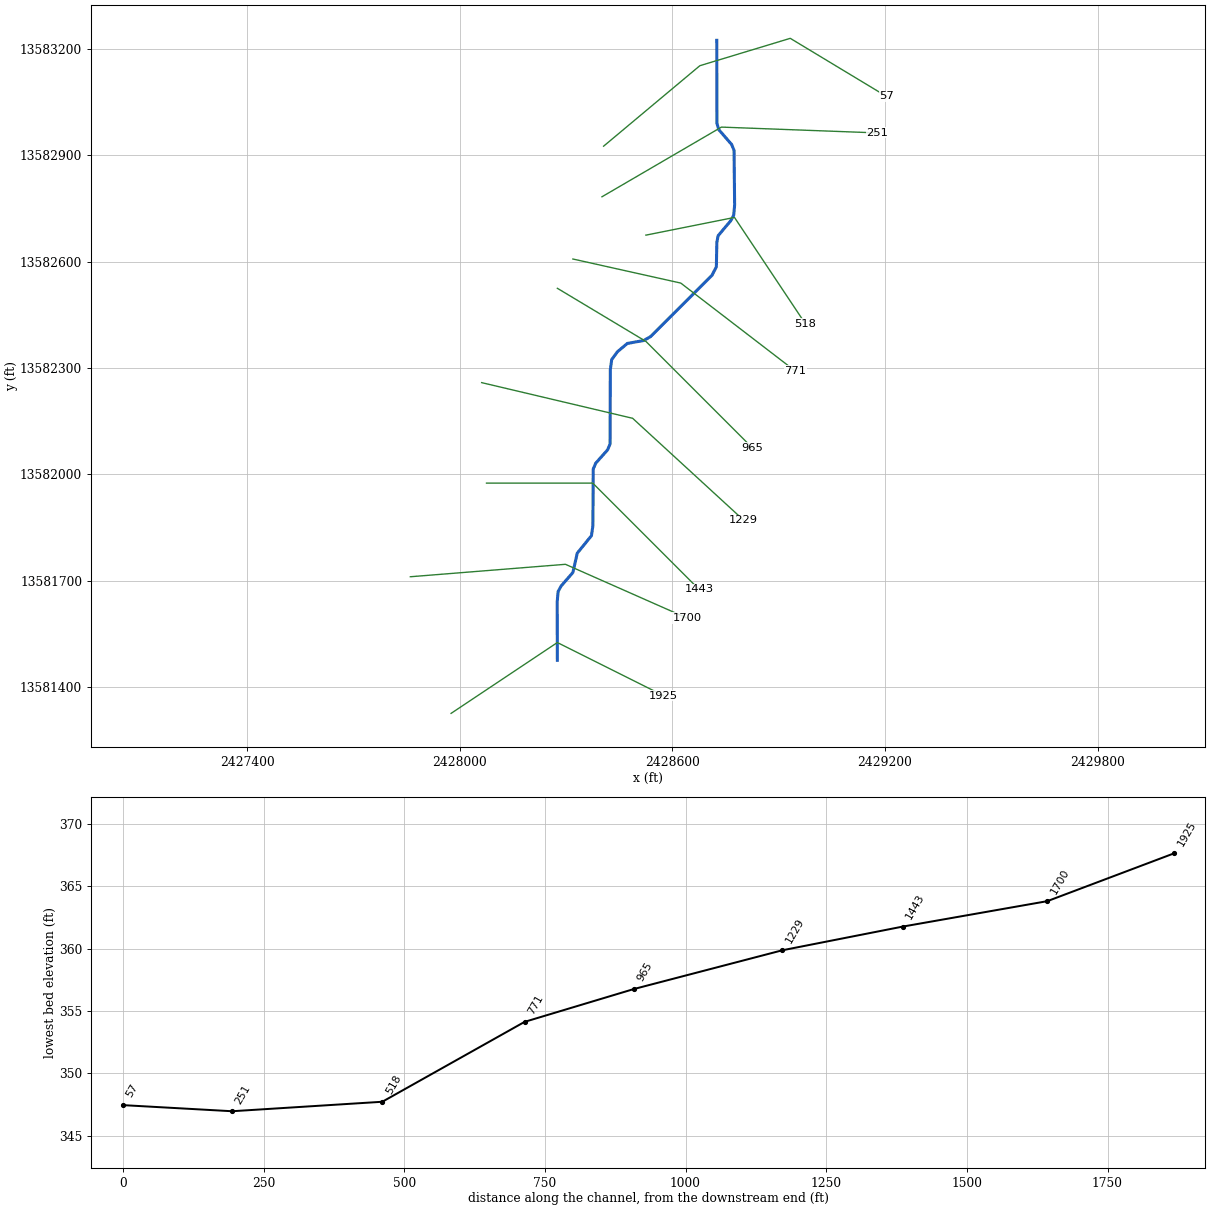
--- Stream0795.prj (project) ---

Proj Title=Stream0795 Base Level Engineering
Current Plan=p01
Default Exp/Contr=0.3,0.1
English Units
Geom File=g01
Flow File=f01
Plan File=p01
BEGIN DESCRIPTION:
Stream0795
END DESCRIPTION:

--- Stream0795.p01 (plan) ---

Plan Title=Multiple Run
Short Identifier=Multiple
Geom File=g01
Flow File=f01
Subcritical Flow
K Sum by GR= 0
Std Step Tol= 0.01
Critical Tol= 0.01
Num of Std Step Trials= 20
Max Error Tol= 0.3
Flow Tol Ratio= 0.001
Split Flow NTrial= 30
Split Flow Tol= 0.02
Split Flow Ratio= 0.02
Log Output Level= 0
Friction Slope Method= 1
Unsteady Friction Slope Method= 2
Unsteady Bridges Friction Slope Method= 1
Parabolic Critical Depth
Global Vel Dist=  1 , 1 , 1
Global Log Level= 0
CheckData=True
Encroach Param= -1, 0, 0, 0
BEGIN DESCRIPTION:
Multiple Run
END DESCRIPTION:

--- Stream0795.f01 (steady flow) ---

Flow Title=Multiple
Number of Profiles=7
Profile Names=10-year,25-year,50-year,1pct_min,100-year,1pct_plu,500-year
River Rch & RM= Stream0795,Reach-1,1925
     437     698     932     605    1208    2410    2004
River Rch & RM= Stream0795,Reach-1,57
     931    1550    2127    1414    2821    5628    4914
Boundary for River Rch & Prof#=Stream0795,Reach-1,1
Up Type=0
Dn Type=3
Dn Slope=0.005
Boundary for River Rch & Prof#=Stream0795,Reach-1,2
Up Type=0
Dn Type=3
Dn Slope=0.005
Boundary for River Rch & Prof#=Stream0795,Reach-1,3
Up Type=0
Dn Type=3
Dn Slope=0.005
Boundary for River Rch & Prof#=Stream0795,Reach-1,4
Up Type=0
Dn Type=3
Dn Slope=0.005
Boundary for River Rch & Prof#=Stream0795,Reach-1,5
Up Type=0
Dn Type=3
Dn Slope=0.005
Boundary for River Rch & Prof#=Stream0795,Reach-1,6
Up Type=0
Dn Type=3
Dn Slope=0.005
Boundary for River Rch & Prof#=Stream0795,Reach-1,7
Up Type=0
Dn Type=3
Dn Slope=0.005

--- Stream0795.g01 (geometry) ---

Geom Title=Existing Conditions

River Reach=Stream0795,Reach-1
Reach XY= 30
      2428275.00     13581475.00      2428274.55     13581640.19
      2428277.23     13581669.08      2428285.79     13581684.67
      2428318.88     13581722.82      2428331.12     13581777.18
      2428371.25     13581826.55      2428375.36     13581854.85
      2428376.22     13582014.49      2428383.14     13582031.06
      2428416.86     13582068.94      2428423.78     13582085.50
      2428424.54     13582295.25      2428428.45     13582323.75
      2428444.44     13582345.55      2428472.42     13582369.26
      2428518.91     13582377.55      2428538.20     13582388.64
      2428711.60     13582561.70      2428723.84     13582585.48
      2428725.25     13582654.90      2428728.86     13582673.40
      2428764.15     13582715.35      2428772.74     13582730.94
      2428775.43     13582759.82      2428773.78     13582914.49
      2428766.86     13582931.06      2428730.75     13582972.67
      2428725.52     13582990.22      2428725.00     13583225.00

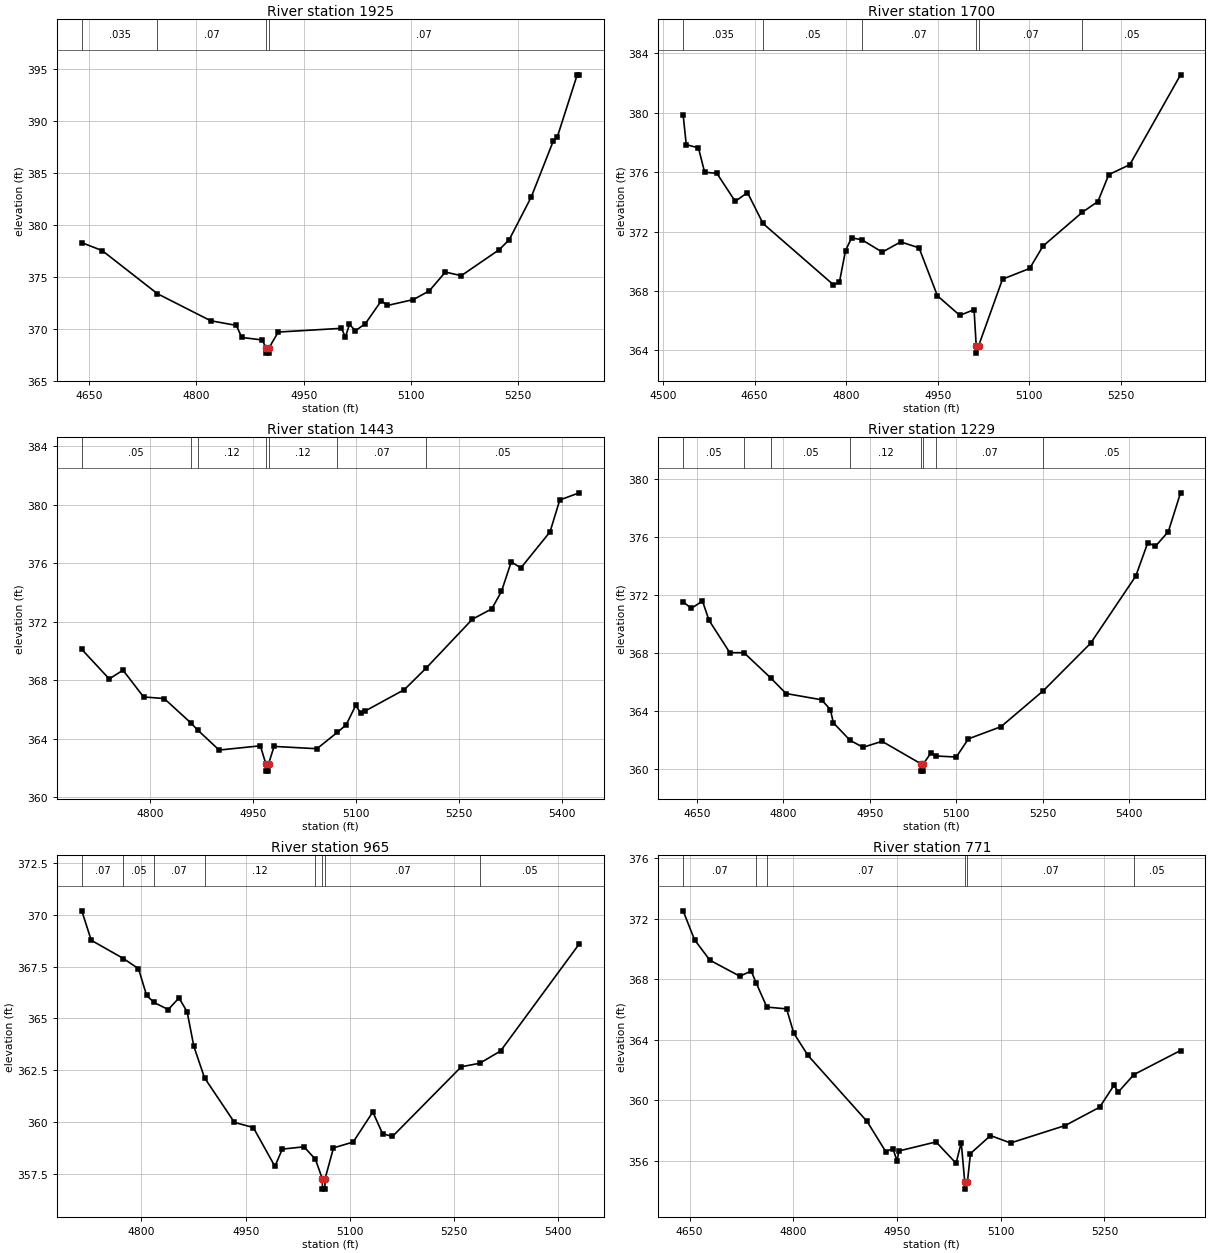
Type RM Length L Ch R = 1,1925,225,225,225
BEGIN DESCRIPTION:
Stream0795 4.0
END DESCRIPTION:
XS GIS Cut Line= 3
      2427975.01     13581325.01      2428275.00     13581525.00
      2428575.04     13581374.98
#Sta/Elev= 30
  4639.5  378.29  4668.0  377.53  4745.4  373.37  4819.8  370.77  4855.8  370.32
  4863.3  369.16  4891.9  368.92  4897.4  368.15  4897.6  367.65  4901.1  367.65
  4901.4  368.15  4914.4  369.68  5002.8  370.04  5008.4  369.19  5014.0  370.43
  5022.4  369.80  5036.4  370.50  5058.7  372.70  5067.1  372.24  5103.5  372.81
  5125.8  373.65  5148.2  375.46  5170.5  375.11  5223.7  377.62  5237.6  378.58
  5268.4  382.69  5299.1  388.06  5304.7  388.44  5332.7  394.46  5335.5  394.46
#Mann=4,-1,0
  4639.5   0.035       0  4745.4    0.07       0  4897.4    0.05       0
  4901.4    0.07       0
Bank Sta=4897.4,4901.4
Exp/Cntr=0.3,0.1

Type RM Length L Ch R = 1,1700,257,257,257
BEGIN DESCRIPTION:
H21071
END DESCRIPTION:
XS GIS Cut Line= 3
      2427859.96     13581710.68      2428297.83     13581745.80
      2428641.00     13581594.06
#Sta/Elev= 30
  4533.1  379.88  4538.2  377.86  4558.2  377.64  4568.3  376.00  4588.3  375.93
  4618.4  374.04  4638.5  374.63  4663.9  372.55  4779.3  368.42  4789.0  368.59
  4799.0  370.73  4809.0  371.58  4825.5  371.46  4859.2  370.62  4889.3  371.31
  4919.4  370.91  4949.5  367.68  4986.2  366.36  5009.5  366.75  5013.0  364.32
  5013.2  363.82  5017.0  364.32  5056.1  368.80  5100.5  369.52  5122.4  371.03
  5186.9  373.31  5212.3  374.03  5230.1  375.84  5264.5  376.51  5347.6  382.56
#Mann=6,-1,0
  4533.1   0.035       0  4663.9    0.05       0  4825.5    0.07       0
  5013.0    0.05       0  5017.0    0.07       0  5186.9    0.05       0
Bank Sta=5013,5017
Exp/Cntr=0.3,0.1

Type RM Length L Ch R = 1,1443,214,214,214
BEGIN DESCRIPTION:
Stream0795 3.0
END DESCRIPTION:
XS GIS Cut Line= 3
      2428075.00     13581975.00      2428375.00     13581975.00
      2428675.03     13581674.97
#Sta/Elev= 30
  4700.4  370.10  4740.4  368.08  4760.4  368.68  4790.4  366.85  4820.4  366.74
  4859.1  365.08  4868.9  364.60  4900.4  363.22  4960.4  363.51  4968.4  362.28
  4968.6  361.78  4972.1  361.78  4972.4  362.28  4980.4  363.47  5042.8  363.31
  5072.5  364.43  5085.3  364.94  5099.4  366.28  5106.5  365.74  5113.5  365.90
  5170.1  367.35  5201.8  368.82  5269.1  372.16  5297.4  372.87  5311.5  374.06
  5325.7  376.08  5339.8  375.67  5382.2  378.13  5396.4  380.31  5424.7  380.80
#Mann=7,-1,0
  4700.4    0.05       0  4859.1    0.07       0  4868.9    0.12       0
  4968.4    0.05       0  4972.4    0.12       0  5072.5    0.07       0
  5201.8    0.05       0
Bank Sta=4968.4,4972.4
Exp/Cntr=0.3,0.1

Type RM Length L Ch R = 1,1229,264,264,264
BEGIN DESCRIPTION:
H21070
END DESCRIPTION:
XS GIS Cut Line= 3
      2428061.30     13582258.67      2428487.52     13582157.97
      2428800.65     13581870.55
#Sta/Elev= 30
  4626.2  371.53  4640.3  371.08  4659.8  371.58  4671.1  370.26  4707.2  368.03
  4731.8  368.03  4778.2  366.29  4804.7  365.22  4866.3  364.79  4881.6  364.12
  4886.9  363.20  4915.8  362.00  4938.3  361.52  4971.3  361.93  5039.0  360.38
  5039.3  359.88  5042.8  359.88  5043.0  360.38  5055.9  361.12  5065.6  360.92
  5100.1  360.85  5121.1  362.10  5177.8  362.94  5251.3  365.42  5333.2  368.68
  5411.5  373.30  5432.4  375.60  5445.6  375.35  5468.0  376.36  5489.2  379.03
#Mann=8,-1,0
  4626.2    0.05       0  4731.8    0.12       0  4778.2    0.05       0
  4915.8    0.12       0  5039.0    0.05       0  5043.0    0.12       0
  5065.6    0.07       0  5251.3    0.05       0
Bank Sta=5039,5043
Exp/Cntr=0.3,0.1

Type RM Length L Ch R = 1,965,194,194,194
BEGIN DESCRIPTION:
Stream0795 2.0
END DESCRIPTION:
XS GIS Cut Line= 3
      2428275.03     13582524.98      2428525.00     13582375.00
      2428825.02     13582074.98
#Sta/Elev= 30
  4714.2  370.19  4727.8  368.77  4774.1  367.89  4795.8  367.40  4807.5  366.11
  4818.2  365.77  4838.6  365.43  4854.1  365.99  4865.8  365.32  4875.5  363.65
  4890.8  362.14  4933.8  359.99  4961.0  359.74  4992.1  357.87  5002.8  358.70
  5034.0  358.81  5050.4  358.21  5060.3  357.27  5060.5  356.77  5064.0  356.77
  5064.3  357.27  5076.4  358.76  5104.7  359.04  5133.0  360.49  5147.1  359.44
  5161.3  359.31  5260.3  362.67  5286.9  362.84  5316.8  363.43  5430.0  368.59
#Mann=8,-1,0
  4714.2    0.07       0  4774.1    0.05       0  4818.2    0.07       0
  4890.8    0.12       0  5050.4    0.07       0  5060.3    0.05       0
  5064.3    0.07       0  5286.9    0.05       0
Bank Sta=5060.3,5064.3
Exp/Cntr=0.3,0.1

Type RM Length L Ch R = 1,771,253,253,253
BEGIN DESCRIPTION:
H21069
END DESCRIPTION:
XS GIS Cut Line= 3
      2428318.86     13582607.61      2428623.35     13582539.69
      2428946.54     13582291.44
#Sta/Elev= 30
  4640.6  372.53  4657.1  370.62  4679.2  369.27  4722.6  368.21  4739.1  368.55
  4746.4  367.75  4761.7  366.17  4790.3  366.05  4800.6  364.45  4821.1  362.98
  4906.7  358.61  4933.8  356.61  4944.0  356.82  4950.1  356.00  4952.6  356.66
  5006.4  357.26  5035.4  355.85  5042.9  357.22  5047.9  354.64  5048.1  354.14
  5051.9  354.64  5056.2  356.49  5085.2  357.68  5114.2  357.19  5193.1  358.34
  5243.0  359.55  5263.8  361.00  5270.1  360.56  5292.7  361.71  5360.1  363.30
#Mann=6,-1,0
  4640.6    0.07       0  4746.4    0.05       0  4761.7    0.07       0
  5047.9    0.05       0  5051.9    0.07       0  5292.7    0.05       0
Bank Sta=5047.9,5051.9
Exp/Cntr=0.3,0.1

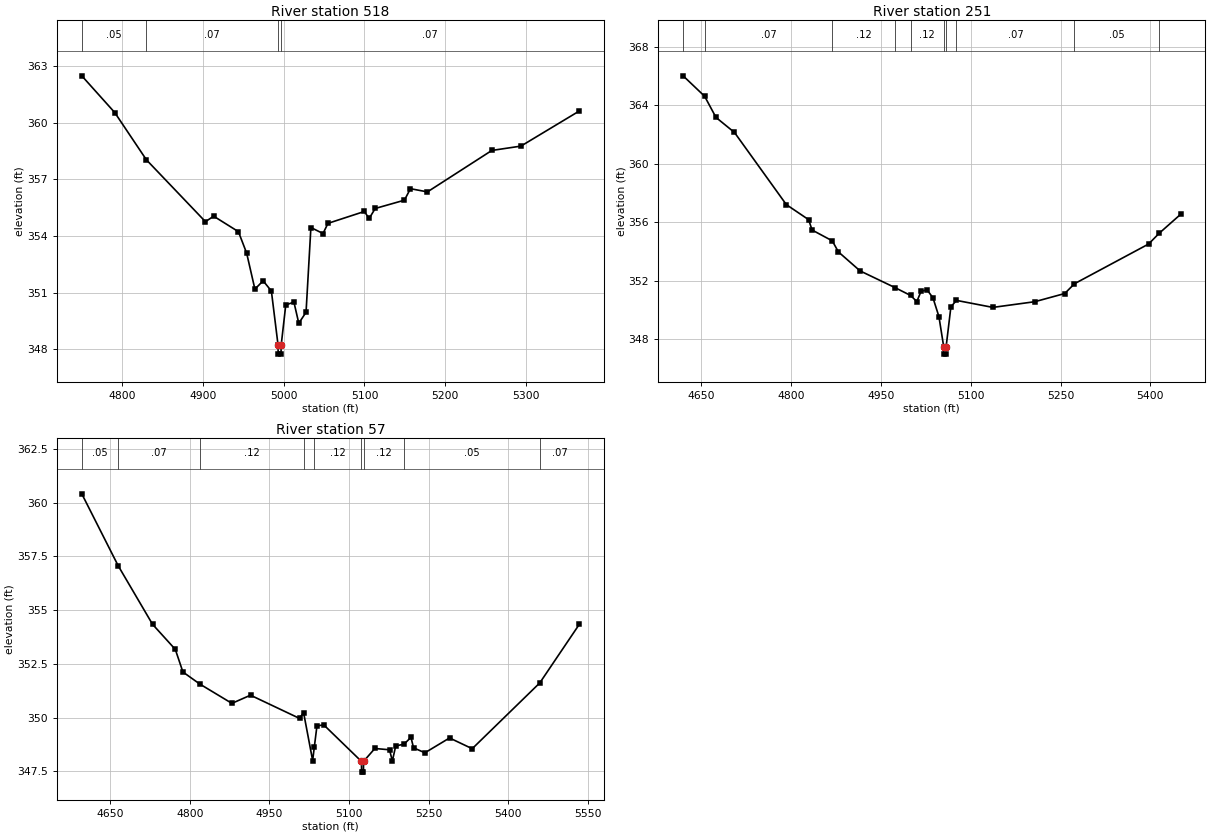
Type RM Length L Ch R = 1,518,267,267,267
BEGIN DESCRIPTION:
Stream0795 1.0
END DESCRIPTION:
XS GIS Cut Line= 3
      2428524.97     13582674.99      2428775.00     13582725.00
      2428974.98     13582425.03
#Sta/Elev= 30
  4750.2  362.50  4791.0  360.55  4830.2  358.04  4903.2  354.76  4913.4  355.05
  4944.0  354.23  4954.2  353.09  4964.4  351.18  4974.6  351.62  4984.8  351.08
  4993.0  348.23  4993.2  347.73  4996.7  347.73  4997.0  348.23  5002.6  350.34
  5012.7  350.49  5018.7  349.37  5027.7  349.95  5033.7  354.45  5048.7  354.13
  5054.8  354.67  5099.8  355.30  5105.8  354.93  5113.3  355.46  5149.4  355.90
  5156.9  356.51  5177.9  356.34  5257.6  358.54  5293.6  358.77  5365.7  360.63
#Mann=4,-1,0
  4750.2    0.05       0  4830.2    0.07       0  4993.0    0.05       0
  4997.0    0.07       0
Bank Sta=4993,4997
Exp/Cntr=0.3,0.1

Type RM Length L Ch R = 1,251,194,194,194
BEGIN DESCRIPTION:
H21068
END DESCRIPTION:
XS GIS Cut Line= 3
      2428400.91     13582783.26      2428738.10     13582979.96
      2429178.33     13582963.57
#Sta/Elev= 30
  4619.5  366.03  4655.4  364.63  4674.4  363.18  4705.3  362.15  4791.9  357.21
  4829.1  356.18  4834.9  355.47  4868.6  354.73  4878.9  353.97  4915.1  352.67
  4973.2  351.53  4999.4  350.99  5009.9  350.57  5016.8  351.26  5026.8  351.38
  5036.8  350.83  5046.8  349.54  5054.8  347.47  5055.1  346.97  5058.6  346.97
  5058.8  347.47  5066.8  350.21  5076.1  350.65  5136.9  350.17  5206.9  350.56
  5256.9  351.12  5273.2  351.79  5397.0  354.51  5414.8  355.25  5450.4  356.54
#Mann=10,-1,0
  4619.5    0.05       0  4655.4    0.07       0  4868.6    0.12       0
  4973.2    0.07       0  4999.4    0.12       0  5054.8    0.05       0
  5058.8    0.12       0  5076.1    0.07       0  5273.2    0.05       0
  5414.8    0.07       0
Bank Sta=5054.8,5058.8
Exp/Cntr=0.3,0.1

Type RM Length L Ch R = 1,57,0,0,0
BEGIN DESCRIPTION:
XS7737
END DESCRIPTION:
XS GIS Cut Line= 4
      2428405.58     13582926.11      2428677.21     13583153.25
      2428932.47     13583230.54      2429204.15     13583066.60
#Sta/Elev= 30
  4596.0  360.41  4664.7  357.06  4729.4  354.34  4772.4  353.17  4786.7  352.12
  4818.5  351.56  4879.1  350.66  4914.2  351.04  5006.6  349.96  5014.3  350.23
  5031.4  348.00  5034.6  348.64  5039.5  349.61  5052.3  349.66  5123.4  347.96
  5123.7  347.46  5127.2  347.46  5127.4  347.96  5148.7  348.56  5176.4  348.50
  5181.7  347.98  5188.1  348.68  5203.7  348.76  5216.8  349.08  5221.7  348.59
  5243.1  348.36  5289.6  349.05  5332.3  348.55  5459.7  351.61  5534.1  354.33
#Mann=9,-1,0
  4596.0    0.05       0  4664.7    0.07       0  4818.5    0.12       0
  5014.3    0.07       0  5034.6    0.12       0  5123.4    0.05       0
  5127.4    0.12       0  5203.7    0.05       0  5459.7    0.07       0
Bank Sta=5123.4,5127.4
Exp/Cntr=0.3,0.1

Chan Stop Cuts=-1