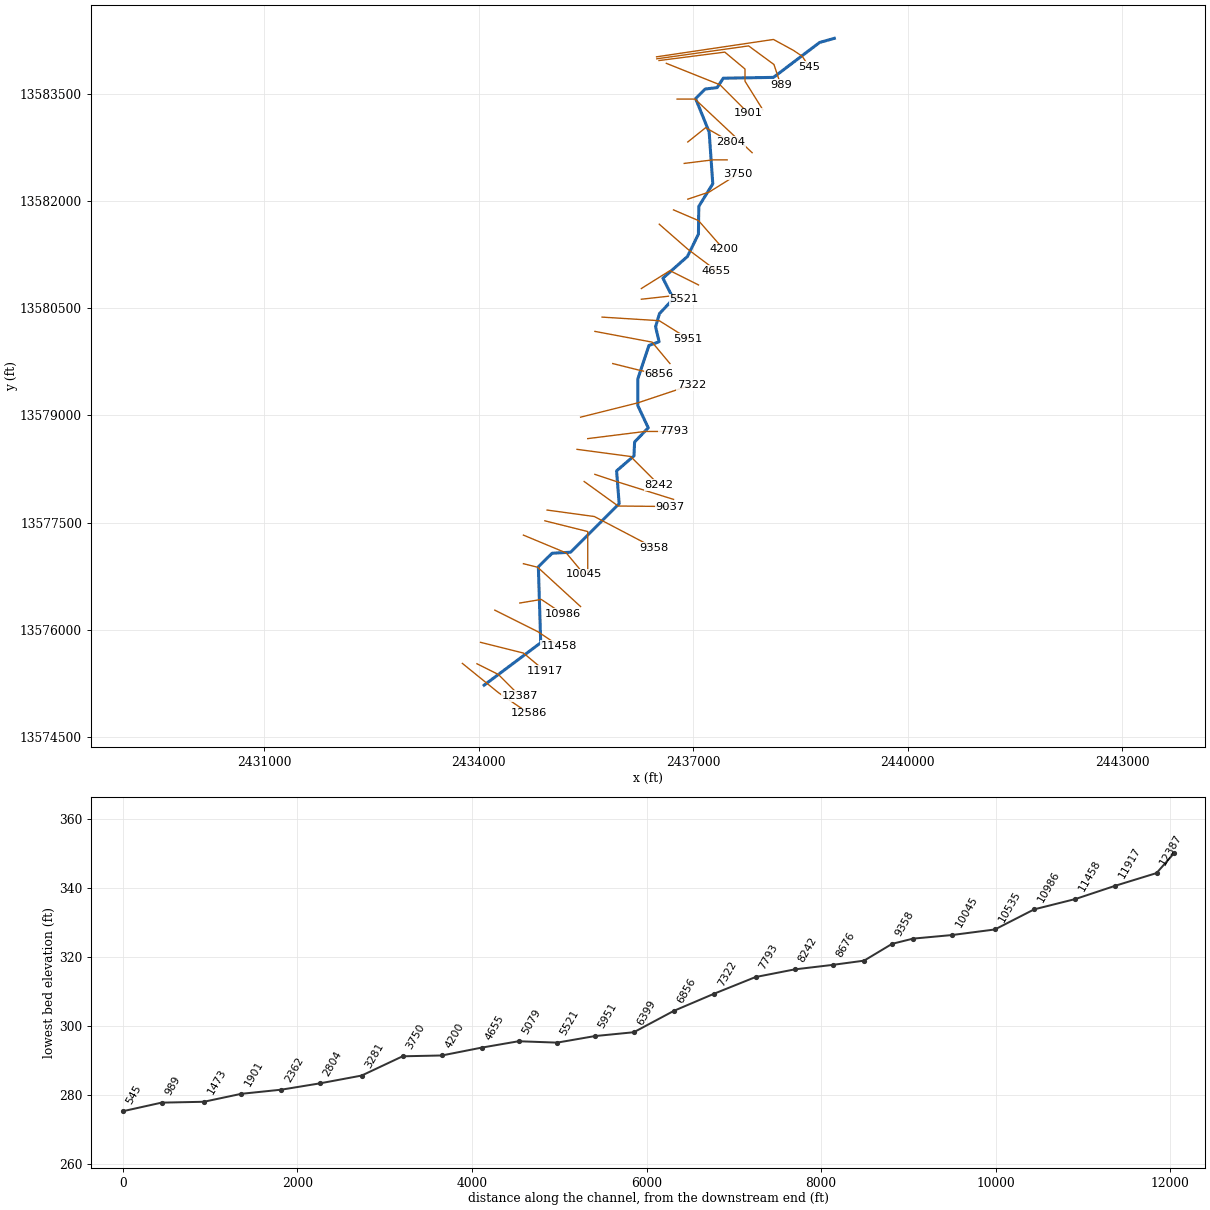
--- Stream0797.prj (project) ---

Proj Title=Stream0797 Base Level Engineering
Current Plan=p01
Default Exp/Contr=0.3,0.1
English Units
Geom File=g01
Flow File=f01
Plan File=p01
Y Axis Title=Elevation
X Axis Title(PF)=Main Channel Distance
X Axis Title(XS)=Station
BEGIN DESCRIPTION:
Stream0797
END DESCRIPTION:
DSS Export Rating Curves= 0
DSS Export Rating Curve Sorted= 0
DSS Export Volume Flow Curves= 0
DXF OffsetX= 0
DXF OffsetY= 0
DXF ScaleX= 1
DXF ScaleY= 10

--- Stream0797.p01 (plan) ---

Plan Title=Multiple Run
Short Identifier=Multiple
Geom File=g01
Flow File=f01
Subcritical Flow
K Sum by GR= 0
Std Step Tol= 0.01
Critical Tol= 0.01
Num of Std Step Trials= 20
Max Error Tol= 0.3
Flow Tol Ratio= 0.001
Split Flow NTrial= 30
Split Flow Tol= 0.02
Split Flow Ratio= 0.02
Log Output Level= 0
Friction Slope Method= 1
Unsteady Friction Slope Method= 2
Unsteady Bridges Friction Slope Method= 1
Parabolic Critical Depth
Global Vel Dist=  1 , 1 , 1
Global Log Level= 0
CheckData=True
Encroach Param= -1, 0, 0, 0
BEGIN DESCRIPTION:
Multiple Run
END DESCRIPTION:

--- Stream0797.f01 (steady flow) ---

Flow Title=Multiple
Number of Profiles=7
Profile Names=10-year,25-year,50-year,1pct_min,100-year,1pct_plu,500-year
River Rch & RM= Stream0797,Reach-1,12586
     569     920    1238     808    1613    3217    2707
River Rch & RM= Stream0797,Reach-1,9037
    1183    1989    2746    1833    3658    7299    6439
River Rch & RM= Stream0797,Reach-1,4200
    1911    3300    4641    3152    6289   12548   11457
Boundary for River Rch & Prof#=Stream0797,Reach-1,1
Up Type=0
Dn Type=3
Dn Slope=0.005
Boundary for River Rch & Prof#=Stream0797,Reach-1,2
Up Type=0
Dn Type=3
Dn Slope=0.005
Boundary for River Rch & Prof#=Stream0797,Reach-1,3
Up Type=0
Dn Type=3
Dn Slope=0.005
Boundary for River Rch & Prof#=Stream0797,Reach-1,4
Up Type=0
Dn Type=3
Dn Slope=0.005
Boundary for River Rch & Prof#=Stream0797,Reach-1,5
Up Type=0
Dn Type=3
Dn Slope=0.005
Boundary for River Rch & Prof#=Stream0797,Reach-1,6
Up Type=0
Dn Type=3
Dn Slope=0.005
Boundary for River Rch & Prof#=Stream0797,Reach-1,7
Up Type=0
Dn Type=3
Dn Slope=0.005

--- Stream0797.g01 (geometry) ---

Geom Title=Existing Conditions
Program Version=4.10

River Reach=Stream0797      ,Reach-1
Reach XY= 30
        2434075.       13575225.      2434867.25     13575818.81
      2434834.13     13576881.74      2435026.46     13577071.46
      2435284.82     13577085.47      2435964.53     13577765.18
      2435928.53     13578223.53      2436171.93      13578433.3
      2436180.46     13578627.45      2436371.54      13578826.5
       2436226.2      13579135.5      2436225.52     13579509.78
      2436380.83     13579977.84      2436523.04      13580030.5
      2436474.29     13580240.06      2436528.61      13580423.5
      2436723.39     13580631.04      2436576.58     13580918.95
      2436919.51     13581222.55      2437073.81     13581535.49
      2437078.55     13581923.53      2437274.49     13582240.21
      2437223.78      13582964.5      2437034.13     13583431.74
      2437168.33      13583565.7        2437335.     13583585.62
      2437421.33     13583717.31       2438123.5     13583728.61
      2438768.81     13584217.19        2438975.       13584275.

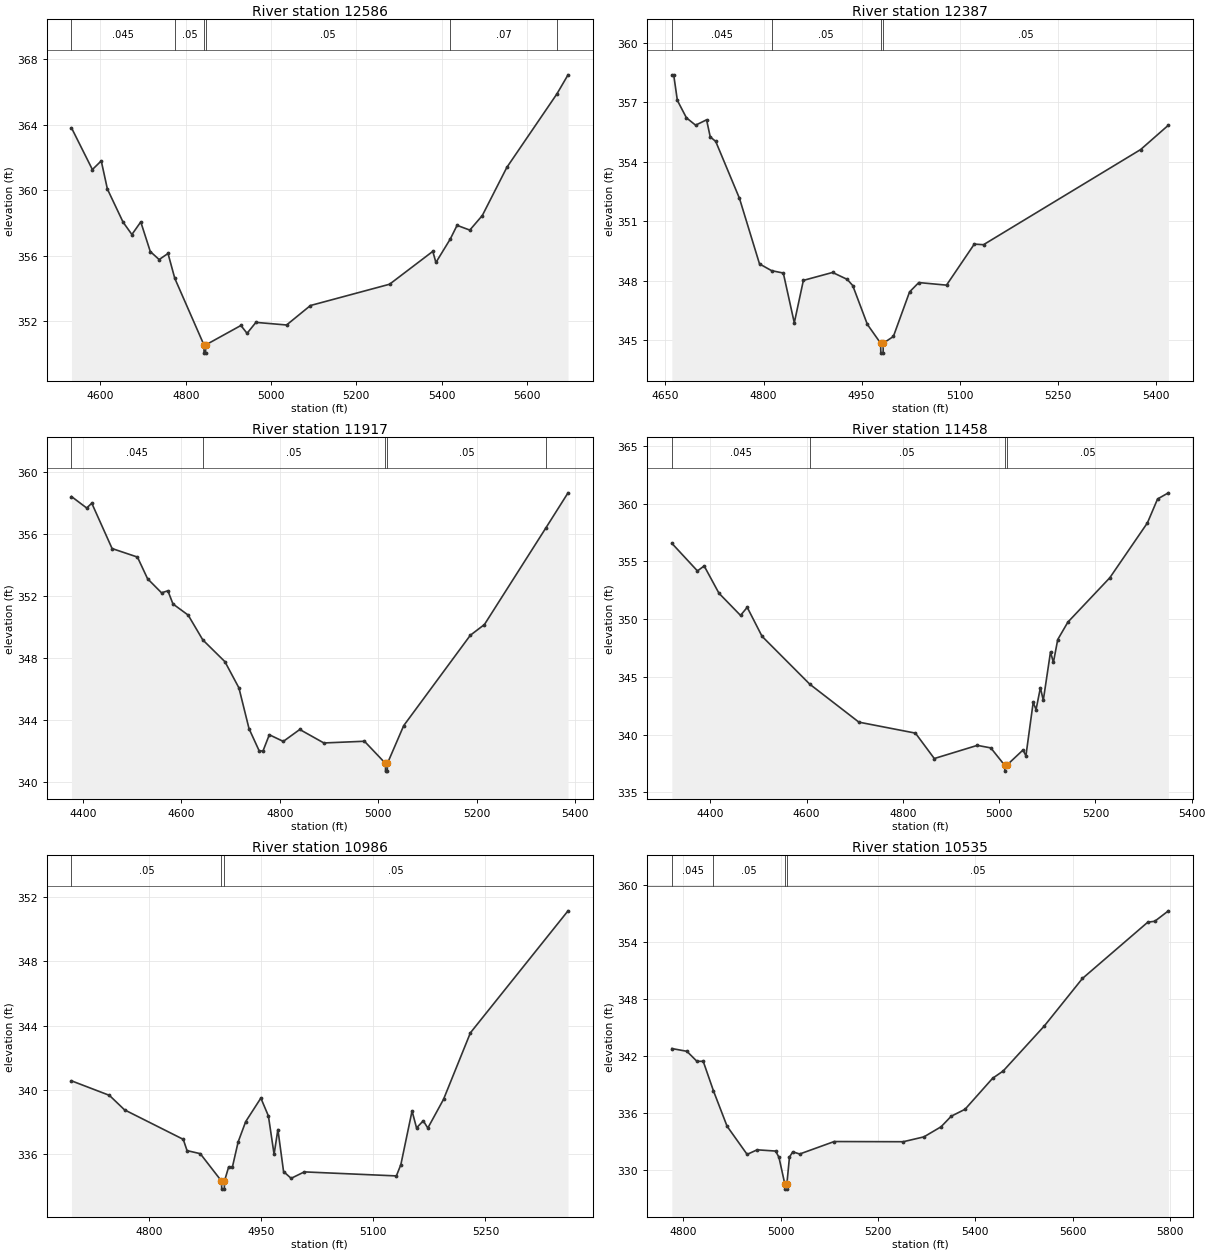
Type RM Length L Ch R = 1 ,12586   ,199,199,199
BEGIN DESCRIPTION:
XS7740
END DESCRIPTION:
XS GIS Cut Line= 3
      2433771.05     13575530.12      2434279.11     13575118.02
      2434701.27     13574830.95
#Sta/Elev= 30
    4532  363.82    4581  361.27  4601.8   361.8  4616.2  360.08  4652.9  358.06
  4673.7   357.3  4694.5  358.07  4716.8  356.26  4737.6  355.77  4758.4  356.14
  4774.3  354.62  4842.7  350.55  4842.9  350.05  4846.4  350.05  4846.7  350.55
  4929.4  351.74  4943.8  351.26  4964.6  351.93  5036.5  351.77  5092.5  352.96
    5278  354.26  5379.5  356.27  5386.8  355.59  5420.6  357.03  5436.4  357.86
  5466.3  357.57  5495.6  358.46  5553.1   361.4  5670.5  365.89  5696.7  367.06
#Mann= 6 ,-1 , 0
    4532    .045       0  4774.3     .05       0  4842.7     .05       0
  4846.7     .05       0  5420.6     .07       0  5670.5     .05       0
Bank Sta=4842.7,4846.7
XS Rating Curve= 0 ,0
Exp/Cntr=0.3,0.1

Type RM Length L Ch R = 1 ,12387   ,470,470,470
BEGIN DESCRIPTION:
Stream0797 27.0
END DESCRIPTION:
XS GIS Cut Line= 3
      2433975.02     13575524.99        2434275.       13575375.
      2434575.03     13575074.97
#Sta/Elev= 30
  4659.8  358.39  4662.6  358.39  4668.2   357.1  4682.1  356.22  4696.1  355.85
  4712.9  356.12  4718.5  355.26  4726.9  355.03  4763.2  352.16  4793.9  348.85
  4812.4  348.51  4830.3  348.39  4847.1  345.88    4861  348.02  4905.7  348.42
  4928.1  348.07  4936.5  347.76  4958.9   345.8  4979.2  344.85  4979.5  344.35
    4983  344.35  4983.2  344.85  4998.7  345.19  5023.5  347.44  5037.6  347.91
    5080  347.78  5122.5  349.85  5136.6  349.82    5377  354.62  5419.5  355.85
#Mann= 4 ,-1 , 0
  4659.8    .045       0  4812.4     .05       0  4979.2     .05       0
  4983.2     .05       0
Bank Sta=4979.2,4983.2
XS Rating Curve= 0 ,0
Exp/Cntr=0.3,0.1

Type RM Length L Ch R = 1 ,11917   ,459,459,459
BEGIN DESCRIPTION:
Stream0797 26.0
END DESCRIPTION:
XS GIS Cut Line= 3
      2434024.99       13575825.        2434625.       13575675.
      2434925.01     13575424.99
#Sta/Elev= 30
  4376.5  358.44  4407.4   357.7  4417.7  358.01    4459  355.08  4510.5  354.53
  4531.1  353.13  4559.5  352.22  4572.4  352.35  4582.7   351.5  4613.6  350.78
  4643.3  349.18  4688.3  347.77  4716.7  346.08  4737.3  343.44  4757.9  342.01
  4765.6     342  4778.5  343.05  4806.9  342.62  4840.4  343.39  4889.3  342.52
  4971.8  342.63  5014.5   341.2  5014.7   340.7  5018.2   340.7  5018.5   341.2
  5051.6  343.64    5187  349.48  5215.6  350.17  5340.2   356.4  5385.5  358.68
#Mann= 5 ,-1 , 0
  4376.5    .045       0  4643.3     .05       0  5014.5     .05       0
  5018.5     .05       0  5340.2    .035       0
Bank Sta=5014.5,5018.5
XS Rating Curve= 0 ,0
Exp/Cntr=0.3,0.1

Type RM Length L Ch R = 1 ,11458   ,472,472,472
BEGIN DESCRIPTION:
Stream0797 25.0
END DESCRIPTION:
XS GIS Cut Line= 3
      2434224.98     13576275.01        2434825.       13575975.
        2435125.       13575775.
#Sta/Elev= 30
  4320.3  356.56  4373.4  354.17  4387.4   354.6  4418.1  352.24  4462.9  350.32
  4476.8  351.02  4507.6  348.51  4606.9  344.36  4708.8  341.08  4826.2  340.13
  4865.4  337.93  4954.8  339.07  4982.8  338.85  5011.7  337.34  5011.9  336.84
  5015.7  337.34  5049.7  338.67  5055.7  338.16  5070.8  342.79  5076.8  342.17
  5085.8  344.06  5091.8  342.97  5106.8  347.16  5112.8  346.25  5121.8  348.23
  5142.9  349.74    5230  353.58  5308.1  358.33  5329.2   360.4  5351.7  360.93
#Mann= 4 ,-1 , 0
  4320.3    .045       0  4606.9     .05       0  5011.7     .05       0
  5015.7     .05       0
Bank Sta=5011.7,5015.7
XS Rating Curve= 0 ,0
Exp/Cntr=0.3,0.1

Type RM Length L Ch R = 1 ,10986   ,451,451,451
BEGIN DESCRIPTION:
Stream0797 24.0
END DESCRIPTION:
XS GIS Cut Line= 3
      2434574.95     13576374.99        2434875.       13576425.
      2435174.96     13576225.02
#Sta/Elev= 30
  4695.8  340.57  4746.5  339.67  4766.8  338.77  4845.4  336.94  4850.5  336.24
  4868.2  336.05  4896.6  334.35  4896.9  333.85  4900.4  333.85  4900.6  334.35
  4906.2  335.23  4911.3  335.24  4918.9  336.78    4929  338.04  4949.3   339.5
  4959.4  338.39    4967  336.01  4972.1  337.55  4979.7  334.94  4989.8  334.52
  5007.5  334.92  5130.7  334.67  5136.7  335.37  5151.7   338.7  5157.7  337.65
  5166.7  338.09  5172.8  337.64  5193.8  339.42  5229.8  343.55  5360.5  351.12
#Mann= 3 ,-1 , 0
  4695.8     .05       0  4896.6     .05       0  4900.6     .05       0
Bank Sta=4896.6,4900.6
XS Rating Curve= 0 ,0
Exp/Cntr=0.3,0.1

Type RM Length L Ch R = 1 ,10535   ,490,490,490
BEGIN DESCRIPTION:
Stream0797 23.0
END DESCRIPTION:
XS GIS Cut Line= 3
      2434625.02     13576924.99        2434825.       13576875.
      2435425.02     13576324.98
#Sta/Elev= 30
  4776.7  342.79  4807.6   342.5  4828.2  341.45  4841.1  341.45  4862.2  338.34
  4890.1  334.63  4931.3  331.67  4951.9  332.15  4989.9  332.02  4996.7  331.36
  5008.9  328.52  5009.1  328.02  5012.6  328.02  5012.9  328.52  5018.3  331.39
  5025.1  331.94  5039.3  331.71  5110.2  333.02    5252     333  5294.5  333.51
  5329.7  334.57  5350.6  335.68    5379  336.41  5435.7  339.67  5457.3  340.43
  5541.8  345.16  5620.1  350.15  5754.5  356.07  5768.7  356.16  5796.8  357.26
#Mann= 4 ,-1 , 0
  4776.7    .045       0  4862.2     .05       0  5008.9     .05       0
  5012.9     .05       0
Bank Sta=5008.9,5012.9
XS Rating Curve= 0 ,0
Exp/Cntr=0.3,0.1

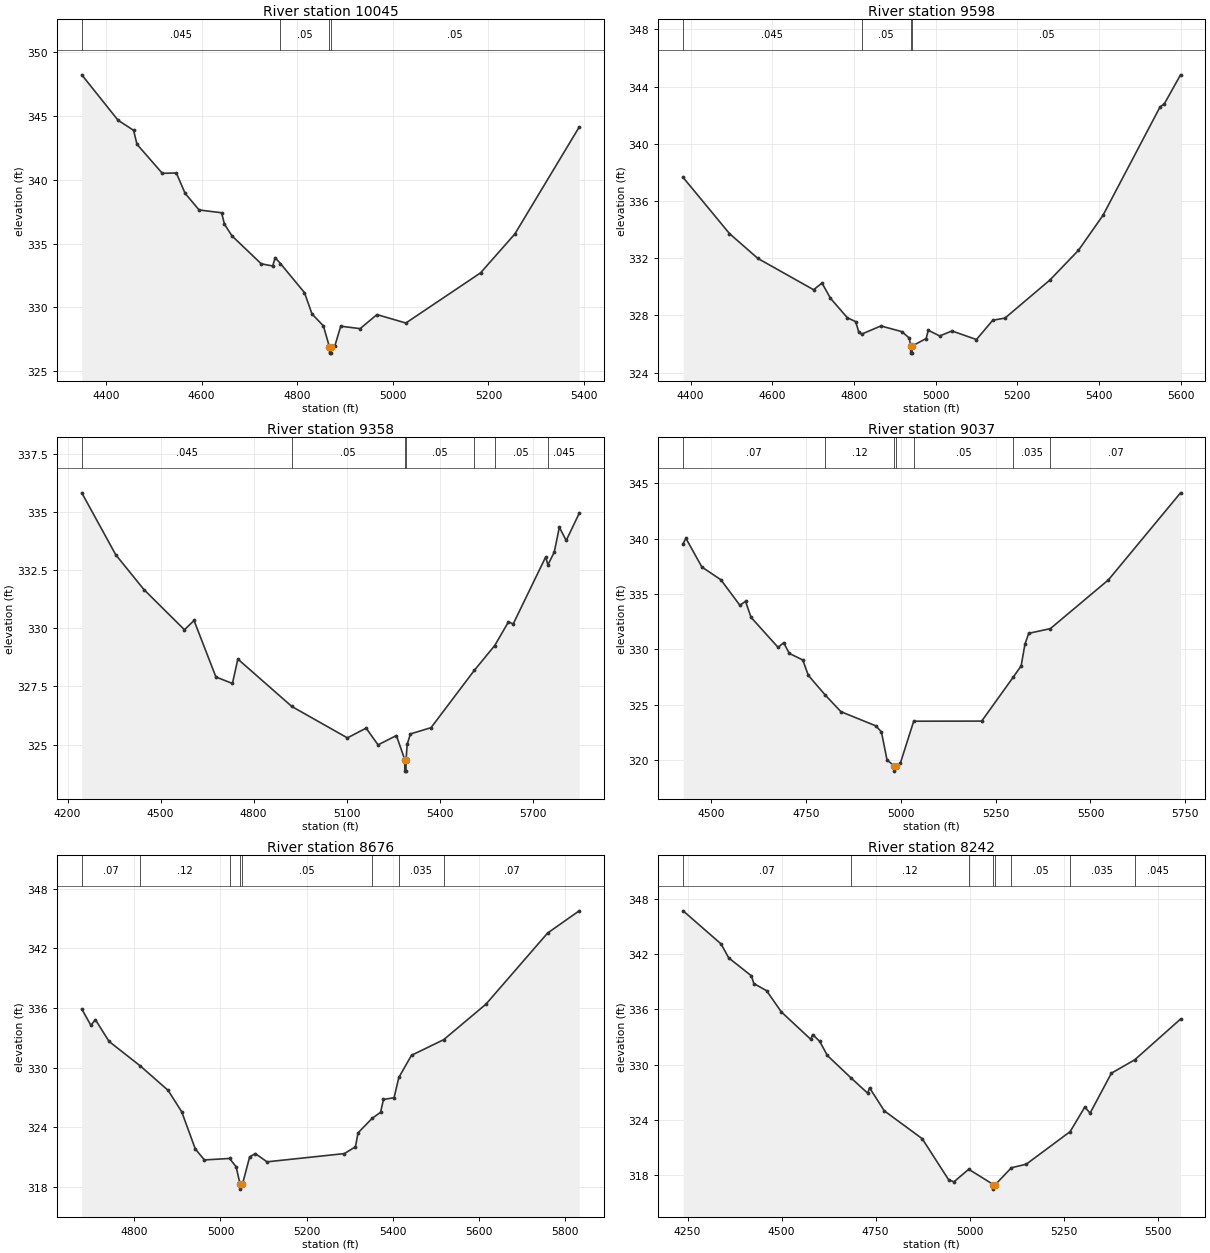
Type RM Length L Ch R = 1 ,10045   ,447,447,447
BEGIN DESCRIPTION:
Stream0797 22.0
END DESCRIPTION:
XS GIS Cut Line= 3
      2434624.96     13577325.02        2435225.       13577075.
      2435475.03     13576774.97
#Sta/Elev= 30
  4349.4  348.22  4425.3  344.66  4457.8  343.87  4464.8  342.78  4517.9   340.5
  4547.2  340.53  4565.6  338.93  4594.8  337.63  4641.9  337.41  4647.9  336.51
  4663.6   335.6  4724.8  333.41  4748.7  333.24  4754.1  333.89    4765  333.43
  4815.3  331.15    4831  329.48  4854.8  328.55  4867.4  326.91  4867.7  326.41
  4871.2  326.41  4871.4  326.91  4878.7  326.96  4891.1  328.52  4931.7  328.33
  4966.9  329.43  5027.4  328.77  5183.6   332.7  5255.2  335.74    5390  344.13
#Mann= 4 ,-1 , 0
  4349.4    .045       0    4765     .05       0  4867.4     .05       0
  4871.4     .05       0
Bank Sta=4867.4,4871.4
XS Rating Curve= 0 ,0
Exp/Cntr=0.3,0.1

Type RM Length L Ch R = 1 ,9598    ,240,240,240
BEGIN DESCRIPTION:
Stream0797 21.0
END DESCRIPTION:
XS GIS Cut Line= 3
      2434924.96     13577525.01        2435525.       13577375.
        2435525.     13576775.01
#Sta/Elev= 30
  4381.5  337.65  4494.9  333.73  4564.5  331.99  4701.1   329.8  4721.7  330.27
  4742.3  329.21  4783.5  327.85  4804.2  327.57  4811.9  326.83  4818.9   326.7
    4866  327.27  4917.5  326.87  4935.6  326.42  4938.7  325.87    4939  325.37
  4942.5  325.37  4942.7  325.87  4976.8  326.39    4982  326.97    5010  326.57
    5040  326.92    5100  326.32    5140  327.67    5170  327.82    5280  330.48
    5350  332.56    5410     335    5550  342.59    5560  342.78    5600  344.82
#Mann= 4 ,-1 , 0
  4381.5    .045       0  4818.9     .05       0  4938.7     .05       0
  4942.7     .05       0
Bank Sta=4938.7,4942.7
XS Rating Curve= 0 ,0
Exp/Cntr=0.3,0.1

Type RM Length L Ch R = 1 ,9358    ,321,321,321
BEGIN DESCRIPTION:
XS7741
END DESCRIPTION:
XS GIS Cut Line= 3
      2434956.58     13577675.47      2435617.11     13577585.14
      2436446.98     13577150.45
#Sta/Elev= 30
  4245.9  335.83  4355.2  333.17  4446.2  331.67  4576.9  329.94  4607.7  330.34
  4678.3  327.91  4731.5  327.63    4749  328.68  4923.1  326.64  5102.1  325.29
  5162.5  325.71  5200.9  324.99  5260.1  325.39    5287  324.36  5287.3  323.86
    5291  323.86  5291.3  324.36  5294.8  325.01  5305.3  325.46  5371.8  325.73
    5511  328.19    5577  329.26  5621.4  330.28  5636.6  330.19  5741.3  333.07
  5748.5  332.73    5769  333.28  5785.4  334.35  5807.5  333.78  5849.4  334.95
#Mann= 7 ,-1 , 0
  4245.9    .045       0  4923.1     .05       0    5287     .05       0
  5291.3     .05       0    5511    .045       0    5577     .05       0
  5748.5    .045       0
Bank Sta=5287,5291.3
XS Rating Curve= 0 ,0
Exp/Cntr=0.3,0.1

Type RM Length L Ch R = 1 ,9037    ,361,361,361
BEGIN DESCRIPTION:
Stream0797 20.0
END DESCRIPTION:
XS GIS Cut Line= 3
      2435474.98     13578075.02       2435950.2     13577731.93
      2436675.04       13577725.
#Sta/Elev= 30
  4426.4  339.55  4433.8  340.02  4475.8  337.43  4525.8  336.28  4576.1  333.97
  4590.8  334.33  4605.5  332.88  4676.7  330.17  4691.4  330.59  4706.1  329.63
  4741.7  329.03  4756.4  327.64  4800.8  325.87  4842.3  324.36  4934.3  323.08
  4949.1  322.53  4963.8     320  4981.9  319.49  4982.3  318.99  4987.4  319.49
  4999.3  319.75  5034.1   323.5  5213.3  323.51  5295.8  327.45  5317.3   328.5
  5327.3  330.46  5337.3  331.44  5394.2  331.86  5547.4  336.27  5737.4  344.13
#Mann= 7 ,-1 , 0
  4426.4     .07       0  4800.8     .12       0  4981.9     .05       0
  4987.4     .12       0  5034.1     .05       0  5295.8    .035       0
  5394.2     .07       0
Bank Sta=4981.9,4987.4
XS Rating Curve= 0 ,0
Exp/Cntr=0.3,0.1

Type RM Length L Ch R = 1 ,8676    ,434,434,434
BEGIN DESCRIPTION:
Stream0797 19.0
END DESCRIPTION:
XS GIS Cut Line= 3
        2435625.       13578175.        2435925.       13578075.
      2436725.02     13577824.99
#Sta/Elev= 30
  4678.1   335.9  4699.2  334.26  4709.7  334.83  4741.3  332.64  4813.8  330.17
  4878.4  327.71    4910  325.55  4941.6   321.8  4962.7   320.7    5021  320.85
  5036.2  320.02  5045.5  318.26    5046  317.76    5051  318.26  5067.7  321.01
  5080.8  321.34    5108  320.51  5287.7  321.34  5313.3  322.03  5319.1  323.42
  5351.7  324.88  5371.5   325.5  5378.3  326.79  5402.9  326.97  5413.9  329.01
  5443.3  331.24  5517.9  332.81  5616.1  336.39  5759.1  343.55  5832.5  345.79
#Mann= 8 ,-1 , 0
  4678.1     .07       0  4813.8     .12       0    5021     .05       0
  5045.5     .05       0    5051     .05       0  5351.7     .07       0
  5413.9    .035       0  5517.9     .07       0
Bank Sta=5045.5,5051
XS Rating Curve= 0 ,0
Exp/Cntr=0.3,0.1

Type RM Length L Ch R = 1 ,8242    ,449,449,449
BEGIN DESCRIPTION:
Stream0797 18.0
END DESCRIPTION:
XS GIS Cut Line= 3
      2435375.01       13578525.        2436125.       13578425.
      2436524.99     13578025.01
#Sta/Elev= 30
  4238.2   346.7  4339.1   343.1  4359.3  341.59  4419.8  339.63  4426.1   338.8
  4460.1  338.02  4499.2  335.72  4577.4  332.74  4582.5  333.26  4601.4  332.51
  4621.6  330.98  4684.9  328.53  4728.7  326.89  4733.8  327.47  4772.9  324.97
  4873.8  321.94  4944.4  317.45  4958.3  317.26  4997.4  318.62  5062.8  316.96
  5063.2  316.46  5068.3  316.96  5110.7  318.78  5150.4  319.17    5267  322.71
    5306  325.38  5320.1  324.72  5376.7  329.06  5438.6  330.51  5560.5  334.94
#Mann= 8 ,-1 , 0
  4238.2     .07       0  4684.9     .12       0  4997.4     .05       0
  5062.8     .05       0  5068.3     .05       0  5110.7     .05       0
    5267    .035       0  5438.6    .045       0
Bank Sta=5062.8,5068.3
XS Rating Curve= 0 ,0
Exp/Cntr=0.3,0.1

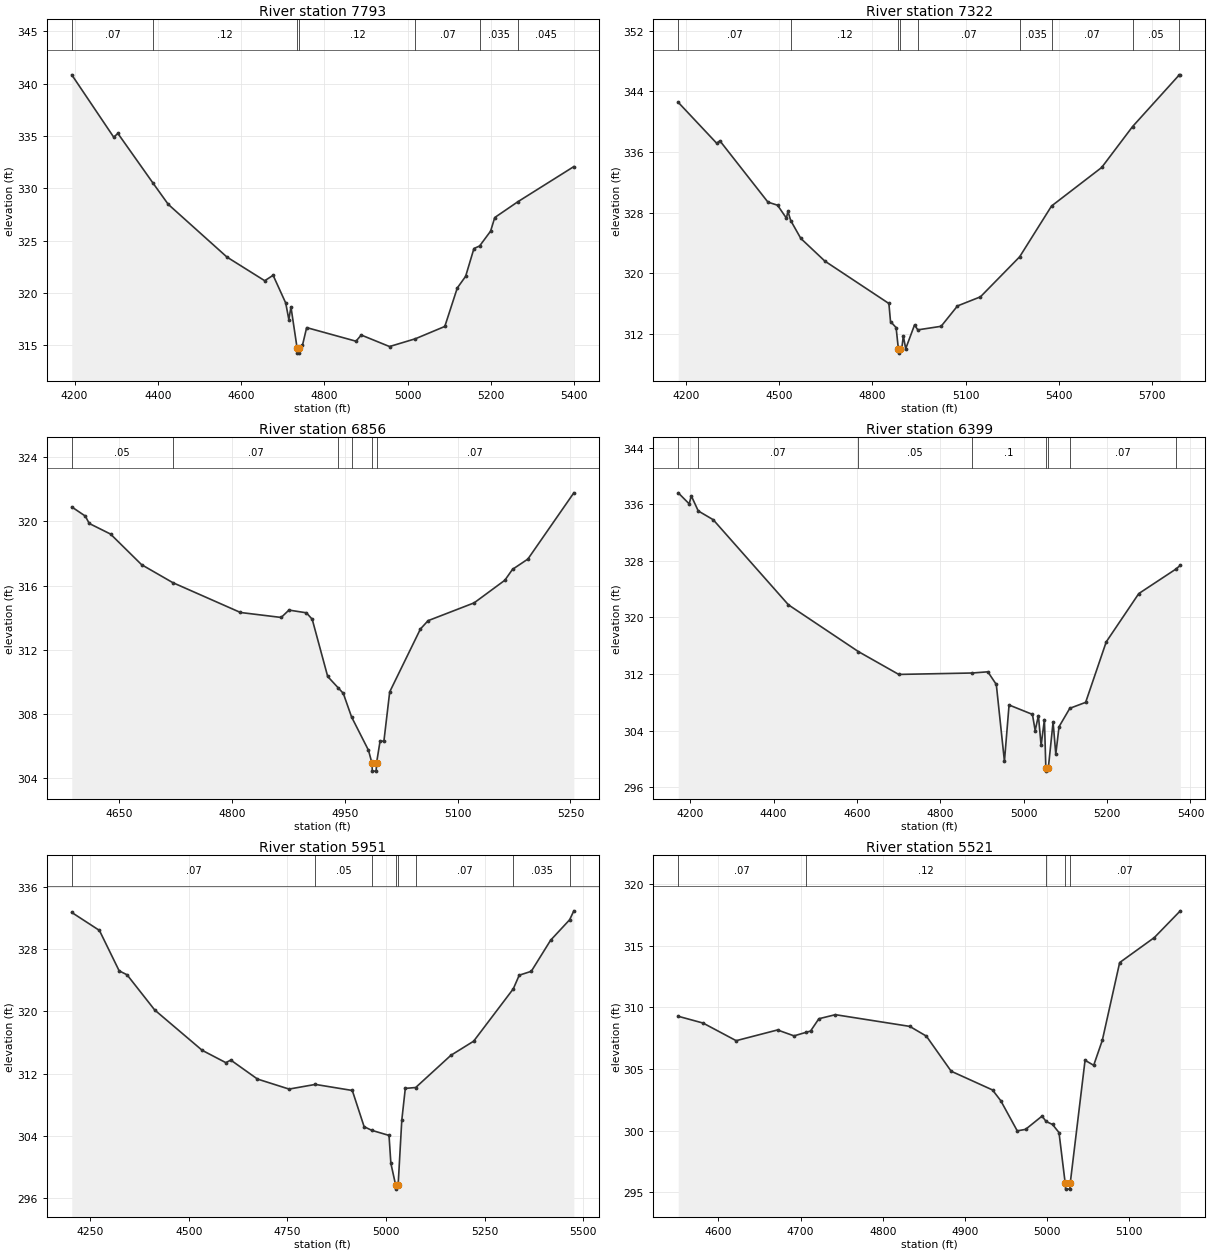
Type RM Length L Ch R = 1 ,7793    ,471,471,471
BEGIN DESCRIPTION:
Stream0797 17.0
END DESCRIPTION:
XS GIS Cut Line= 3
      2435525.01       13578675.        2436325.       13578775.
      2436724.99       13578775.
#Sta/Elev= 30
  4193.4  340.84  4294.2  334.88  4304.2  335.24  4388.6  330.49  4425.2  328.46
  4566.3  323.42    4657  321.16  4677.1  321.68  4707.4  319.03  4714.9  317.45
    4720  318.65  4734.7  314.74  4735.2  314.24    4740  314.24  4740.4  314.74
  4747.7     315  4757.7  316.68  4876.2  315.38  4888.8  315.97  4956.8  314.87
  5018.7  315.61  5089.6  316.79  5119.6  320.47  5139.6  321.58  5159.6  324.24
  5173.2  324.48  5199.6   325.9  5209.6   327.2  5265.1  328.71  5399.6  332.07
#Mann= 7 ,-1 , 0
  4193.4     .07       0  4388.6     .12       0  4734.7     .05       0
  4740.4     .12       0  5018.7     .07       0  5173.2    .035       0
  5265.1    .045       0
Bank Sta=4734.7,4740.4
XS Rating Curve= 0 ,0
Exp/Cntr=0.3,0.1

Type RM Length L Ch R = 1 ,7322    ,466,466,466
BEGIN DESCRIPTION:
Stream0797 16.0
END DESCRIPTION:
XS GIS Cut Line= 3
      2435425.02       13578975.        2436225.       13579175.
      2436975.03     13579425.01
#Sta/Elev= 30
  4175.8  342.55  4299.5  337.15  4309.8  337.47  4464.4  329.38  4495.3  328.97
  4523.7  327.27  4528.8  328.16  4537.6  326.95  4570.1  324.59  4647.4   321.6
  4853.5     316  4858.7  313.62  4876.7  312.82  4884.1  309.95  4884.6  309.45
  4889.9  309.95  4894.7  309.99  4899.9  311.71  4907.6  310.04    4936  313.17
  4946.5  312.52  5021.5  312.99  5074.2  315.68    5148  316.88  5274.1  322.16
  5376.8  328.87    5538  333.95  5637.6  339.36  5787.6  346.17    5791  346.18
#Mann= 9 ,-1 , 0
  4175.8     .07       0  4537.6     .12       0  4884.1     .05       0
  4889.9     .12       0  4946.5     .07       0  5274.1    .035       0
  5376.8     .07       0  5637.6     .05       0  5787.6    .045       0
Bank Sta=4884.1,4889.9
XS Rating Curve= 0 ,0
Exp/Cntr=0.3,0.1

Type RM Length L Ch R = 1 ,6856    ,457,457,457
BEGIN DESCRIPTION:
Stream0797 15.0
END DESCRIPTION:
XS GIS Cut Line= 3
      2435875.02       13579725.        2436275.       13579625.
      2436524.96     13579575.01
#Sta/Elev= 30
  4587.3   320.9  4605.3  320.33  4610.5  319.87  4638.8  319.21  4680.1   317.3
  4721.6  316.18  4811.5  314.32  4865.6  314.01  4875.9  314.47  4899.1   314.3
  4906.8   313.9  4927.4  310.33  4941.2  309.63  4948.1  309.28  4959.1  307.81
  4981.6  305.73  4986.2  304.93  4986.7  304.43  4991.8  304.43  4992.3  304.93
    4997   306.3  5002.1   306.3  5009.8  309.37  5050.6  313.29  5060.8  313.81
    5122  314.92  5162.8  316.33    5173  317.01  5193.4  317.65  5254.5  321.78
#Mann= 6 ,-1 , 0
  4587.3     .05       0  4721.6     .07       0  4941.2      .1       0
  4959.1     .07       0  4986.2     .05       0  4992.3     .07       0
Bank Sta=4986.2,4992.3
XS Rating Curve= 0 ,0
Exp/Cntr=0.3,0.1

Type RM Length L Ch R = 1 ,6399    ,448,448,448
BEGIN DESCRIPTION:
Stream0797 14.0
END DESCRIPTION:
XS GIS Cut Line= 3
      2435625.03       13580175.        2436425.       13580025.
      2436674.98     13579725.02
#Sta/Elev= 30
  4171.2   337.6  4197.5  336.04  4202.5  337.18  4219.2  335.04  4255.1   333.8
  4435.7  321.76  4603.3  315.16  4700.2  311.93  4876.4  312.13  4913.9   312.3
  4934.2  310.51  4953.7  299.65  4964.8  307.61  5020.9  306.28  5027.4  303.99
  5035.2  306.11  5041.7  301.89  5049.6  305.55    5053  298.76  5053.5  298.26
  5059.1  298.76  5070.4   305.2  5076.9  300.66  5084.7  304.54  5110.5  307.14
  5148.5  307.98  5197.9  316.53    5276  323.36  5364.5   326.8  5375.6  327.35
#Mann= 8 ,-1 , 0
  4171.2    .035       0  4219.2     .07       0  4603.3     .05       0
  4876.4      .1       0    5053     .05       0  5059.1      .1       0
  5110.5     .07       0  5364.5    .035       0
Bank Sta=5053,5059.1
XS Rating Curve= 0 ,0
Exp/Cntr=0.3,0.1

Type RM Length L Ch R = 1 ,5951    ,430,430,430
BEGIN DESCRIPTION:
Stream0797 13.0
END DESCRIPTION:
XS GIS Cut Line= 3
      2435725.03       13580375.        2436525.       13580325.
      2436924.98     13580075.01
#Sta/Elev= 30
    4203  332.73  4273.1  330.42  4323.2  325.22  4343.2  324.71  4413.4  320.18
  4533.6     315  4593.7  313.41  4606.3  313.74  4673.9   311.3    4754  310.01
  4820.7  310.61  4914.4  309.83  4944.4  305.17  4963.9   304.7  5007.5  304.05
  5012.2  300.46  5024.4  297.64  5024.9  297.14  5030.6  297.64  5039.9  306.01
  5048.8   310.1  5075.1  310.21  5164.3  314.35  5222.1  316.17  5322.7  322.91
  5337.7  324.66  5368.3  325.16  5417.3  329.16  5465.5  331.79  5476.2  332.94
#Mann= 8 ,-1 , 0
    4203     .07       0  4820.7     .05       0  4963.9     .12       0
  5024.4     .05       0  5030.6     .12       0  5075.1     .07       0
  5322.7    .035       0  5465.5     .05       0
Bank Sta=5024.4,5030.6
XS Rating Curve= 0 ,0
Exp/Cntr=0.3,0.1

Type RM Length L Ch R = 1 ,5521    ,442,442,442
BEGIN DESCRIPTION:
Stream0797 12.0
END DESCRIPTION:
XS GIS Cut Line= 3
      2436274.98       13580625.        2436725.       13580675.
      2436874.99       13580625.
#Sta/Elev= 30
  4551.2  309.28  4581.4  308.73  4621.7   307.3    4672  308.17  4692.1  307.69
  4706.3  307.97  4712.2  308.08  4722.3  309.08  4742.4  309.41  4832.9  308.46
  4853.1  307.67  4883.3  304.82  4933.6   303.3  4943.6  302.43  4963.7  299.98
  4973.8   300.1  4993.9  301.18  4998.8  300.74  5006.6   300.5  5014.5  299.84
    5022  295.75  5022.5  295.25  5027.7  295.25  5028.2  295.75  5046.2  305.71
  5056.7   305.3  5067.2  307.33  5088.3  313.64  5130.5  315.67  5162.1  317.84
#Mann= 5 ,-1 , 0
  4551.2     .07       0  4706.3     .12       0  4998.8     .07       0
    5022     .05       0  5028.2     .07       0
Bank Sta=5022,5028.2
XS Rating Curve= 0 ,0
Exp/Cntr=0.3,0.1

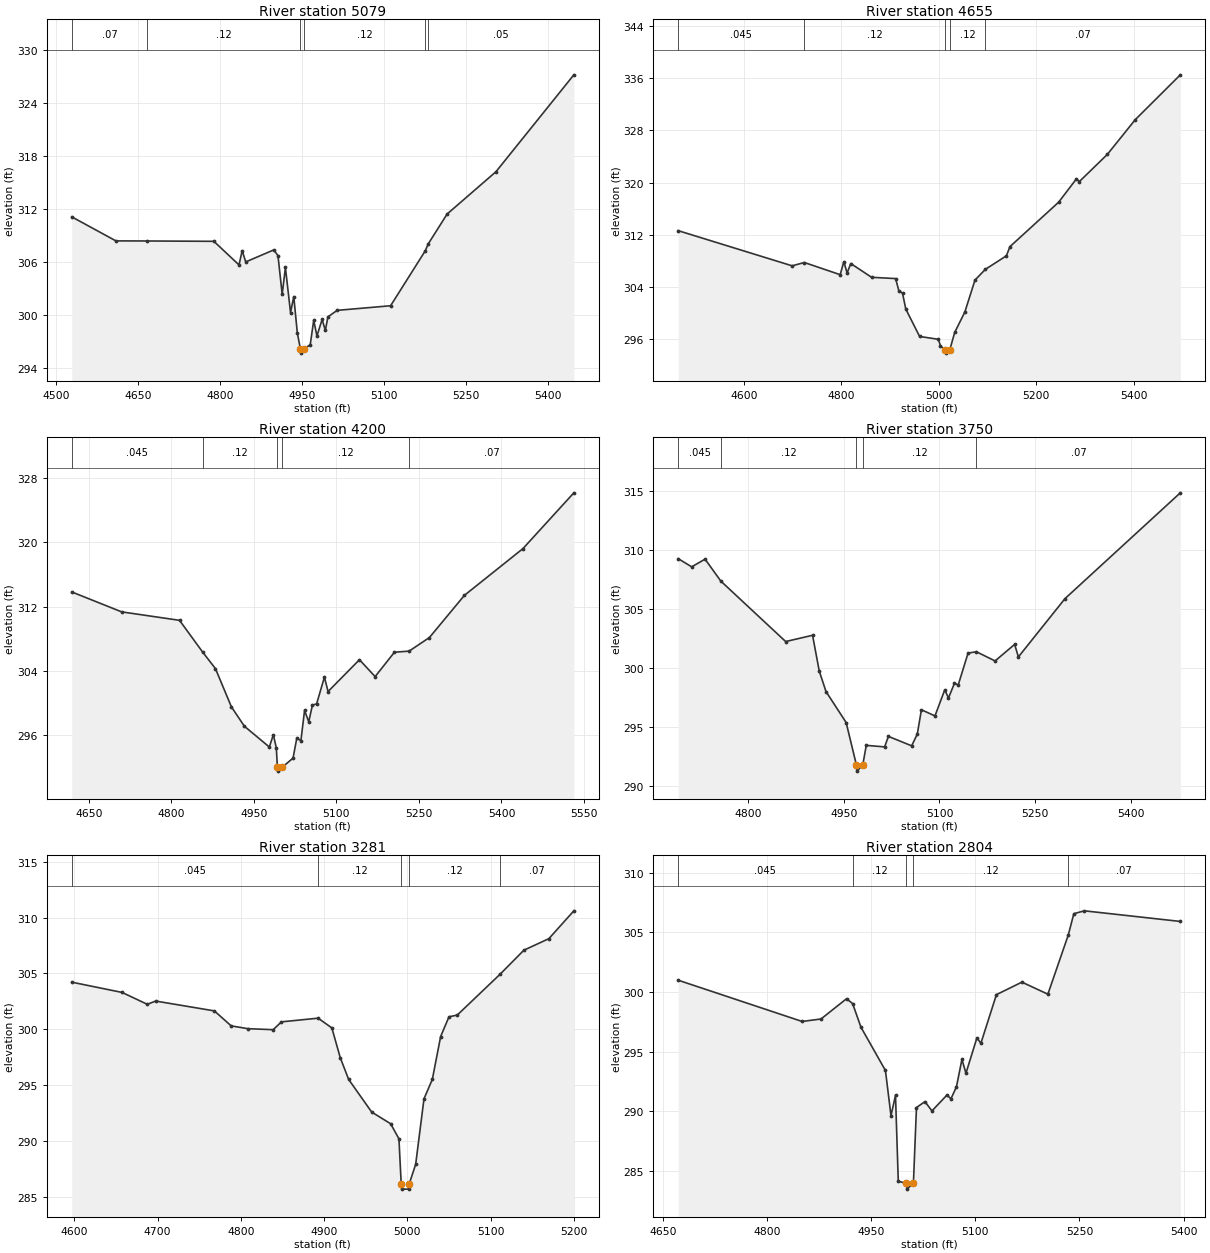
Type RM Length L Ch R = 1 ,5079    ,424,424,424
BEGIN DESCRIPTION:
Stream0797 11.0
END DESCRIPTION:
XS GIS Cut Line= 3
      2436274.97     13580774.98        2436675.       13581025.
      2437074.96     13580825.02
#Sta/Elev= 30
  4528.4  311.07  4609.2  308.35  4666.8  308.34  4788.5   308.3  4834.5  305.63
  4840.3  307.24  4846.8  305.97  4898.1  307.33  4905.8  306.68  4913.5  302.31
  4919.4  305.34  4928.8  300.24  4934.7  302.05  4941.2  297.93  4946.8  296.15
  4947.3  295.65  4953.2  296.15  4964.8  296.58  4971.2  299.37  4977.1  297.59
  4986.6  299.46  4992.5  298.22  4997.2  299.75  5014.1  300.49  5111.9  301.01
  5175.1   307.2  5181.1  308.04  5215.4  311.39  5304.8  316.18  5447.3  327.14
#Mann= 6 ,-1 , 0
  4528.4     .07       0  4666.8     .12       0  4946.8     .05       0
  4953.2     .12       0  5175.1     .07       0  5181.1     .05       0
Bank Sta=4946.8,4953.2
XS Rating Curve= 0 ,0
Exp/Cntr=0.3,0.1

Type RM Length L Ch R = 1 ,4655    ,455,455,455
BEGIN DESCRIPTION:
Stream0797 10.0
END DESCRIPTION:
XS GIS Cut Line= 3
      2436524.99     13581675.01        2436925.       13581325.
      2437324.99     13581025.01
#Sta/Elev= 30
  4464.6  312.61  4698.6  307.21  4723.7  307.72  4797.3  305.85  4804.9  307.85
  4811.5  306.11  4819.1  307.56  4861.8  305.45  4911.2  305.25  4917.8  303.39
  4925.4  303.01  4932.1  300.57  4960.5  296.36  4999.2  295.92  5003.4  294.88
  5013.5   294.3    5014   293.8  5022.5   294.3  5032.6  296.98  5053.4  300.11
  5074.2  305.01  5095.4  306.66  5138.8  308.75  5146.1  310.16  5246.1  316.98
  5282.6  320.56  5288.8  320.16  5346.1  324.32  5403.4  329.65  5496.1  336.55
#Mann= 5 ,-1 , 0
  4464.6    .045       0  4723.7     .12       0  5013.5     .05       0
  5022.5     .12       0  5095.4     .07       0
Bank Sta=5013.5,5022.5
XS Rating Curve= 0 ,0
Exp/Cntr=0.3,0.1

Type RM Length L Ch R = 1 ,4200    ,450,450,450
BEGIN DESCRIPTION:
Stream0797 9.0
END DESCRIPTION:
XS GIS Cut Line= 3
        2436725.       13581875.        2437075.       13581725.
        2437425.       13581325.
#Sta/Elev= 30
  4619.2  313.82  4709.9  311.34    4815  310.29  4856.8  306.36  4880.3  304.28
  4909.3  299.52  4932.9  297.11  4978.2  294.53  4985.5  296.06  4990.9   294.4
  4992.8  292.03  4993.3  291.53  5001.8  292.03  5021.3  293.15    5028   295.6
  5035.6  295.34  5042.2  299.08  5049.8  297.67  5056.5  299.75  5064.1  299.89
  5078.3  303.23  5084.9  301.43  5141.9  305.39  5170.4  303.29  5205.5  306.32
  5232.2  306.46  5269.1  308.15  5332.7   313.4    5439  319.21  5531.5  326.15
#Mann= 5 ,-1 , 0
  4619.2    .045       0  4856.8     .12       0  4992.8     .05       0
  5001.8     .12       0  5232.2     .07       0
Bank Sta=4992.8,5001.8
XS Rating Curve= 0 ,0
Exp/Cntr=0.3,0.1

Type RM Length L Ch R = 1 ,3750    ,469,469,469
BEGIN DESCRIPTION:
Stream0797 8.0
END DESCRIPTION:
XS GIS Cut Line= 3
      2436925.03     13582025.01        2437225.       13582125.
        2437625.       13582375.
#Sta/Elev= 30
  4690.1  309.26  4711.2  308.57  4732.2  309.22    4757  307.36  4858.7  302.25
  4900.9  302.78  4911.4  299.75    4922  298.02  4953.6   295.4  4969.8  291.79
  4970.3  291.29  4979.6  291.79  4985.2  293.47    5014  293.34  5019.9  294.23
  5056.4  293.43  5065.3  294.43  5071.7  296.48    5093  295.96  5108.3  298.16
  5114.2  297.48  5123.6  298.72  5129.5  298.58  5144.9  301.27  5157.9  301.39
  5187.3  300.61    5218  302.01  5223.9  300.95    5297  305.88    5478  314.83
#Mann= 5 ,-1 , 0
  4690.1    .045       0    4757     .12       0  4969.8     .05       0
  4979.6     .12       0  5157.9     .07       0
Bank Sta=4969.8,4979.6
XS Rating Curve= 0 ,0
Exp/Cntr=0.3,0.1

Type RM Length L Ch R = 1 ,3281    ,477,477,477
BEGIN DESCRIPTION:
Stream0797 7.0
END DESCRIPTION:
XS GIS Cut Line= 3
        2436875.       13582525.        2437275.       13582575.
      2437474.99       13582575.
#Sta/Elev= 30
  4596.8  304.22  4657.3   303.3  4687.5  302.24  4697.6  302.53  4768.1  301.65
  4788.3  300.31  4808.4  300.06  4838.7  299.97  4848.7  300.67  4892.7     301
  4909.2  300.13  4919.3  297.47  4929.4  295.52  4957.1   292.6  4979.8  291.56
  4989.8  290.21  4992.5  286.21    4993  285.71  5001.8  285.71  5002.3  286.21
  5009.9  287.93  5019.9  293.79  5029.9  295.52  5039.9  299.36  5049.9  301.12
  5059.9  301.28  5111.3  304.93  5139.9  307.08  5169.9  308.11  5199.9   310.6
#Mann= 5 ,-1 , 0
  4596.8    .045       0  4892.7     .12       0  4992.5     .05       0
  5002.3     .12       0  5111.3     .07       0
Bank Sta=4992.5,5002.3
XS Rating Curve= 0 ,0
Exp/Cntr=0.3,0.1

Type RM Length L Ch R = 1 ,2804    ,442,442,442
BEGIN DESCRIPTION:
Stream0797 6.0
END DESCRIPTION:
XS GIS Cut Line= 3
        2436925.       13582825.        2437175.       13583025.
      2437525.03     13582824.98
#Sta/Elev= 30
  4672.1  300.98  4850.6  297.52  4877.8  297.73  4914.6  299.43  4923.3  299.02
  4935.4  297.03  4970.6  293.41  4978.6  289.62  4985.1  291.33  4989.1  284.11
  5000.9  283.96  5001.4  283.46  5010.9  283.96  5015.3   290.3  5027.5   290.8
  5037.6  290.02  5059.2  291.35    5065  291.04  5072.9  292.04  5080.8  294.34
  5086.6  293.18  5102.4  296.15  5108.1  295.69  5130.5  299.77  5167.2  300.82
  5204.6  299.81    5234  304.77    5242  306.56  5257.2   306.8  5395.4  305.91
#Mann= 5 ,-1 , 0
  4672.1    .045       0  4923.3     .12       0  5000.9     .05       0
  5010.9     .12       0    5234     .07       0
Bank Sta=5000.9,5010.9
XS Rating Curve= 0 ,0
Exp/Cntr=0.3,0.1

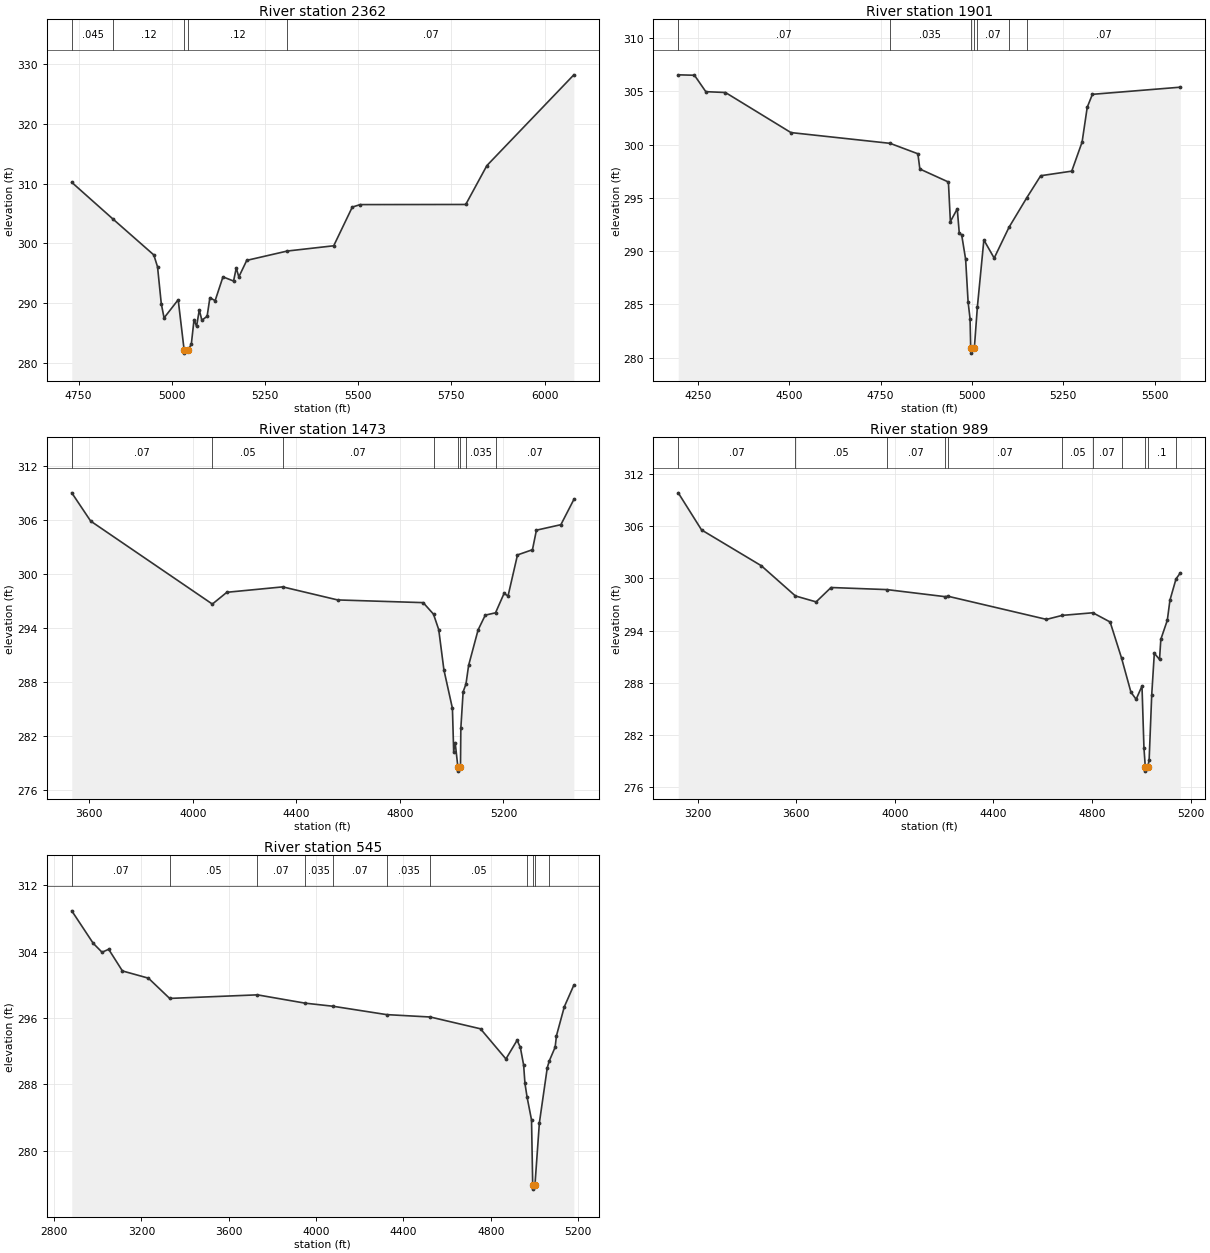
Type RM Length L Ch R = 1 ,2362    ,461,461,461
BEGIN DESCRIPTION:
Stream0797 5.0
END DESCRIPTION:
XS GIS Cut Line= 3
      2436775.04       13583425.        2437025.       13583425.
      2437824.96     13582675.03
#Sta/Elev= 30
  4731.8   310.2  4842.7  304.04  4951.8  298.06  4961.8  296.07  4971.8  289.93
  4979.3  287.52  5017.2  290.56  5033.2  282.13  5033.7  281.63  5043.2  282.13
  5052.4  283.11  5059.7  287.23  5066.5  286.11  5073.8  288.86  5080.7  287.13
  5094.8  287.79  5102.2   290.9  5116.3  290.41  5137.3  294.39  5165.7  293.69
    5173  295.87  5179.8  294.38  5201.1  297.15  5309.7  298.71  5434.3  299.59
  5484.1  306.06  5505.2  306.48  5788.4   306.5  5845.1  313.01  6078.3  328.19
#Mann= 5 ,-1 , 0
  4731.8    .045       0  4842.7     .12       0  5033.2     .05       0
  5043.2     .12       0  5309.7     .07       0
Bank Sta=5033.2,5043.2
XS Rating Curve= 0 ,0
Exp/Cntr=0.3,0.1

Type RM Length L Ch R = 1 ,1901    ,428,428,428
BEGIN DESCRIPTION:
Stream0797 4.0
END DESCRIPTION:
XS GIS Cut Line= 3
      2436625.01       13583925.        2437375.       13583625.
      2437775.03     13583224.97
#Sta/Elev= 30
  4196.4  306.54  4240.8   306.5  4271.8  304.96  4325.6  304.88  4504.7  301.12
  4775.9  300.11    4852  299.13  4857.4   297.7  4935.5  296.48  4940.9  292.77
  4959.7  293.96  4965.1  291.73  4971.9   291.5  4982.6  289.23  4989.4   285.2
  4994.7  283.66  4996.5  280.92    4997  280.42  5006.5  280.92  5014.7  284.74
  5032.5  291.04  5060.7  289.34  5101.1  292.22  5150.2  295.02    5188  297.07
  5272.9   297.5  5301.2  300.23  5315.3   303.5  5329.4  304.71  5569.9  305.38
#Mann= 7 ,-1 , 0
  4196.4     .07       0  4775.9    .035       0  4996.5    .035       0
  5006.5    .035       0  5014.7     .07       0  5101.1     .12       0
  5150.2     .07       0
Bank Sta=4996.5,5006.5
XS Rating Curve= 0 ,0
Exp/Cntr=0.3,0.1

Type RM Length L Ch R = 1 ,1473    ,484,484,484
BEGIN DESCRIPTION:
Stream0797 3.0
END DESCRIPTION:
XS GIS Cut Line= 5
      2436522.56     13583964.24      2437442.71     13584082.29
        2437725.     13583846.18        2437725.       13583675.
      2437975.01     13583274.99
#Sta/Elev= 30
  3533.1  309.04  3606.1   305.9  4075.9  296.68  4131.9  297.99  4347.7  298.59
  4559.7  297.14    4890  296.84  4929.8  295.56    4950  293.84    4970  289.37
  5002.9  285.09  5007.7  280.28  5013.5  281.28  5023.8  278.62  5024.3  278.12
    5034  278.62  5035.4  282.91  5044.2  286.93  5055.2   287.8  5065.4  289.87
    5102  293.81  5129.7  295.45  5169.3  295.71  5202.2  297.86  5217.6  297.58
  5254.1  302.14  5311.9  302.72  5327.2  304.89  5421.6   305.5  5471.7   308.3
#Mann= 8 ,-1 , 0
  3533.1     .07       0  4075.9     .05       0  4347.7     .07       0
  4929.8      .1       0  5023.8     .05       0    5034      .1       0
  5055.2    .035       0  5169.3     .07       0
Bank Sta=5023.8,5034
XS Rating Curve= 0 ,0
Exp/Cntr=0.3,0.1

Type RM Length L Ch R = 1 ,989     ,444,444,444
BEGIN DESCRIPTION:
Stream0797 2.0
END DESCRIPTION:
XS GIS Cut Line= 5
      2436491.35     13583988.55      2437776.04      13584169.1
      2438130.42     13583908.75        2438175.       13583775.
      2438224.99     13583625.04
#Sta/Elev= 30
  3121.7  309.82  3216.3  305.56  3458.6  301.45    3597  297.98  3680.8   297.3
  3741.4  298.95    3968  298.71  4203.9   297.9  4215.1  297.95  4615.1  295.29
  4678.9  295.75  4803.3  296.05  4873.2  294.99  4919.6  290.84  4957.6  286.93
  4978.6  286.12  5002.4  287.64  5010.3  280.56  5015.7  278.37  5016.2  277.87
    5026  278.37  5031.4  279.18  5041.9  286.65  5052.4   291.4  5073.5  290.69
  5078.8     293  5105.1  295.19  5115.7  297.49  5140.4  299.94  5157.8  300.62
#Mann= 11 ,-1 , 0
  3121.7     .07       0    3597     .05       0    3968     .07       0
  4203.9    .035       0  4215.1     .07       0  4678.9     .05       0
  4803.3     .07       0  4919.6      .1       0  5015.7     .05       0
    5026      .1       0  5140.4    .035       0
Bank Sta=5015.7,5026
XS Rating Curve= 0 ,0
Exp/Cntr=0.3,0.1

Type RM Length L Ch R = 1 ,545     ,0,0,0
BEGIN DESCRIPTION:
Stream0797 1.0
END DESCRIPTION:
XS GIS Cut Line= 5
      2436487.82     13584016.32      2438123.26     13584259.38
      2438399.92     13584108.39        2438525.       13584025.
      2438625.01     13583874.99
#Sta/Elev= 30
  2881.3   308.9  2979.5  304.99    3020  303.91  3050.3  304.27  3113.2  301.66
  3232.3  300.79  3329.6  298.35  3731.2  298.78  3949.6  297.78  4076.7  297.41
  4322.9   296.4  4523.3  296.11  4753.1  294.69  4869.5  291.06  4920.6  293.31
  4935.6  292.44  4950.6  290.32  4956.6  288.11  4966.5  286.44  4986.7  283.71
  4992.1  275.88  4992.6  275.38  5002.4  275.88  5022.7  283.37  5058.8     290
  5068.1  290.83  5094.9  292.48  5100.9  293.86  5136.9  297.35  5180.5  299.95
#Mann= 11 ,-1 , 0
  2881.3     .07       0  3329.6     .05       0  3731.2     .07       0
  3949.6    .035       0  4076.7     .07       0  4322.9    .035       0
  4523.3     .05       0  4966.5      .1       0  4992.1     .05       0
  5002.4      .1       0  5068.1     .07       0
Bank Sta=4992.1,5002.4
XS Rating Curve= 0 ,0
Exp/Cntr=0.3,0.1

Chan Stop Cuts=-1
Use User Specified Reach Order=0
Composite Channel Slope=5