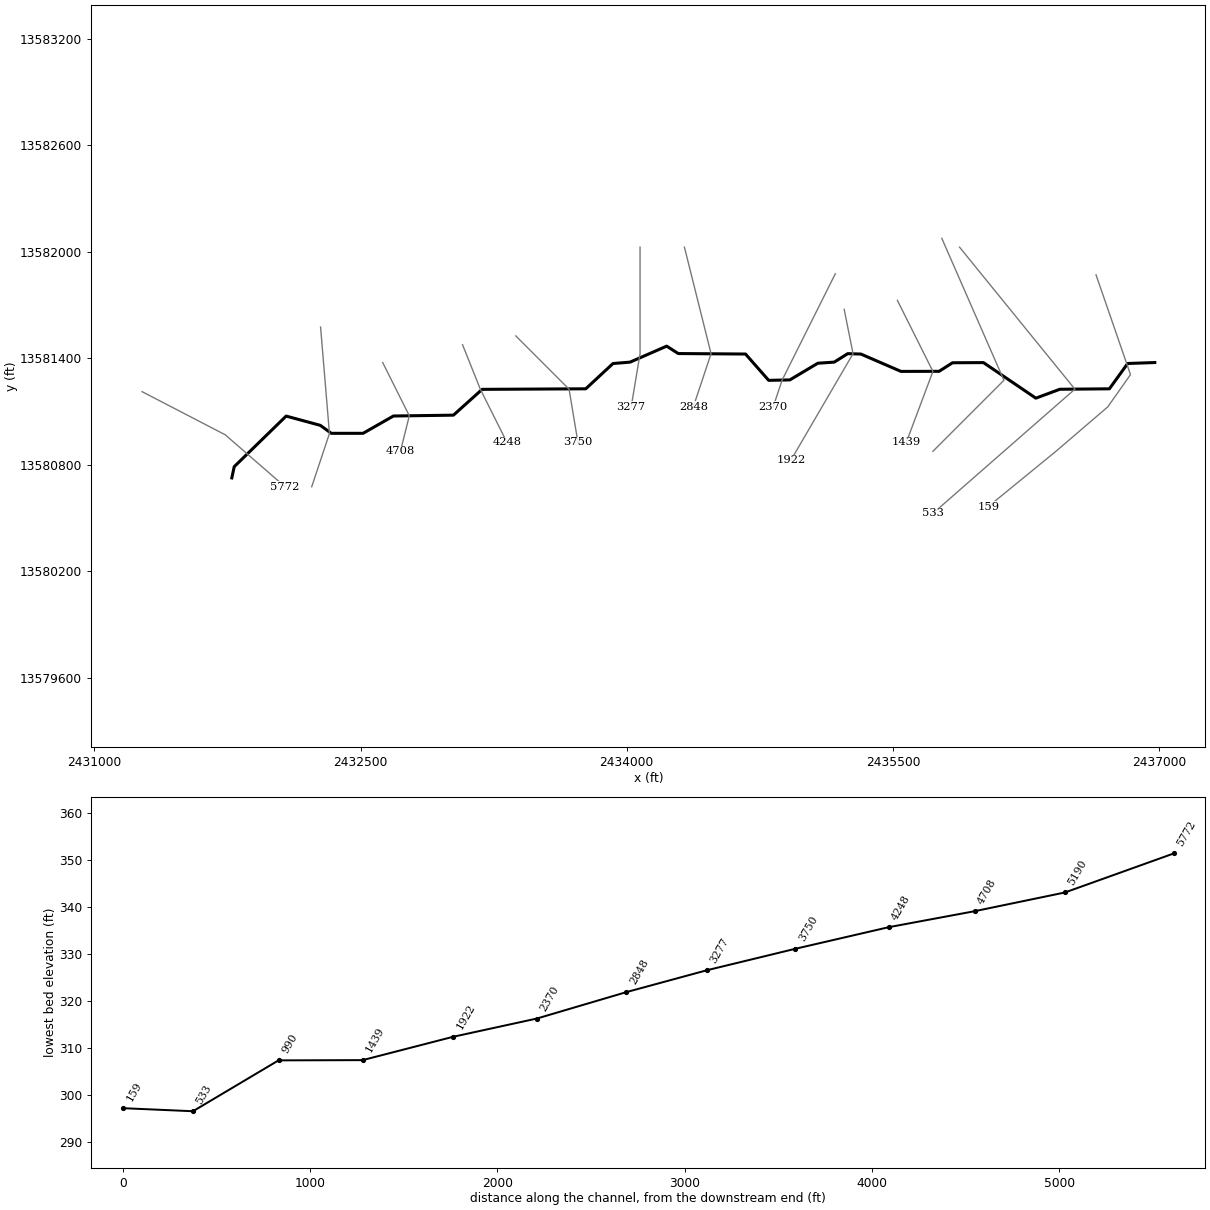
--- Stream0798.prj (project) ---

Proj Title=Stream0798 Base Level Engineering
Current Plan=p01
Default Exp/Contr=0.3,0.1
English Units
Geom File=g01
Flow File=f01
Plan File=p01
BEGIN DESCRIPTION:
Stream0798
END DESCRIPTION:

--- Stream0798.p01 (plan) ---

Plan Title=Multiple Run
Short Identifier=Multiple
Geom File=g01
Flow File=f01
Subcritical Flow
K Sum by GR= 0
Std Step Tol= 0.01
Critical Tol= 0.01
Num of Std Step Trials= 20
Max Error Tol= 0.3
Flow Tol Ratio= 0.001
Split Flow NTrial= 30
Split Flow Tol= 0.02
Split Flow Ratio= 0.02
Log Output Level= 0
Friction Slope Method= 1
Unsteady Friction Slope Method= 2
Unsteady Bridges Friction Slope Method= 1
Parabolic Critical Depth
Global Vel Dist=  1 , 1 , 1
Global Log Level= 0
CheckData=True
Encroach Param= -1, 0, 0, 0
BEGIN DESCRIPTION:
Multiple Run
END DESCRIPTION:

--- Stream0798.f01 (steady flow) ---

Flow Title=Multiple
Number of Profiles=7
Profile Names=10-year,25-year,50-year,1pct_min,100-year,1pct_plu,500-year
River Rch & RM= Stream0798,Reach-1,5772
     541     873    1173     765    1526    3044    2557
River Rch & RM= Stream0798,Reach-1,4248
     697    1139    1543    1013    2021    4033    3436
River Rch & RM= Stream0798,Reach-1,1439
     755    1242    1690    1115    2224    4437    3814
Boundary for River Rch & Prof#=Stream0798,Reach-1,1
Up Type=0
Dn Type=3
Dn Slope=0.005
Boundary for River Rch & Prof#=Stream0798,Reach-1,2
Up Type=0
Dn Type=3
Dn Slope=0.005
Boundary for River Rch & Prof#=Stream0798,Reach-1,3
Up Type=0
Dn Type=3
Dn Slope=0.005
Boundary for River Rch & Prof#=Stream0798,Reach-1,4
Up Type=0
Dn Type=3
Dn Slope=0.005
Boundary for River Rch & Prof#=Stream0798,Reach-1,5
Up Type=0
Dn Type=3
Dn Slope=0.005
Boundary for River Rch & Prof#=Stream0798,Reach-1,6
Up Type=0
Dn Type=3
Dn Slope=0.005
Boundary for River Rch & Prof#=Stream0798,Reach-1,7
Up Type=0
Dn Type=3
Dn Slope=0.005

--- Stream0798.g01 (geometry) ---

Geom Title=Existing Conditions

River Reach=Stream0798,Reach-1
Reach XY= 30
      2431775.00     13580725.00      2431788.47     13580788.27
      2432081.03     13581073.38      2432273.40     13581021.14
      2432335.50     13580976.22      2432514.50     13580976.20
      2432685.50     13581073.80      2433023.54     13581078.54
      2433185.43     13581223.95      2433769.15     13581227.06
      2433922.57     13581369.48      2434019.02     13581377.36
      2434225.00     13581467.44      2434290.16     13581425.66
      2434669.16     13581422.95      2434799.80     13581274.64
      2434919.06     13581277.22      2435076.58     13581371.17
      2435169.03     13581377.36      2435245.10     13581425.10
      2435319.03     13581422.83      2435545.03     13581325.07
      2435759.78     13581325.52      2435835.51     13581373.78
      2436009.84     13581374.62      2436304.92     13581174.33
      2436440.22     13581224.48      2436719.33     13581226.98
      2436822.28     13581369.67      2436975.00     13581375.00

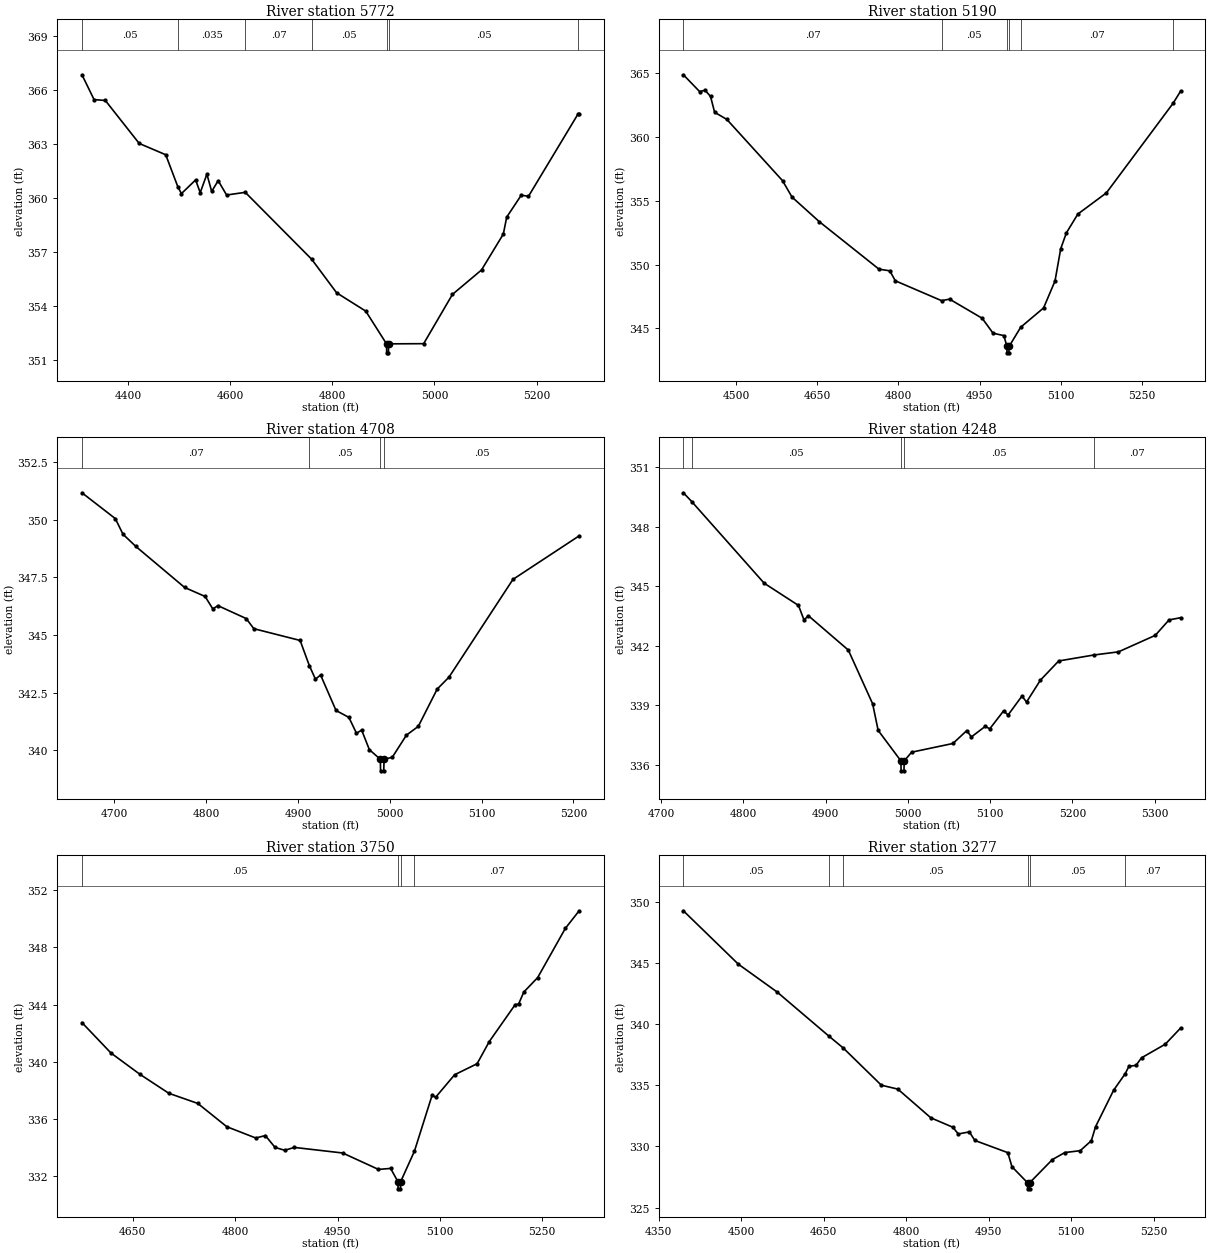
Type RM Length L Ch R = 1,5772,582,582,582
BEGIN DESCRIPTION:
Stream0798 12.0
END DESCRIPTION:
XS GIS Cut Line= 3
      2431269.22     13581211.00      2431737.93     13580967.97
      2432075.03     13580674.98
#Sta/Elev= 30
  4309.0  366.86  4332.7  365.48  4354.8  365.43  4421.2  363.04  4473.2  362.41
  4497.2  360.61  4504.0  360.25  4531.8  361.01  4540.8  360.30  4553.9  361.33
  4563.3  360.37  4576.0  360.97  4592.5  360.17  4629.1  360.32  4759.2  356.60
  4808.2  354.73  4865.3  353.71  4906.0  351.89  4906.3  351.39  4909.8  351.39
  4910.0  351.89  4978.8  351.90  5035.2  354.64  5092.2  356.00  5135.0  358.00
  5141.6  358.94  5170.1  360.16  5184.3  360.10  5281.9  364.70  5283.6  364.70
#Mann=7,-1,0
  4309.0    0.05       0  4497.2   0.035       0  4629.1    0.07       0
  4759.2    0.05       0  4906.0    0.05       0  4910.0    0.05       0
  5281.9    0.07       0
Bank Sta=4906,4910
Exp/Cntr=0.3,0.1

Type RM Length L Ch R = 1,5190,482,482,482
BEGIN DESCRIPTION:
Stream0798 11.0
END DESCRIPTION:
XS GIS Cut Line= 3
      2432275.00     13581575.00      2432325.00     13580975.00
      2432225.00     13580675.01
#Sta/Elev= 30
  4402.7  364.88  4432.8  363.56  4442.8  363.67  4452.9  363.18  4460.4  361.94
  4483.0  361.38  4585.8  356.58  4603.4  355.29  4653.6  353.37  4764.0  349.64
  4784.0  349.51  4794.1  348.73  4879.6  347.17  4894.4  347.29  4954.6  345.79
  4974.7  344.62  4994.7  344.43  5000.3  343.58  5000.5  343.08  5004.0  343.08
  5004.3  343.58  5025.8  345.09  5068.0  346.60  5089.1  348.71  5099.7  351.25
  5110.2  352.49  5131.3  353.96  5184.0  355.62  5307.3  362.65  5321.0  363.59
#Mann=6,-1,0
  4402.7    0.07       0  4879.6    0.05       0  5000.3    0.05       0
  5004.3    0.05       0  5025.8    0.07       0  5307.3    0.05       0
Bank Sta=5000.3,5004.3
Exp/Cntr=0.3,0.1

Type RM Length L Ch R = 1,4708,460,460,460
BEGIN DESCRIPTION:
Stream0798 10.0
END DESCRIPTION:
XS GIS Cut Line= 3
      2432625.01     13581374.98      2432775.00     13581075.00
      2432725.01     13580875.04
#Sta/Elev= 30
  4664.7  351.17  4701.0  350.05  4709.4  349.37  4723.4  348.84  4776.5  347.06
  4798.8  346.67  4807.2  346.13  4812.8  346.27  4843.6  345.71  4851.9  345.27
  4902.3  344.76  4912.3  343.67  4919.0  343.08  4924.6  343.26  4941.4  341.72
  4955.4  341.42  4963.7  340.73  4969.3  340.87  4977.7  340.02  4989.7  339.60
  4989.9  339.10  4993.4  339.10  4993.7  339.60  5002.7  339.69  5018.1  340.65
  5031.0  341.03  5051.6  342.65  5064.5  343.17  5134.1  347.41  5206.2  349.30
#Mann=4,-1,0
  4664.7    0.07       0  4912.3    0.05       0  4989.7    0.05       0
  4993.7    0.05       0
Bank Sta=4989.7,4993.7
Exp/Cntr=0.3,0.1

Type RM Length L Ch R = 1,4248,498,498,498
BEGIN DESCRIPTION:
Stream0798 9.0
END DESCRIPTION:
XS GIS Cut Line= 3
      2433075.01     13581474.99      2433175.00     13581225.00
      2433325.02     13580924.96
#Sta/Elev= 30
  4726.9  349.71  4737.0  349.27  4825.2  345.15  4866.9  344.03  4873.6  343.30
  4879.0  343.51  4927.5  341.78  4957.1  339.07  4963.8  337.73  4991.5  336.19
  4991.7  335.69  4995.2  335.69  4995.5  336.19  5004.5  336.63  5054.8  337.07
  5071.6  337.72  5077.2  337.40  5094.0  337.93  5099.6  337.81  5116.3  338.71
  5121.9  338.51  5138.7  339.46  5144.3  339.16  5161.1  340.26  5183.4  341.23
  5226.1  341.53  5256.1  341.69  5300.8  342.52  5317.6  343.30  5331.6  343.41
#Mann=5,-1,0
  4726.9    0.07       0  4737.0    0.05       0  4991.5    0.05       0
  4995.5    0.05       0  5226.1    0.07       0
Bank Sta=4991.5,4995.5
Exp/Cntr=0.3,0.1

Type RM Length L Ch R = 1,3750,473,473,473
BEGIN DESCRIPTION:
Stream0798 8.0
END DESCRIPTION:
XS GIS Cut Line= 3
      2433374.97     13581525.03      2433675.00     13581225.00
      2433724.99     13580925.04
#Sta/Elev= 30
  4575.6  342.74  4618.1  340.61  4660.5  339.12  4702.9  337.79  4745.3  337.08
  4787.8  335.45  4830.2  334.66  4844.3  334.83  4858.5  334.00  4872.6  333.80
  4886.8  334.00  4957.5  333.61  5010.0  332.46  5027.8  332.53  5038.5  331.60
  5038.7  331.10  5042.2  331.10  5042.5  331.60  5062.7  333.74  5088.6  337.66
  5093.7  337.51  5121.6  339.09  5154.5  339.86  5172.3  341.41  5210.3  344.00
  5215.3  344.04  5222.9  344.88  5243.2  345.89  5283.8  349.34  5304.0  350.57
#Mann=4,-1,0
  4575.6    0.05       0  5038.5    0.05       0  5042.5    0.05       0
  5062.7    0.07       0
Bank Sta=5038.5,5042.5
Exp/Cntr=0.3,0.1

Type RM Length L Ch R = 1,3277,429,429,429
BEGIN DESCRIPTION:
Stream0798 7.0
END DESCRIPTION:
XS GIS Cut Line= 3
      2434075.00     13582024.96      2434075.00     13581425.00
      2434025.00     13581125.00
#Sta/Elev= 30
  4394.9  349.28  4494.9  344.91  4564.9  342.65  4659.4  339.03  4685.7  338.05
  4754.9  335.01  4784.9  334.69  4844.9  332.34  4884.9  331.57  4894.9  331.02
  4914.9  331.19  4924.9  330.49  4984.9  329.49  4992.4  328.34  5020.7  327.03
  5021.0  326.53  5024.5  326.53  5024.7  327.03  5065.8  328.92  5088.6  329.50
  5116.5  329.65  5136.8  330.47  5144.4  331.61  5177.3  334.60  5198.2  335.94
  5205.2  336.56  5217.9  336.63  5228.0  337.25  5271.1  338.36  5299.0  339.68
#Mann=6,-1,0
  4394.9    0.05       0  4659.4    0.07       0  4685.7    0.05       0
  5020.7    0.05       0  5024.7    0.05       0  5198.2    0.07       0
Bank Sta=5020.7,5024.7
Exp/Cntr=0.3,0.1

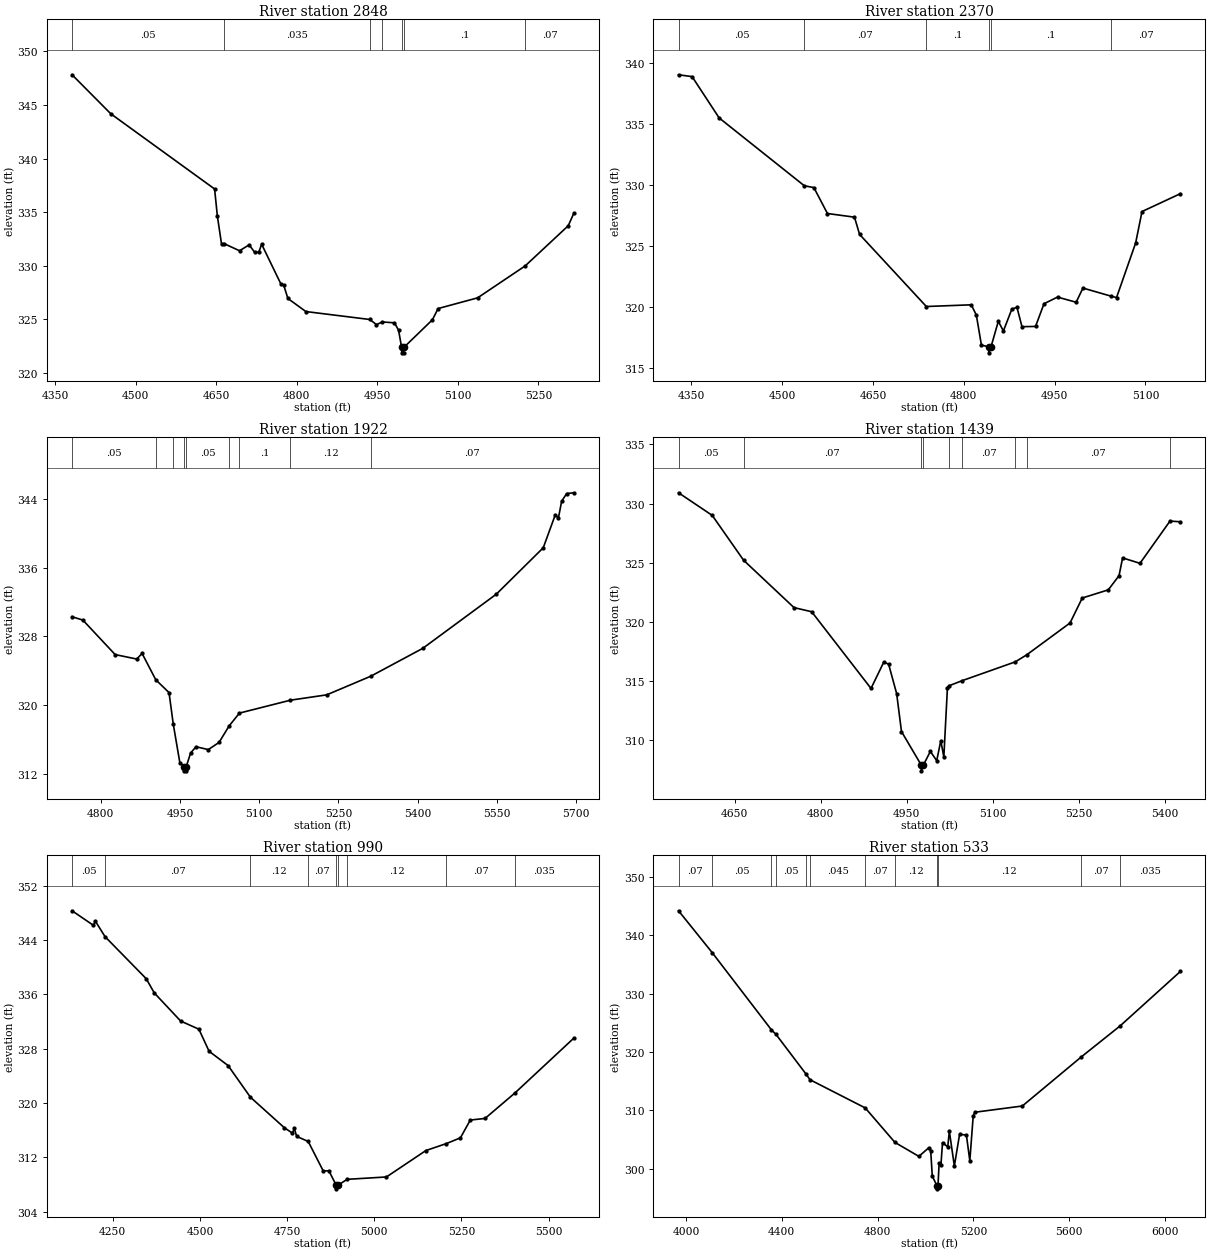
Type RM Length L Ch R = 1,2848,478,478,478
BEGIN DESCRIPTION:
Stream0798 6.0
END DESCRIPTION:
XS GIS Cut Line= 3
      2434324.99     13582025.04      2434475.00     13581425.00
      2434375.01     13581125.04
#Sta/Elev= 30
  4381.5  347.82  4453.7  344.18  4647.0  337.17  4652.1  334.66  4659.9  332.04
  4664.3  332.08  4693.4  331.41  4711.4  331.96  4721.7  331.26  4729.4  331.28
  4734.6  332.02  4770.7  328.29  4775.8  328.19  4783.5  326.96  4817.0  325.74
  4936.1  325.00  4948.5  324.52  4959.5  324.77  4982.0  324.69  4989.7  324.00
  4995.4  322.39  4995.7  321.89  4999.2  321.89  4999.4  322.39  5052.7  324.97
  5063.3  326.02  5137.0  327.02  5225.6  330.00  5305.7  333.74  5316.2  334.91
#Mann=7,-1,0
  4381.5    0.05       0  4664.3   0.035       0  4936.1    0.07       0
  4959.5     0.1       0  4995.4    0.05       0  4999.4     0.1       0
  5225.6    0.07       0
Bank Sta=4995.4,4999.4
Exp/Cntr=0.3,0.1

Type RM Length L Ch R = 1,2370,448,448,448
BEGIN DESCRIPTION:
Stream0798 5.0
END DESCRIPTION:
XS GIS Cut Line= 3
      2435175.02     13581875.03      2434875.00     13581275.00
      2434824.99     13581124.97
#Sta/Elev= 30
  4328.6  339.02  4351.0  338.87  4395.7  335.49  4536.4  329.94  4552.2  329.79
  4574.6  327.67  4619.3  327.37  4627.7  325.96  4738.0  320.06  4812.2  320.20
  4820.6  319.36  4829.0  316.90  4840.9  316.77  4841.2  316.27  4844.9  316.77
  4856.9  318.85  4865.3  318.06  4879.3  319.85  4887.7  319.99  4896.0  318.41
  4918.4  318.43  4932.4  320.29  4954.7  320.83  4985.5  320.41  4996.7  321.57
  5043.0  320.91  5052.2  320.79  5083.8  325.26  5094.3  327.83  5157.6  329.29
#Mann=6,-1,0
  4328.6    0.05       0  4536.4    0.07       0  4738.0     0.1       0
  4840.9    0.05       0  4844.9     0.1       0  5043.0    0.07       0
Bank Sta=4840.9,4844.9
Exp/Cntr=0.3,0.1

Type RM Length L Ch R = 1,1922,483,483,483
BEGIN DESCRIPTION:
Stream0798 4.0
END DESCRIPTION:
XS GIS Cut Line= 3
      2435225.01     13581674.96      2435275.00     13581425.00
      2434925.02     13580825.03
#Sta/Elev= 30
  4745.9  330.28  4766.3  329.90  4827.4  325.89  4868.2  325.37  4878.4  326.02
  4904.3  322.96  4929.4  321.47  4937.3  317.84  4949.8  313.34  4958.0  312.88
  4958.3  312.38  4961.8  312.38  4962.0  312.88  4970.2  314.45  4980.4  315.18
  5003.7  314.85  5024.0  315.68  5043.1  317.60  5062.6  319.09  5159.2  320.59
  5227.8  321.21  5311.3  323.38  5409.7  326.62  5548.7  332.91  5637.5  338.30
  5660.3  342.14  5666.1  341.74  5672.3  343.71  5681.8  344.60  5695.4  344.69
#Mann=9,-1,0
  4745.9    0.05       0  4904.3    0.07       0  4937.3    0.05       0
  4958.0    0.05       0  4962.0    0.05       0  5043.1    0.12       0
  5062.6     0.1       0  5159.2    0.12       0  5311.3    0.07       0
Bank Sta=4958,4962
Exp/Cntr=0.3,0.1

Type RM Length L Ch R = 1,1439,449,449,449
BEGIN DESCRIPTION:
Stream0798 3.0
END DESCRIPTION:
XS GIS Cut Line= 3
      2435525.01     13581724.98      2435725.00     13581325.00
      2435575.00     13580924.99
#Sta/Elev= 30
  4552.4  330.91  4611.1  329.00  4665.8  325.21  4753.6  321.21  4784.4  320.86
  4887.8  314.38  4910.1  316.61  4918.5  316.43  4932.5  313.94  4940.9  310.74
  4975.2  307.92  4975.5  307.42  4979.2  307.92  4991.2  309.06  5002.3  308.28
  5009.4  309.97  5014.7  308.59  5021.0  314.46  5023.9  314.61  5046.2  315.03
  5139.4  316.63  5159.4  317.23  5234.6  319.91  5255.9  322.02  5301.3  322.71
  5320.0  323.91  5326.2  325.41  5356.5  324.95  5408.8  328.52  5426.8  328.46
#Mann=9,-1,0
  4552.4    0.05       0  4665.8    0.07       0  4975.2    0.05       0
  4979.2    0.07       0  5023.9    0.12       0  5046.2    0.07       0
  5139.4    0.12       0  5159.4    0.07       0  5408.8   0.035       0
Bank Sta=4975.2,4979.2
Exp/Cntr=0.3,0.1

Type RM Length L Ch R = 1,990,457,457,457
BEGIN DESCRIPTION:
Stream0798 2.0
END DESCRIPTION:
XS GIS Cut Line= 3
      2435775.02     13582074.96      2436125.00     13581275.00
      2435724.97     13580874.97
#Sta/Elev= 30
  4133.5  348.32  4194.7  346.18  4200.1  346.81  4228.0  344.51  4345.9  338.33
  4369.3  336.22  4444.9  332.08  4497.2  330.88  4526.4  327.63  4581.0  325.52
  4645.0  320.86  4742.0  316.38  4765.4  315.57  4770.8  316.29  4777.5  315.09
  4810.6  314.35  4853.9  309.99  4869.8  310.04  4891.2  307.87  4891.5  307.37
  4895.2  307.87  4922.2  308.77  5035.0  309.12  5148.1  313.01  5206.6  314.03
  5247.1  314.88  5275.4  317.50  5317.8  317.74  5403.5  321.49  5572.4  329.57
#Mann=9,-1,0
  4133.5    0.05       0  4228.0    0.07       0  4645.0    0.12       0
  4810.6    0.07       0  4891.2    0.05       0  4895.2    0.07       0
  4922.2    0.12       0  5206.6    0.07       0  5403.5   0.035       0
Bank Sta=4891.2,4895.2
Exp/Cntr=0.3,0.1

Type RM Length L Ch R = 1,533,374,374,374
BEGIN DESCRIPTION:
Stream0798 1.0
END DESCRIPTION:
XS GIS Cut Line= 3
      2435874.99     13582025.02      2436525.00     13581225.00
      2435725.01     13580525.01
#Sta/Elev= 30
  3969.3  344.18  4109.8  337.01  4356.2  323.82  4376.1  323.00  4500.2  316.27
  4517.9  315.24  4748.3  310.41  4872.4  304.50  4972.1  302.11  5013.9  303.60
  5021.5  303.08  5028.1  298.73  5047.9  297.05  5048.2  296.55  5051.9  297.05
  5056.6  300.92  5064.2  300.64  5070.8  304.47  5092.6  303.74  5099.3  306.41
  5120.2  300.47  5142.0  305.88  5170.5  305.77  5184.7  301.35  5198.9  309.05
  5205.6  309.67  5403.9  310.74  5648.1  319.09  5812.2  324.47  6063.1  333.78
#Mann=12,-1,0
  3969.3    0.07       0  4109.8    0.05       0  4356.2    0.07       0
  4376.1    0.05       0  4500.2    0.07       0  4517.9   0.045       0
  4748.3    0.07       0  4872.4    0.12       0  5047.9    0.05       0
  5051.9    0.12       0  5648.1    0.07       0  5812.2   0.035       0
Bank Sta=5047.9,5051.9
Exp/Cntr=0.3,0.1

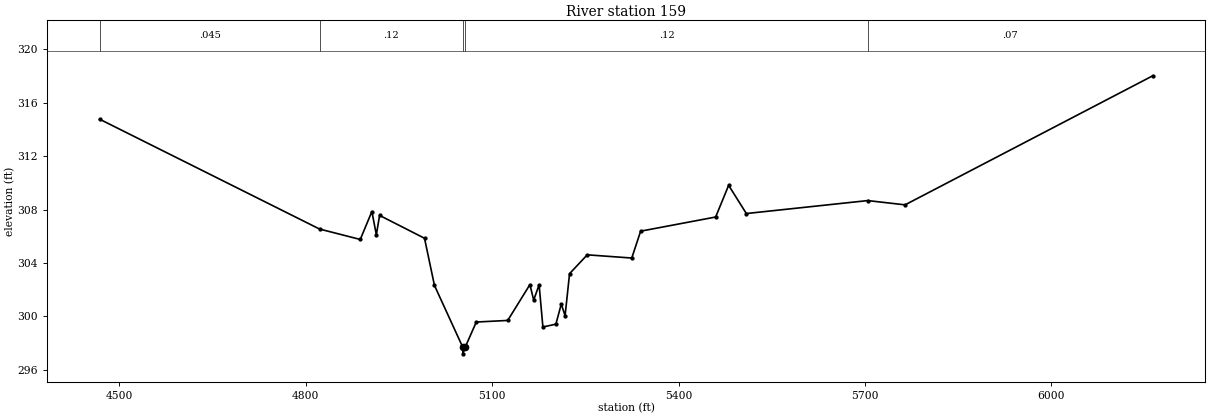
Type RM Length L Ch R = 1,159,0,0,0
BEGIN DESCRIPTION:
H21072
END DESCRIPTION:
XS GIS Cut Line= 5
      2436643.97     13581869.11      2436838.22     13581307.02
      2436710.09     13581125.15      2436420.76     13580877.15
      2436036.35     13580563.01
#Sta/Elev= 30
  4468.4  314.76  4822.3  306.54  4887.8  305.76  4906.5  307.85  4913.7  306.11
  4918.9  307.56  4991.2  305.85  5007.2  302.32  5052.7  297.70  5052.9  297.20
  5056.7  297.70  5074.5  299.58  5125.1  299.70  5160.8  302.38  5166.9  301.22
  5175.6  302.37  5181.7  299.21  5202.6  299.42  5211.3  300.93  5217.4  300.05
  5224.6  303.20  5253.1  304.61  5324.7  304.37  5339.0  306.38  5459.7  307.44
  5480.6  309.81  5509.1  307.70  5704.5  308.67  5764.5  308.35  6163.1  318.01
#Mann=5,-1,0
  4468.4   0.045       0  4822.3    0.12       0  5052.7    0.05       0
  5056.7    0.12       0  5704.5    0.07       0
Bank Sta=5052.7,5056.7
Exp/Cntr=0.3,0.1

Chan Stop Cuts=-1