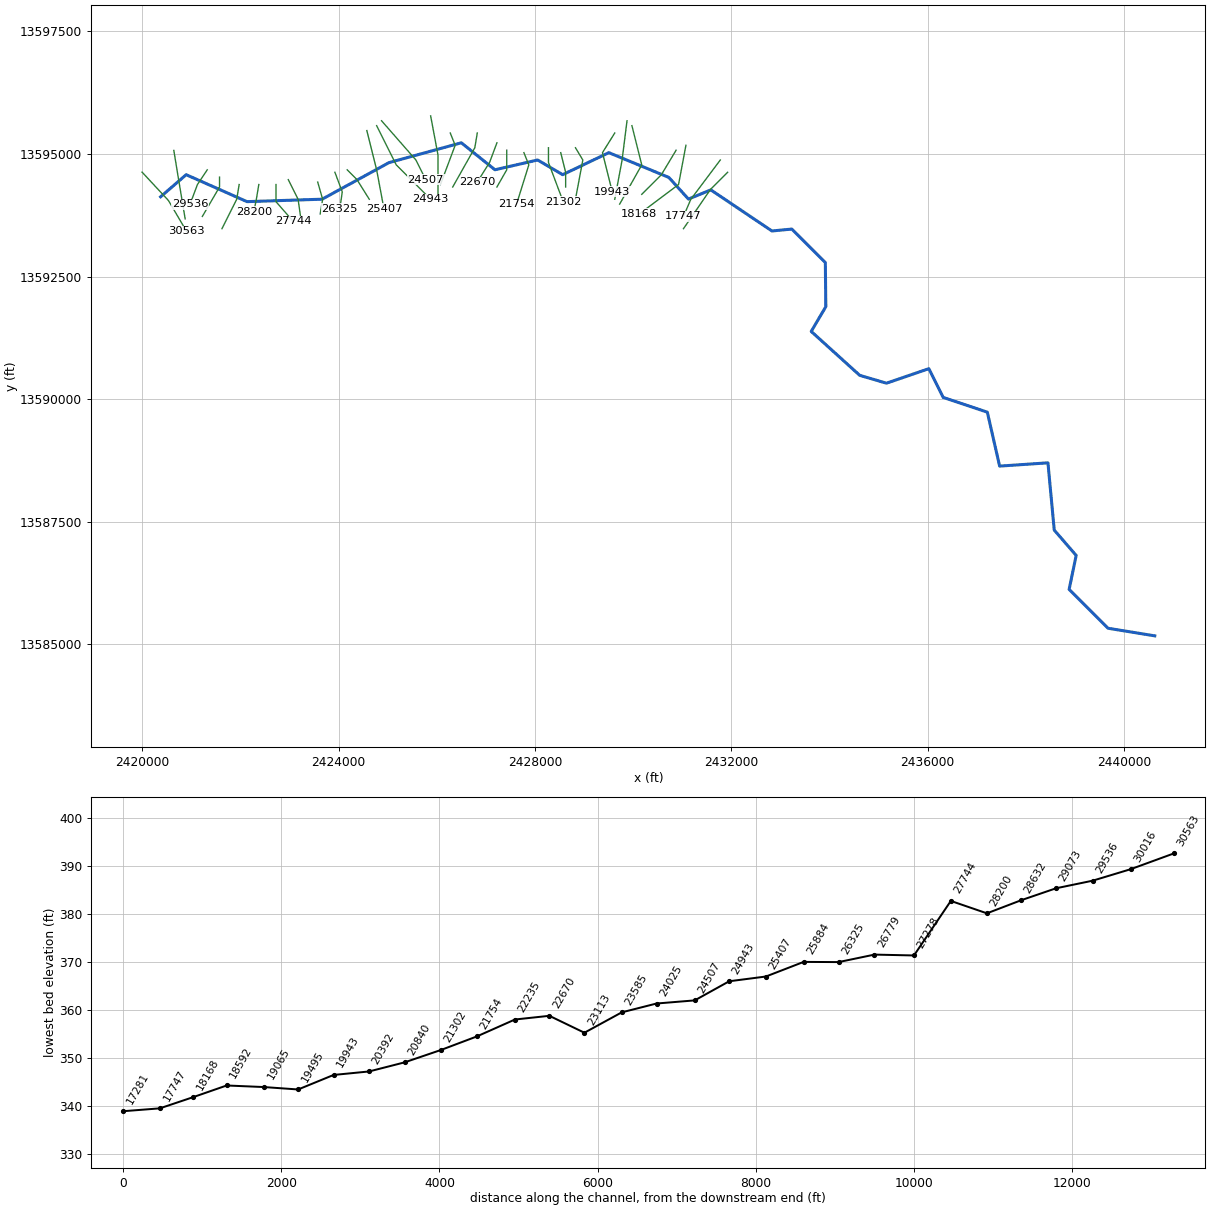
--- Stream0799.prj (project) ---

Proj Title=Stream0799 Base Level Engineering
Current Plan=p01
Default Exp/Contr=0.3,0.1
English Units
Geom File=g01
Flow File=f01
Plan File=p01
Y Axis Title=Elevation
X Axis Title(PF)=Main Channel Distance
X Axis Title(XS)=Station
BEGIN DESCRIPTION:
Stream0799
END DESCRIPTION:
DSS Export Rating Curves= 0
DSS Export Rating Curve Sorted= 0
DSS Export Volume Flow Curves= 0
DXF OffsetX= 0
DXF OffsetY= 0
DXF ScaleX= 1
DXF ScaleY= 10

--- Stream0799.p01 (plan) ---

Plan Title=Multiple Run
Short Identifier=Multiple
Geom File=g01
Flow File=f01
Subcritical Flow
K Sum by GR= 0
Std Step Tol= 0.01
Critical Tol= 0.01
Num of Std Step Trials= 20
Max Error Tol= 0.3
Flow Tol Ratio= 0.001
Split Flow NTrial= 30
Split Flow Tol= 0.02
Split Flow Ratio= 0.02
Log Output Level= 0
Friction Slope Method= 1
Unsteady Friction Slope Method= 2
Unsteady Bridges Friction Slope Method= 1
Parabolic Critical Depth
Global Vel Dist=  1 , 1 , 1
Global Log Level= 0
CheckData=True
Encroach Param= -1, 0, 0, 0
BEGIN DESCRIPTION:
Multiple Run
END DESCRIPTION:

--- Stream0799.f01 (steady flow) ---

Flow Title=Multiple
Number of Profiles=7
Profile Names=10-year,25-year,50-year,1pct_min,100-year,1pct_plu,500-year
River Rch & RM= Stream0799,Reach-1,30563
     719    1183    1610    1063    2120    4231    3642
River Rch & RM= Stream0799,Reach-1,27744
    1226    2059    2840    1894    3778    7539    6631
River Rch & RM= Stream0799,Reach-1,21302
    1431    2408    3326    2218    4425    8829    7769
River Rch & RM= Stream0799,Reach-1,15056
    1672    2829    3919    2620    5228   10432    9230
River Rch & RM= Stream0799,Reach-1,9631
    1807    3052    4226    2821    5628   11230    9906
Boundary for River Rch & Prof#=Stream0799,Reach-1,1
Up Type=0
Dn Type=3
Dn Slope=0.005
Boundary for River Rch & Prof#=Stream0799,Reach-1,2
Up Type=0
Dn Type=3
Dn Slope=0.005
Boundary for River Rch & Prof#=Stream0799,Reach-1,3
Up Type=0
Dn Type=3
Dn Slope=0.005
Boundary for River Rch & Prof#=Stream0799,Reach-1,4
Up Type=0
Dn Type=3
Dn Slope=0.005
Boundary for River Rch & Prof#=Stream0799,Reach-1,5
Up Type=0
Dn Type=3
Dn Slope=0.005
Boundary for River Rch & Prof#=Stream0799,Reach-1,6
Up Type=0
Dn Type=3
Dn Slope=0.005
Boundary for River Rch & Prof#=Stream0799,Reach-1,7
Up Type=0
Dn Type=3
Dn Slope=0.005

--- Stream0799.g01 (geometry) ---

Geom Title=Existing Conditions
Program Version=4.10

River Reach=Stream0799      ,Reach-1
Reach XY= 30
        2420375.       13594125.      2420895.18     13594575.43
      2422135.55      13594026.1      2423664.56     13594076.06
       2425026.5     13594821.53      2426500.12     13595225.52
      2427185.28     13594675.99      2428054.82     13594875.29
       2428564.3      13594575.7      2429504.97     13595024.94
      2430727.42     13594519.46      2431126.46     13594078.53
      2431581.67     13594266.04      2432826.71      13593428.3
      2433231.34     13593466.98      2433914.58     13592784.81
       2433924.4     13591885.62      2433626.97     13591380.65
      2434615.19     13590485.51      2435159.78     13590325.51
      2436023.44     13590621.26      2436315.17     13590035.47
      2437214.24     13589734.68      2437464.82     13588635.31
      2438448.86     13588701.94      2438577.24     13587330.93
       2439023.8      13586814.5      2438880.45     13586122.53
       2439672.7     13585330.09        2440625.       13585175.

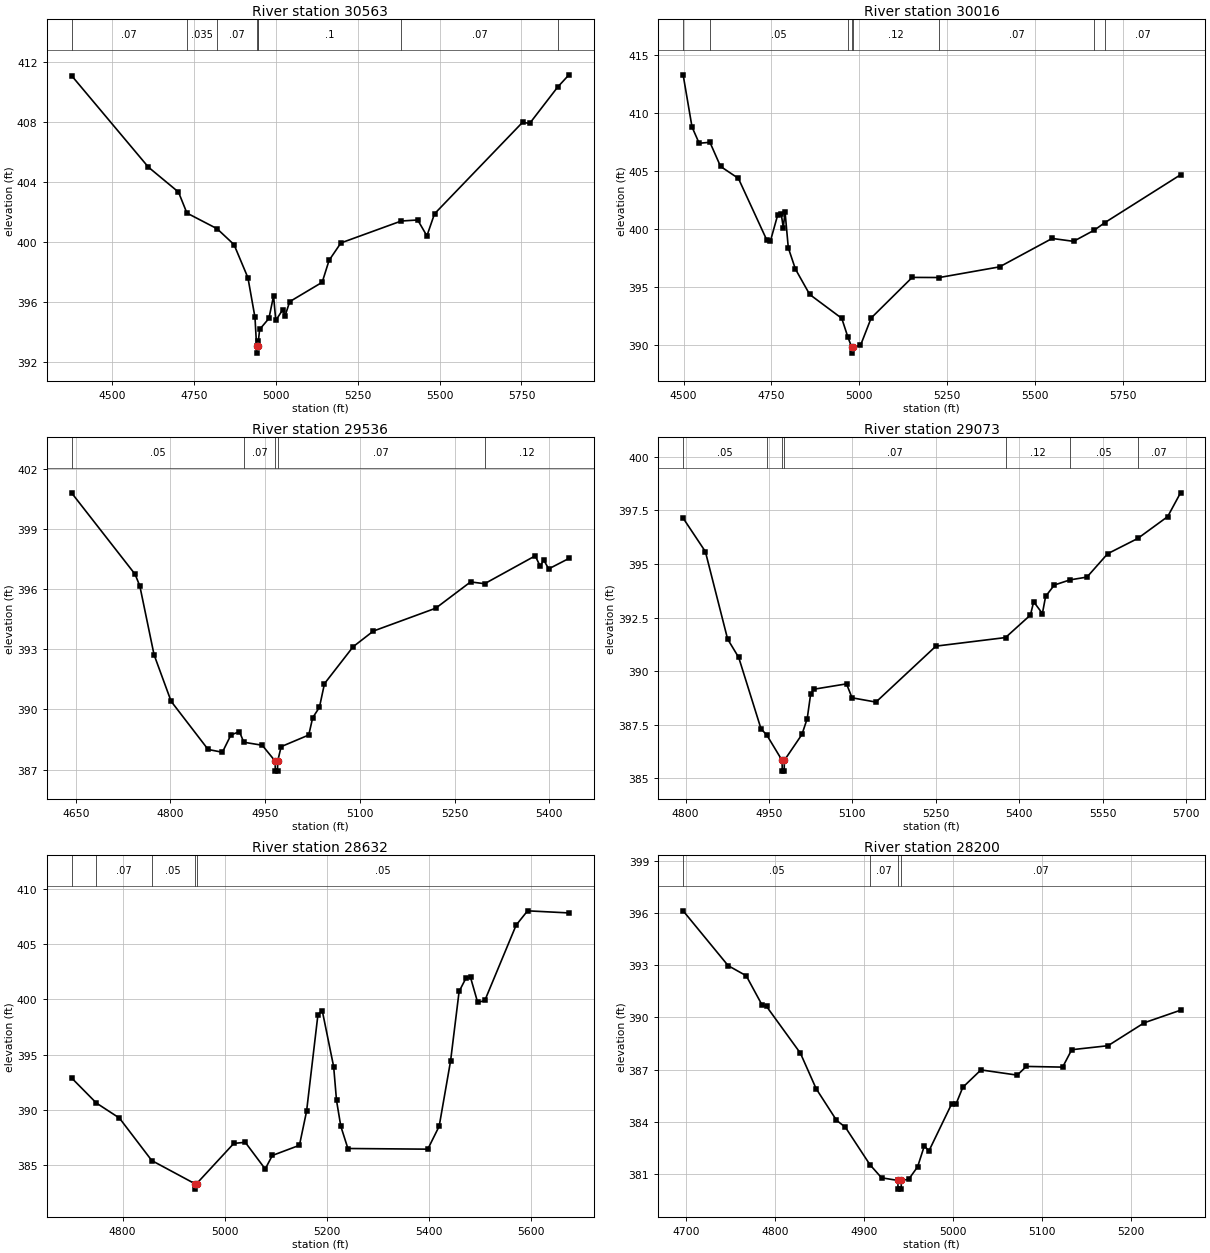
Type RM Length L Ch R = 1 ,30563   ,547,547,547
BEGIN DESCRIPTION:
Stream0799 64.0
END DESCRIPTION:
XS GIS Cut Line= 3
       2419996.8      13594628.2      2420534.35     13594049.64
      2420903.35     13593420.98
#Sta/Elev= 30
  4376.3  411.09    4611  404.99  4702.8  403.33  4728.6  401.93  4820.5  400.89
  4872.4  399.83  4914.9  397.62  4936.4  394.98  4941.2   393.1  4941.5   392.6
  4945.2   393.1  4946.6  393.38  4950.6  394.18  4978.9  394.91  4993.1  396.41
  4999.9  394.78  5021.4   395.5  5028.2  395.08  5042.4  396.03  5141.6  397.32
  5162.6  398.78  5198.7  399.94  5382.8   401.4  5433.2  401.47  5461.3  400.41
  5484.5  401.88  5753.5  407.98    5775   407.9  5860.4  410.32    5895  411.14
#Mann= 8 ,-1 , 0
  4376.3     .07       0  4728.6    .035       0  4820.5     .07       0
  4941.2     .05       0  4945.2     .07       0  4946.6      .1       0
  5382.8     .07       0  5860.4     .12       0
Bank Sta=4941.2,4945.2
XS Rating Curve= 0 ,0
Exp/Cntr=0.3,0.1

Type RM Length L Ch R = 1 ,30016   ,480,480,480
BEGIN DESCRIPTION:
Stream0799 63.0
END DESCRIPTION:
XS GIS Cut Line= 3
      2420643.69     13595070.01        2420725.       13594575.
      2420875.01     13593674.96
#Sta/Elev= 30
  4498.8  413.31  4524.1  408.81  4544.4  407.41    4575  407.49  4605.2  405.41
  4655.9  404.38    4737  399.04  4747.1  398.99  4767.4   401.2  4777.5  401.35
  4783.5  400.14  4788.6  401.47  4797.8  398.39    4818  396.56  4858.6  394.37
  4949.8  392.31  4967.2  390.69  4978.2  389.81  4978.4  389.31  4982.2  389.81
    5003  389.97  5033.4  392.34    5150  395.84  5227.1  395.83  5398.4  396.75
  5547.9   399.2  5608.7  398.95  5667.9  399.92    5698  400.57  5912.9  404.69
#Mann= 8 ,-1 , 0
  4498.8    .035       0    4575     .05       0  4967.2     .12       0
  4978.2     .05       0  4982.2     .12       0  5227.1     .07       0
  5667.9     .12       0    5698     .07       0
Bank Sta=4978.2,4982.2
XS Rating Curve= 0 ,0
Exp/Cntr=0.3,0.1

Type RM Length L Ch R = 1 ,29536   ,463,463,463
BEGIN DESCRIPTION:
Stream0799 62.0
END DESCRIPTION:
XS GIS Cut Line= 3
        2421325.       13594675.        2421125.       13594375.
      2420974.98     13593974.96
#Sta/Elev= 30
  4643.4  400.79  4744.1  396.73  4751.6  396.14  4774.1  392.72  4801.1   390.4
  4859.7     388  4882.3  387.86  4895.8  388.72  4909.3  388.89  4916.2  388.36
  4945.4  388.21  4965.9  387.42  4966.1  386.92  4969.6  386.92  4969.9  387.42
  4975.4  388.14  5019.1  388.72  5025.3  389.58    5036   390.1    5044  391.28
  5089.4  393.12  5121.4   393.9  5220.2  395.04  5275.4  396.35  5297.6  396.26
  5377.8  397.65  5385.8  397.12  5391.1  397.45  5399.1     397  5431.2  397.52
#Mann= 5 ,-1 , 0
  4643.4     .05       0  4916.2     .07       0  4965.9     .05       0
  4969.9     .07       0  5297.6     .12       0
Bank Sta=4965.9,4969.9
XS Rating Curve= 0 ,0
Exp/Cntr=0.3,0.1

Type RM Length L Ch R = 1 ,29073   ,441,441,441
BEGIN DESCRIPTION:
Stream0799 61.0
END DESCRIPTION:
XS GIS Cut Line= 3
        2421575.     13594525.04        2421575.       13594325.
      2421224.98     13593724.96
#Sta/Elev= 30
  4795.6  397.14  4835.6  395.58  4875.6   391.5  4895.6  390.64  4935.6  387.32
  4946.4  387.01  4973.6  385.84  4973.9  385.34  4977.4  385.34  4977.6  385.84
  5009.3  387.05  5018.8  387.79    5025  388.94  5030.8  389.16  5089.5  389.41
  5099.4  388.76  5142.4  388.56  5250.3  391.17  5375.5  391.57  5420.3  392.62
  5426.1  393.24  5441.8  392.69  5447.6  393.49  5463.3  394.02  5491.5  394.26
    5522  394.39  5559.2  395.48  5613.2  396.19  5667.1  397.21  5690.3  398.32
#Mann= 7 ,-1 , 0
  4795.6     .05       0  4946.4     .07       0  4973.6     .05       0
  4977.6     .07       0  5375.5     .12       0  5491.5     .05       0
  5613.2     .07       0
Bank Sta=4973.6,4977.6
XS Rating Curve= 0 ,0
Exp/Cntr=0.3,0.1

Type RM Length L Ch R = 1 ,28632   ,432,432,432
BEGIN DESCRIPTION:
Stream0799 60.0
END DESCRIPTION:
XS GIS Cut Line= 3
        2421975.     13594375.01        2421925.       13594075.
      2421624.98     13593474.97
#Sta/Elev= 30
  4700.1   392.9  4748.7  390.63  4793.9  389.27  4857.4  385.43  4941.4  383.35
  4941.7  382.85  4945.4  383.35  5018.2  386.98  5040.6  387.08  5079.7  384.67
  5093.7  385.89  5146.8  386.81  5160.8  389.88  5183.1  398.62  5191.5  398.98
  5213.9  393.91  5219.5  390.86  5227.9  388.53  5241.8  386.52  5398.4  386.46
  5420.7  388.53  5443.1  394.44  5459.8  400.71  5473.8  401.96  5482.2  401.97
  5496.2  399.71  5510.2  399.89  5571.6   406.7    5594  407.99  5675.1   407.8
#Mann= 5 ,-1 , 0
  4700.1     .05       0  4748.7     .07       0  4857.4     .05       0
  4941.4     .05       0  4945.4     .05       0
Bank Sta=4941.4,4945.4
XS Rating Curve= 0 ,0
Exp/Cntr=0.3,0.1

Type RM Length L Ch R = 1 ,28200   ,456,456,456
BEGIN DESCRIPTION:
Stream0799 59.0
END DESCRIPTION:
XS GIS Cut Line= 3
      2422374.99     13594374.96        2422325.       13594075.
      2422275.01     13593825.05
#Sta/Elev= 30
  4696.3  396.12  4746.9  392.97  4767.2  392.39    4785  390.71    4790  390.63
  4828.1  387.94  4845.8   385.9  4868.6  384.09  4878.7  383.68  4906.3  381.53
  4919.3  380.78  4937.6  380.63  4937.8  380.13  4941.3  380.13  4941.6  380.63
  4949.7  380.69  4959.8  381.41  4967.4  382.62  4972.5  382.32  4997.9  385.01
  5002.9  385.01  5010.6  385.98    5031  386.98  5071.8  386.68    5082  387.18
  5122.8  387.14    5133  388.14  5173.8  388.37  5214.6  389.69  5255.3  390.41
#Mann= 4 ,-1 , 0
  4696.3     .05       0  4906.3     .07       0  4937.6     .05       0
  4941.6     .07       0
Bank Sta=4937.6,4941.6
XS Rating Curve= 0 ,0
Exp/Cntr=0.3,0.1

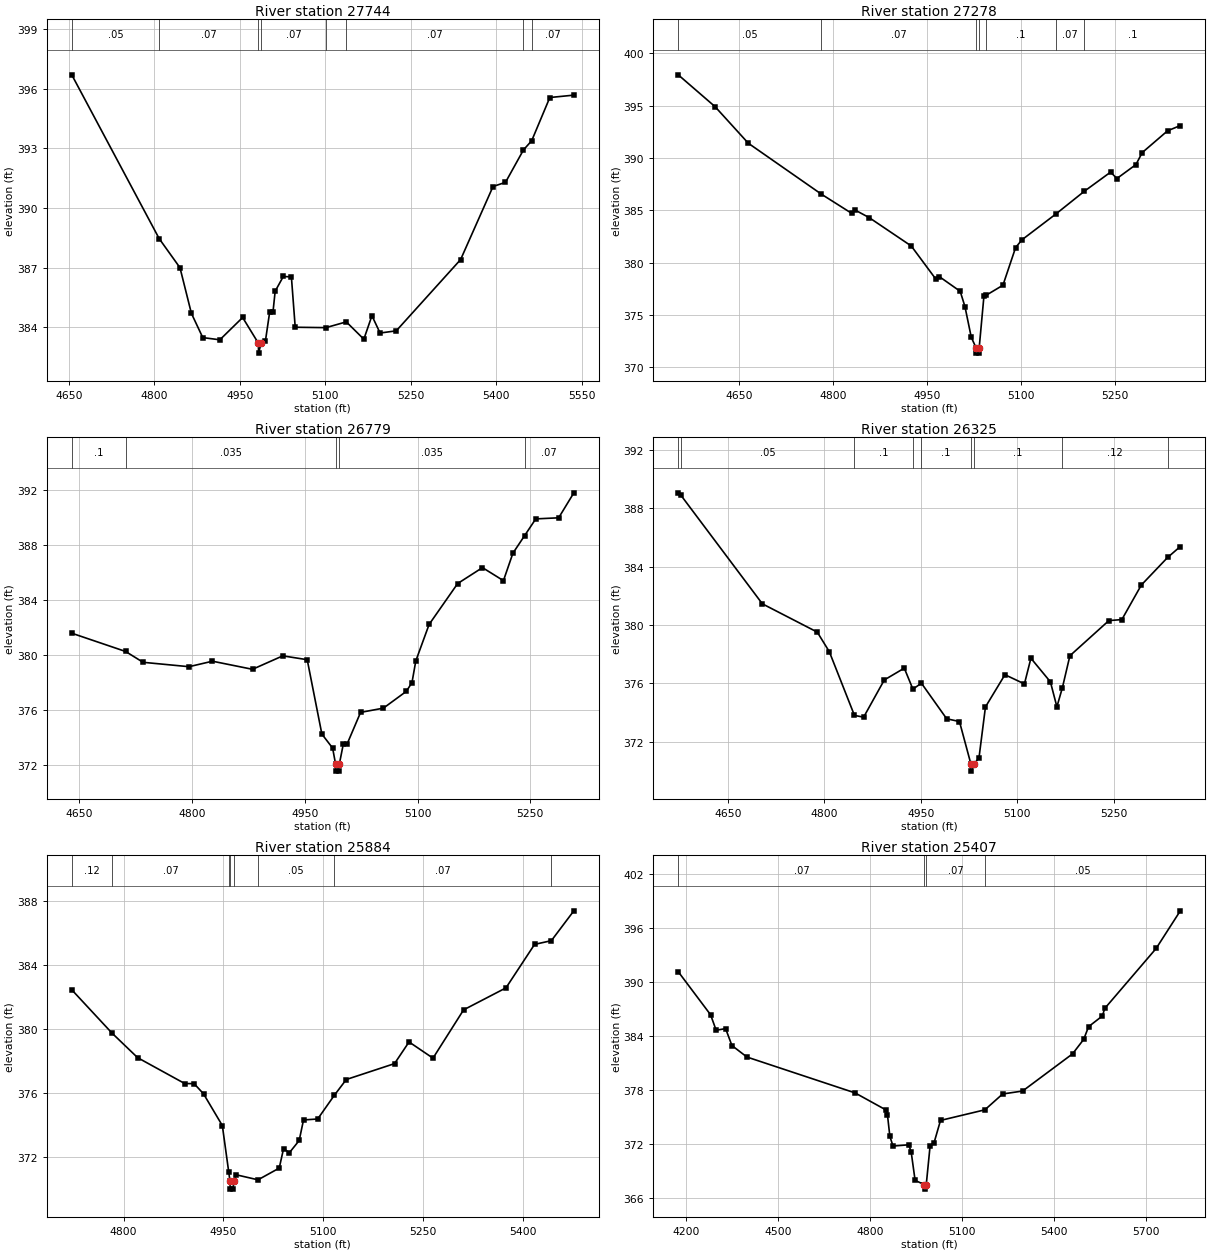
Type RM Length L Ch R = 1 ,27744   ,466,466,466
BEGIN DESCRIPTION:
Stream0799 58.0
END DESCRIPTION:
XS GIS Cut Line= 3
        2422725.     13594375.02        2422725.       13594025.
      2423074.98     13593625.02
#Sta/Elev= 30
  4654.9  396.69  4808.4  388.46  4844.9     387  4864.9  384.71  4884.9  383.49
  4914.9  383.38  4954.9   384.5  4982.5  383.21  4982.9  382.71  4987.3  383.21
  4994.9  383.32  5002.4  384.78  5008.2  384.78    5012  385.82  5026.3  386.56
  5040.5  386.54  5047.2  384.01  5101.1  383.99  5136.9  384.28  5167.7  383.41
  5181.9  384.59  5196.2  383.72  5224.6  383.83  5337.6  387.41  5394.5  391.08
  5416.4  391.29    5448  392.92  5462.4  393.38  5494.2  395.55  5536.4  395.67
#Mann= 8 ,-1 , 0
  4654.9     .05       0  4808.4     .07       0  4982.5     .05       0
  4987.3     .07       0  5101.1      .1       0  5136.9     .07       0
    5448      .1       0  5462.4     .07       0
Bank Sta=4982.5,4987.3
XS Rating Curve= 0 ,0
Exp/Cntr=0.3,0.1

Type RM Length L Ch R = 1 ,27278   ,499,499,499
BEGIN DESCRIPTION:
Stream0799 57.0
END DESCRIPTION:
XS GIS Cut Line= 3
      2422975.01     13594474.98        2423175.       13594075.
      2423225.01     13593724.95
#Sta/Elev= 30
  4552.8  397.96  4611.5  394.92  4664.6  391.42  4781.2  386.55  4829.5  384.72
  4835.1  385.03  4857.4  384.31  4924.5   381.6  4963.7  378.43  4969.3  378.67
  5002.5  377.27  5010.1  375.81  5020.2  372.87  5027.9  371.86  5028.2  371.36
  5032.4  371.36  5032.8  371.86  5040.4  376.82  5043.3  376.87  5070.7  377.85
  5090.9  381.45    5101  382.19  5155.4  384.67  5200.5  386.83  5242.4  388.66
  5252.5  388.05  5282.8  389.38  5292.9  390.53  5333.3  392.61  5353.6  393.11
#Mann= 7 ,-1 , 0
  4552.8     .05       0  4781.2     .07       0  5027.9     .05       0
  5032.8     .07       0  5043.3      .1       0  5155.4     .07       0
  5200.5      .1       0
Bank Sta=5027.9,5032.8
XS Rating Curve= 0 ,0
Exp/Cntr=0.3,0.1

Type RM Length L Ch R = 1 ,26779   ,454,454,454
BEGIN DESCRIPTION:
Stream0799 56.0
END DESCRIPTION:
XS GIS Cut Line= 3
        2423575.     13594424.99        2423675.       13594075.
      2423625.01     13593775.03
#Sta/Elev= 30
  4639.9  381.59  4711.5  380.26  4734.8  379.47  4795.9  379.15  4827.1  379.55
  4880.4  378.96  4920.7  379.94  4953.2  379.66  4972.7  374.24    4987  373.22
    4991  372.04  4991.4  371.54  4995.6  371.54  4995.9  372.04  5001.3  373.53
  5006.4  373.53  5024.2  375.82  5054.6  376.13    5085  377.35  5092.6  377.99
  5097.7  379.57  5115.4  382.23  5153.4  385.21  5186.4  386.37  5214.3  385.42
  5226.9  387.42  5242.6  388.71  5257.3  389.92  5287.8     390    5308  391.82
#Mann= 5 ,-1 , 0
  4639.9      .1       0  4711.5    .035       0    4991    .035       0
  4995.9    .035       0  5242.6     .07       0
Bank Sta=4991,4995.9
XS Rating Curve= 0 ,0
Exp/Cntr=0.3,0.1

Type RM Length L Ch R = 1 ,26325   ,441,441,441
BEGIN DESCRIPTION:
Stream0799 55.0
END DESCRIPTION:
XS GIS Cut Line= 3
      2423925.01     13594624.96        2424075.       13594225.
        2424025.     13593875.02
#Sta/Elev= 30
  4572.8  389.06  4577.2  388.88  4703.6  381.45    4789  379.51  4807.7  378.17
  4846.8   373.8  4861.1  373.68  4893.2  376.23  4924.3  377.04  4937.7   375.6
  4950.9  376.01  4990.2  373.57  5010.1  373.38  5027.8  370.48  5028.2  369.98
  5032.7  370.48  5040.4  370.87  5050.5  374.38  5080.8  376.59  5111.1  375.96
  5121.2  377.72  5151.5   376.1  5161.6  374.39  5170.2  375.71  5181.8  377.89
  5242.4   380.3  5262.6  380.37  5292.9  382.74  5333.8  384.63  5353.5  385.38
#Mann= 9 ,-1 , 0
  4572.8     .07       0  4577.2     .05       0  4846.8      .1       0
  4937.7     .05       0  4950.9      .1       0  5027.8     .05       0
  5032.7      .1       0  5170.2     .12       0  5333.8     .07       0
Bank Sta=5027.8,5032.7
XS Rating Curve= 0 ,0
Exp/Cntr=0.3,0.1

Type RM Length L Ch R = 1 ,25884   ,477,477,477
BEGIN DESCRIPTION:
Stream0799 54.0
END DESCRIPTION:
XS GIS Cut Line= 3
      2424174.97     13594675.03        2424375.       13594475.
      2424625.01     13594074.99
#Sta/Elev= 30
  4722.2  382.44  4782.7  379.74  4821.2  378.21  4891.9   376.6  4906.1  376.59
  4920.2  375.96  4948.5  373.98  4958.1  371.09    4960  370.52  4960.4  370.02
  4964.9  370.02  4965.3  370.52  4969.7  370.91  5002.1   370.6    5034  371.33
  5040.5  372.54  5049.3  372.29    5064  373.05  5070.5  374.33  5091.8  374.39
  5116.7  375.86  5134.8  376.85  5207.3  377.84  5229.1  379.19  5265.1  378.18
  5311.1  381.19  5374.8  382.56  5417.8  385.27    5443   385.5  5476.8  387.36
#Mann= 8 ,-1 , 0
  4722.2     .12       0  4782.7     .07       0  4958.1     .12       0
    4960     .05       0  4965.3     .12       0  5002.1     .05       0
  5116.7     .07       0    5443     .05       0
Bank Sta=4960,4965.3
XS Rating Curve= 0 ,0
Exp/Cntr=0.3,0.1

Type RM Length L Ch R = 1 ,25407   ,464,464,464
BEGIN DESCRIPTION:
Stream0799 53.0
END DESCRIPTION:
XS GIS Cut Line= 3
      2424575.01     13595474.96        2424775.       13594675.
        2424925.     13593875.02
#Sta/Elev= 30
  4175.1  391.16  4280.7  386.37  4298.8  384.65  4329.7  384.83  4350.3  382.95
  4399.3  381.67  4752.3  377.68  4852.8  375.79  4857.9  375.24  4865.7  372.85
    4876  371.77  4927.5  371.91  4935.3  371.11  4948.1  367.95  4978.7  367.48
  4979.2  366.98  4984.5  367.48  4997.1  371.82  5009.9  372.13    5031  374.62
  5175.8   375.8  5233.7  377.56    5299  377.89  5461.8  382.02  5498.2  383.63
  5514.3  385.05  5559.3  386.24  5566.9  387.07  5734.8  393.75  5813.6  397.93
#Mann= 4 ,-1 , 0
  4175.1     .07       0  4978.7     .05       0  4984.5     .07       0
  5175.8     .05       0
Bank Sta=4978.7,4984.5
XS Rating Curve= 0 ,0
Exp/Cntr=0.3,0.1

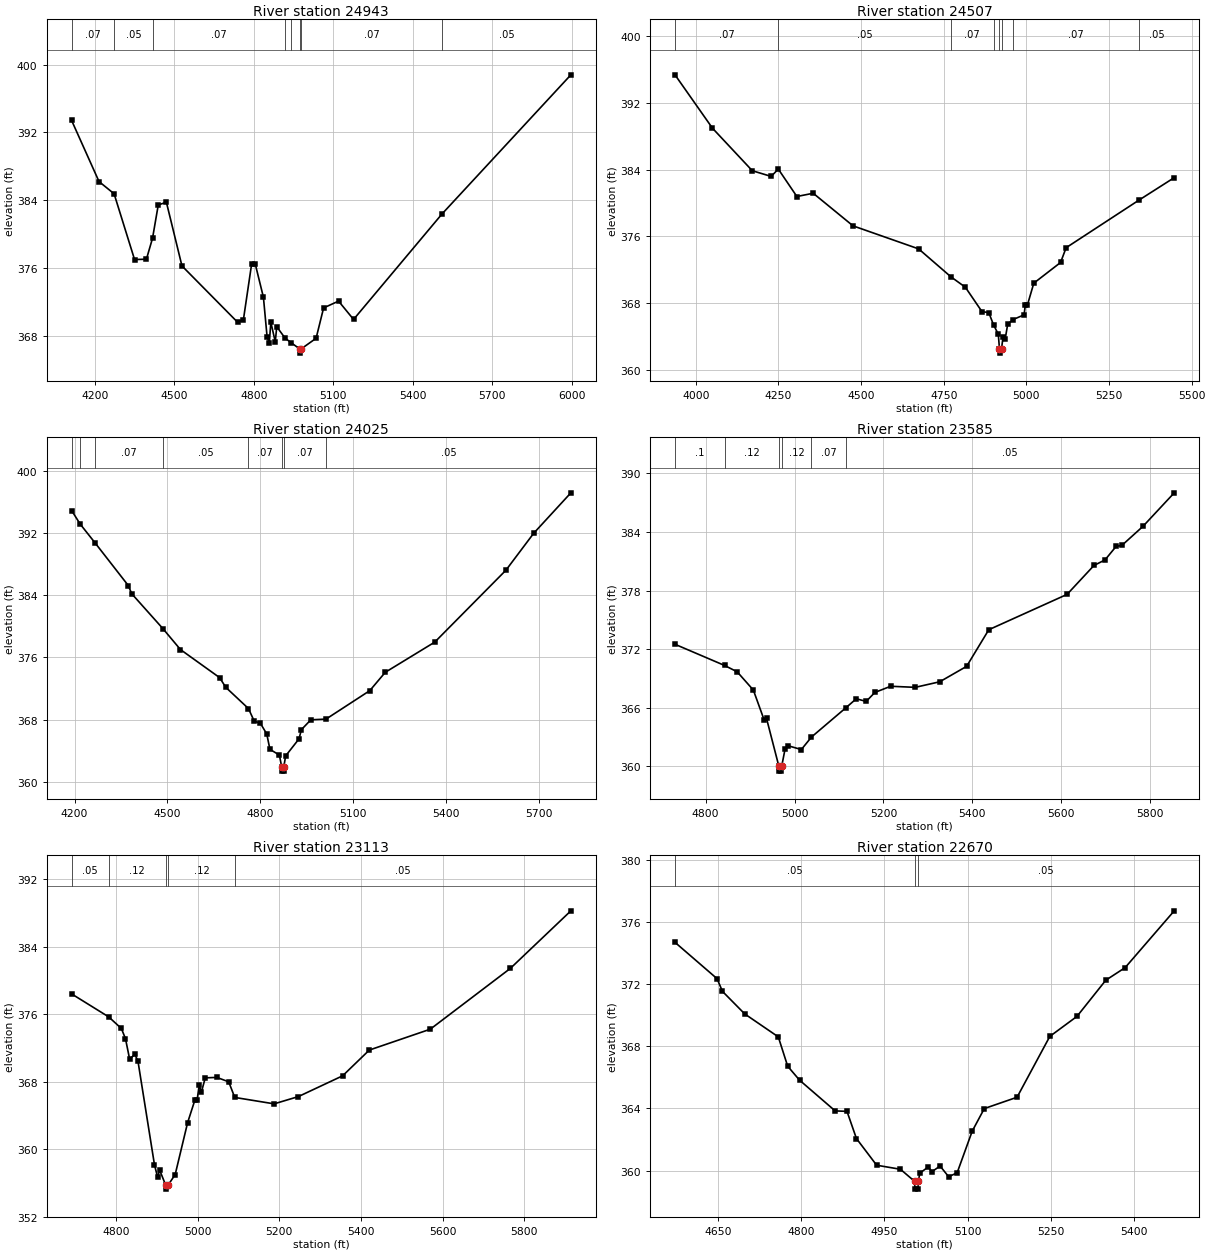
Type RM Length L Ch R = 1 ,24943   ,436,436,436
BEGIN DESCRIPTION:
Stream0799 52.0
END DESCRIPTION:
XS GIS Cut Line= 3
      2424775.01     13595574.97        2425175.       13594775.
      2425874.97     13594075.03
#Sta/Elev= 30
  4112.6  393.41    4216  386.21  4272.9  384.77  4350.1  377.02  4394.9  377.06
    4418  379.54  4439.6  383.46  4470.3  383.77    4529  376.27  4738.7  369.64
    4761  369.94  4791.8  376.46  4805.7  376.49  4836.5  372.57  4850.5  367.85
  4858.9  367.24  4864.4  369.64  4881.2  367.32  4886.8   369.1  4918.2  367.76
  4940.5  367.23  4973.3  366.49  4973.8  365.99  4979.1  366.49  5035.3  367.74
  5063.6  371.32  5120.1  372.12  5176.7  369.96  5510.2  382.38  5996.9  398.79
#Mann= 8 ,-1 , 0
  4112.6     .07       0  4272.9     .05       0    4418     .07       0
  4918.2    .035       0  4940.5     .07       0  4973.3     .05       0
  4979.1     .07       0  5510.2     .05       0
Bank Sta=4973.3,4979.1
XS Rating Curve= 0 ,0
Exp/Cntr=0.3,0.1

Type RM Length L Ch R = 1 ,24507   ,482,482,482
BEGIN DESCRIPTION:
Stream0799 51.0
END DESCRIPTION:
XS GIS Cut Line= 3
      2424875.01     13595674.99        2425575.       13594875.
        2425775.     13594475.01
#Sta/Elev= 30
  3937.1  395.38  4050.5  388.98    4171  383.88    4228   383.2  4249.6  384.08
  4305.8  380.79  4355.2  381.18  4475.7  377.27  4674.1  374.51  4771.8  371.16
  4815.5  369.91  4865.8  366.98  4886.2  366.88  4900.7   365.4  4915.1  364.28
  4918.7  362.51  4919.2  362.01  4924.8  362.51  4929.4  363.93    4936  363.72
  4943.6  365.49  4960.1  366.04    4993   366.6  4996.8  367.74  5002.9  367.74
  5022.5   370.4  5103.5  372.88  5120.3  374.65  5339.6  380.33  5447.3  383.05
#Mann= 8 ,-1 , 0
  3937.1     .07       0  4249.6     .05       0  4771.8     .07       0
  4900.7    .035       0  4918.7     .05       0  4924.8    .035       0
  4960.1     .07       0  5339.6     .05       0
Bank Sta=4918.7,4924.8
XS Rating Curve= 0 ,0
Exp/Cntr=0.3,0.1

Type RM Length L Ch R = 1 ,24025   ,440,440,440
BEGIN DESCRIPTION:
Stream0799 50.0
END DESCRIPTION:
XS GIS Cut Line= 3
        2425875.     13595774.99        2426025.       13594975.
        2426025.     13594175.03
#Sta/Elev= 30
  4190.4  394.93  4218.1  393.18  4266.8  390.73  4373.5  385.27  4384.5  384.22
  4485.6  379.71  4542.2  377.02  4668.6  373.41  4688.9  372.15    4762  369.42
  4780.5  367.81  4800.8  367.51  4821.2  366.14  4831.4  364.17  4861.9  363.43
  4869.8  361.86  4870.3  361.36  4875.6  361.36  4876.1  361.86  4882.2  363.32
  4925.5  365.52  4933.1   366.7  4963.6  367.97  5012.7  368.06  5154.3  371.73
  5204.3  374.09  5364.3  377.98  5594.3  387.24  5684.3  392.01  5804.3  397.21
#Mann= 8 ,-1 , 0
  4190.4     .07       0  4218.1     .05       0  4266.8     .07       0
  4485.6     .05       0    4762     .07       0  4869.8     .05       0
  4876.1     .07       0  5012.7     .05       0
Bank Sta=4869.8,4876.1
XS Rating Curve= 0 ,0
Exp/Cntr=0.3,0.1

Type RM Length L Ch R = 1 ,23585   ,472,472,472
BEGIN DESCRIPTION:
Stream0799 49.0
END DESCRIPTION:
XS GIS Cut Line= 3
      2426274.99     13595425.02        2426375.       13595175.
      2426074.99     13594374.98
#Sta/Elev= 30
  4730.9  372.51  4842.6  370.34  4870.9  369.69  4907.3  367.82  4931.5  364.77
  4936.9  364.92  4964.7  360.02  4965.2  359.52  4970.6  359.52  4971.1  360.02
  4978.6  361.77  4985.4  362.12  5015.3  361.73  5038.1  363.01  5115.1  365.99
    5139  366.93  5161.3  366.66  5180.8  367.58  5216.4  368.21  5271.6   368.1
  5326.8  368.67  5387.3  370.25  5437.2     374  5613.4  377.62  5673.9  380.58
  5698.8  381.15  5723.7  382.53  5737.1  382.65  5784.3  384.59  5854.6  388.02
#Mann= 6 ,-1 , 0
  4730.9      .1       0  4842.6     .12       0  4964.7     .05       0
  4971.1     .12       0  5038.1     .07       0  5115.1     .05       0
Bank Sta=4964.7,4971.1
XS Rating Curve= 0 ,0
Exp/Cntr=0.3,0.1

Type RM Length L Ch R = 1 ,23113   ,443,443,443
BEGIN DESCRIPTION:
Stream0799 48.0
END DESCRIPTION:
XS GIS Cut Line= 3
      2426825.01     13595425.04        2426775.       13595125.
      2426324.98     13594324.97
#Sta/Elev= 30
  4691.7   378.4  4782.4  375.68  4813.4  374.31  4823.5   373.1  4833.7  370.67
  4846.3  371.24    4854  370.46  4894.5  358.16  4902.1   356.7  4907.2  357.53
  4921.7  355.78  4922.2  355.28  4928.2  355.78  4945.2  357.01  4975.6  363.15
  4993.3  365.81  4998.8  365.81  5003.9  367.56  5009.6  366.81  5018.8  368.46
  5047.2  368.51  5076.2  367.99    5091  366.14  5187.4  365.38  5246.7  366.24
  5355.1   368.7  5420.4  371.75  5569.6  374.22  5765.6  381.42  5913.8  388.24
#Mann= 5 ,-1 , 0
  4691.7     .05       0  4782.4     .12       0  4921.7     .05       0
  4928.2     .12       0    5091     .05       0
Bank Sta=4921.7,4928.2
XS Rating Curve= 0 ,0
Exp/Cntr=0.3,0.1

Type RM Length L Ch R = 1 ,22670   ,435,435,435
BEGIN DESCRIPTION:
Stream0799 47.0
END DESCRIPTION:
XS GIS Cut Line= 3
      2427225.01     13595225.02        2427075.       13594825.
      2426825.01     13594425.02
#Sta/Elev= 30
    4573   374.7  4648.7  372.36  4658.5  371.54  4698.5  370.09    4759  368.61
  4775.9  366.72  4797.3  365.82  4861.4  363.84  4882.7  363.81  4899.7  362.06
  4936.1  360.34  4978.9  360.08  5004.5   359.3    5005   358.8  5010.7   358.8
  5011.2   359.3  5013.8  359.83  5029.1  360.23  5035.6  359.92  5050.3  360.29
  5065.7   359.6    5081  359.85  5108.1  362.53  5129.9  363.99  5188.9  364.72
  5247.9  368.64  5296.8  369.93  5348.7  372.26  5383.5  373.07  5471.9  376.73
#Mann= 3 ,-1 , 0
    4573     .05       0  5004.5     .05       0  5011.2     .05       0
Bank Sta=5004.5,5011.2
XS Rating Curve= 0 ,0
Exp/Cntr=0.3,0.1

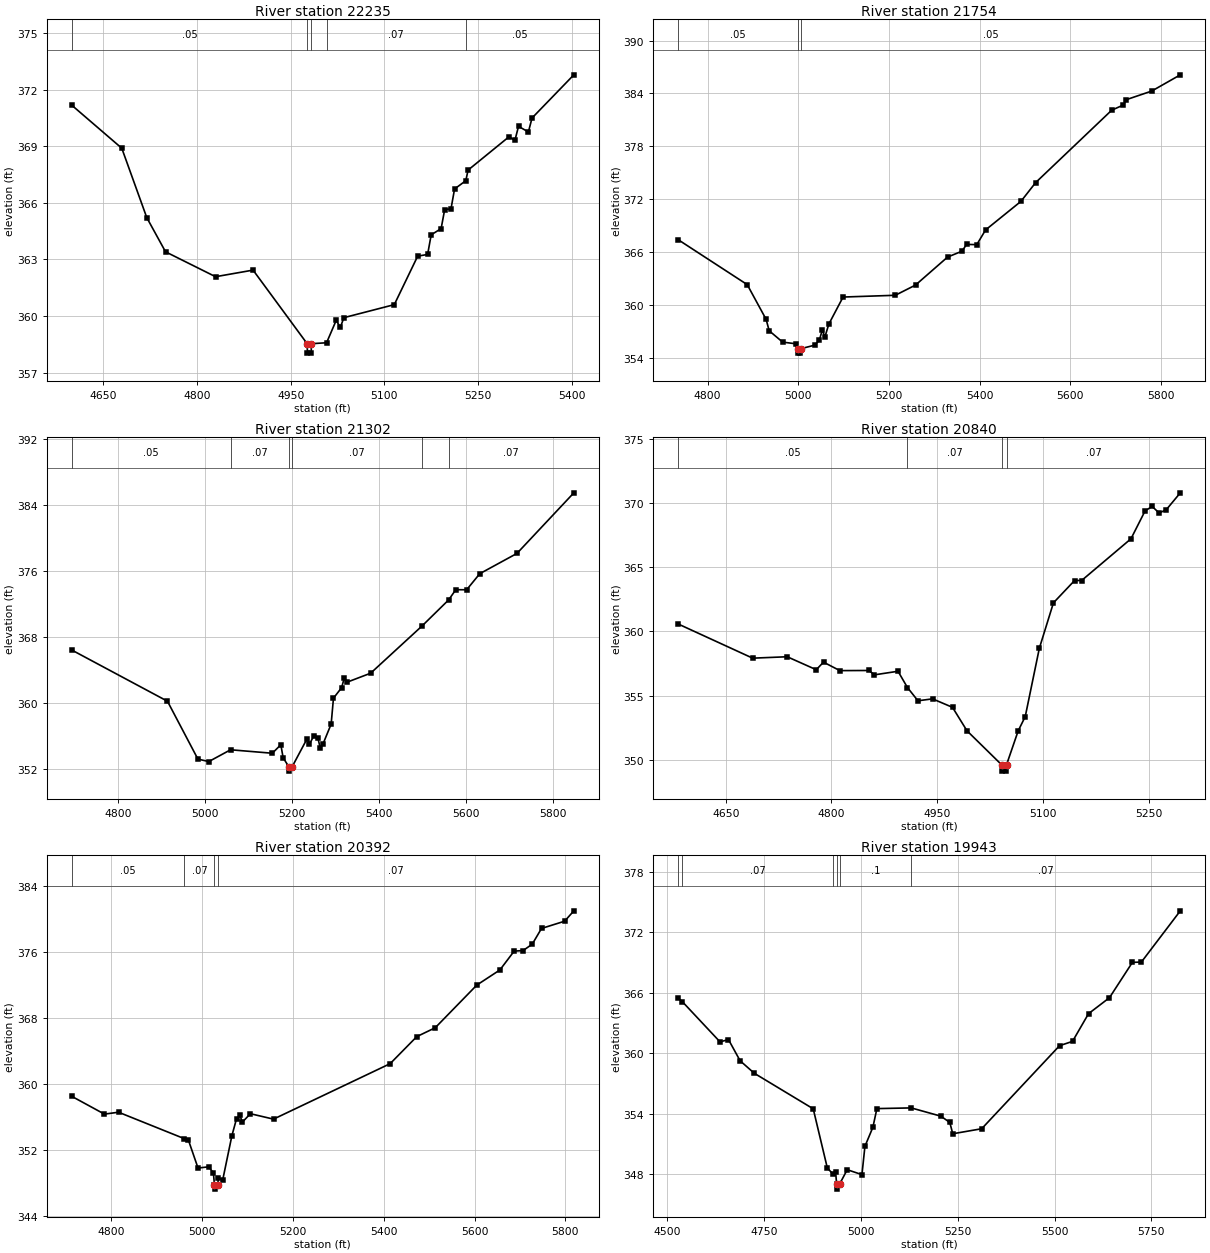
Type RM Length L Ch R = 1 ,22235   ,481,481,481
BEGIN DESCRIPTION:
Stream0799 46.0
END DESCRIPTION:
XS GIS Cut Line= 3
        2427425.       13595075.        2427425.       13594675.
        2427225.     13594325.01
#Sta/Elev= 30
  4599.9  371.17  4679.9  368.89  4719.9  365.21  4749.9   363.4  4829.9  362.08
  4889.9  362.43  4976.4  358.53  4976.9  358.03  4982.8  358.03  4983.3  358.53
  5007.5  358.58  5022.9  359.77  5029.4  359.39  5035.2  359.91  5115.8   360.6
  5153.2  363.17  5169.1  363.26  5174.8   364.3  5190.7  364.63  5196.4  365.64
  5206.5  365.68  5212.2  366.73  5230.2  367.17  5233.8  367.73  5299.4   369.5
  5308.7   369.3  5314.5  370.05  5330.3  369.75  5336.1  370.49    5403  372.78
#Mann= 5 ,-1 , 0
  4599.9     .05       0  4976.4     .05       0  4983.3     .05       0
  5007.5     .07       0  5230.2     .05       0
Bank Sta=4976.4,4983.3
XS Rating Curve= 0 ,0
Exp/Cntr=0.3,0.1

Type RM Length L Ch R = 1 ,21754   ,452,452,452
BEGIN DESCRIPTION:
Stream0799 45.0
END DESCRIPTION:
XS GIS Cut Line= 3
      2427774.98     13595025.04        2427875.       13594775.
      2427624.99     13593974.96
#Sta/Elev= 30
  4735.2  367.39  4887.4  362.29  4929.1  358.34  4935.8  357.05  4965.5  355.76
  4995.1  355.57  4998.4  355.01  4998.9  354.51  5004.8  354.51  5005.3  355.01
  5035.9  355.41  5046.4  355.97  5053.2  357.18  5058.5  356.31  5067.4  357.81
  5098.8  360.88    5214  361.08  5258.6  362.24  5329.3  365.42  5361.2  366.09
  5371.2  366.86  5393.7  366.83  5413.1   368.5  5491.2  371.75  5523.6  373.88
  5691.3   382.1  5716.9  382.69  5723.7   383.3  5779.8  384.28  5842.7  386.12
#Mann= 3 ,-1 , 0
  4735.2     .05       0  4998.4     .05       0  5005.3     .05       0
Bank Sta=4998.4,5005.3
XS Rating Curve= 0 ,0
Exp/Cntr=0.3,0.1

Type RM Length L Ch R = 1 ,21302   ,462,462,462
BEGIN DESCRIPTION:
Stream0799 44.0
END DESCRIPTION:
XS GIS Cut Line= 3
        2428275.     13595125.02        2428275.       13594825.
      2428574.99     13594025.02
#Sta/Elev= 30
  4694.4  366.39  4914.4  360.18  4984.4  353.16  5009.5  352.86  5059.5  354.29
  5155.5  353.87  5175.1   354.9  5180.4  353.32  5193.8   352.2  5194.3   351.7
  5200.8   352.2  5235.6  355.65  5240.9  354.97  5250.7  355.96  5260.5  355.66
  5265.9  354.48  5272.1     355  5290.8  357.41  5296.1  360.55  5314.8  361.82
    5321  363.01  5326.4  362.47  5381.6  363.58    5500  369.32  5560.9  372.47
  5577.4  373.71  5602.3   373.7  5632.5  375.65    5718  378.11  5848.8  385.46
#Mann= 6 ,-1 , 0
  4694.4     .05       0  5059.5     .07       0  5193.8     .05       0
  5200.8     .07       0    5500     .05       0  5560.9     .07       0
Bank Sta=5193.8,5200.8
XS Rating Curve= 0 ,0
Exp/Cntr=0.3,0.1

Type RM Length L Ch R = 1 ,20840   ,448,448,448
BEGIN DESCRIPTION:
Stream0799 43.0
END DESCRIPTION:
XS GIS Cut Line= 3
        2428525.     13595024.98        2428625.       13594625.
        2428625.     13594324.99
#Sta/Elev= 30
  4582.6  360.57  4688.2  357.91  4737.2  358.02  4778.4  357.01  4788.7   357.6
  4811.9  356.94  4853.2  356.95  4860.9  356.61  4894.4  356.89  4907.8  355.62
  4922.7  354.59  4943.4  354.74  4971.7  354.08  4992.3  352.25  5041.3  349.61
  5041.8  349.11  5047.9  349.11  5048.4  349.61  5064.9  352.25  5074.9  353.36
  5094.9  358.68  5114.9  362.22  5144.9  363.96  5154.9  363.96  5224.9  367.21
  5244.9  369.38  5254.9  369.73  5264.9  369.22  5274.9  369.47  5294.9  370.79
#Mann= 4 ,-1 , 0
  4582.6     .05       0  4907.8     .07       0  5041.3     .05       0
  5048.4     .07       0
Bank Sta=5041.3,5048.4
XS Rating Curve= 0 ,0
Exp/Cntr=0.3,0.1

Type RM Length L Ch R = 1 ,20392   ,449,449,449
BEGIN DESCRIPTION:
Stream0799 42.0
END DESCRIPTION:
XS GIS Cut Line= 3
      2428824.99     13595125.01        2428975.       13594875.
        2428825.       13594075.
#Sta/Elev= 30
  4713.1  358.49    4785  356.33  4816.1  356.56  4960.9  353.35  4969.7  353.21
  4991.1  349.78  5014.8  349.93    5025  349.17  5027.3  347.72  5027.8  347.22
  5034.5  347.72    5036  348.59  5045.4  348.32  5065.7  353.72  5075.9  355.77
  5083.5  356.17  5088.6  355.35  5106.4  356.38  5157.3  355.72  5414.2  362.46
  5472.7  365.74  5513.4  366.82  5604.9     372  5655.8  373.84  5687.2  376.13
  5706.7  376.19    5727  376.97  5747.4  378.88  5798.3  379.76  5818.6  381.02
#Mann= 4 ,-1 , 0
  4713.1     .05       0  4960.9     .07       0  5027.3     .05       0
  5034.5     .07       0
Bank Sta=5027.3,5034.5
XS Rating Curve= 0 ,0
Exp/Cntr=0.3,0.1

Type RM Length L Ch R = 1 ,19943   ,448,448,448
BEGIN DESCRIPTION:
Stream0799 41.0
END DESCRIPTION:
XS GIS Cut Line= 3
      2429625.01     13595425.02        2429375.       13595025.
      2429574.99     13594225.04
#Sta/Elev= 30
  4528.4  365.47  4538.6  365.13  4636.3  361.12  4658.1  361.35  4688.2  359.24
  4724.8     358  4876.9  354.47  4913.4  348.58  4926.8  348.04  4934.7  348.23
  4937.3  346.99  4937.8  346.49    4945  346.99  4964.7  348.42  5002.7  347.93
  5010.4  350.74    5031  352.64  5041.3  354.49  5129.9  354.56  5206.3  353.74
  5229.5  353.12  5237.2  351.99  5311.9  352.49  5512.9  360.74  5546.4  361.17
  5587.7  363.92  5641.8  365.51    5701  369.02  5724.2  369.05  5824.7  374.14
#Mann= 6 ,-1 , 0
  4528.4     .05       0  4538.6     .07       0  4926.8      .1       0
  4937.3     .05       0    4945      .1       0  5129.9     .07       0
Bank Sta=4937.3,4945
XS Rating Curve= 0 ,0
Exp/Cntr=0.3,0.1

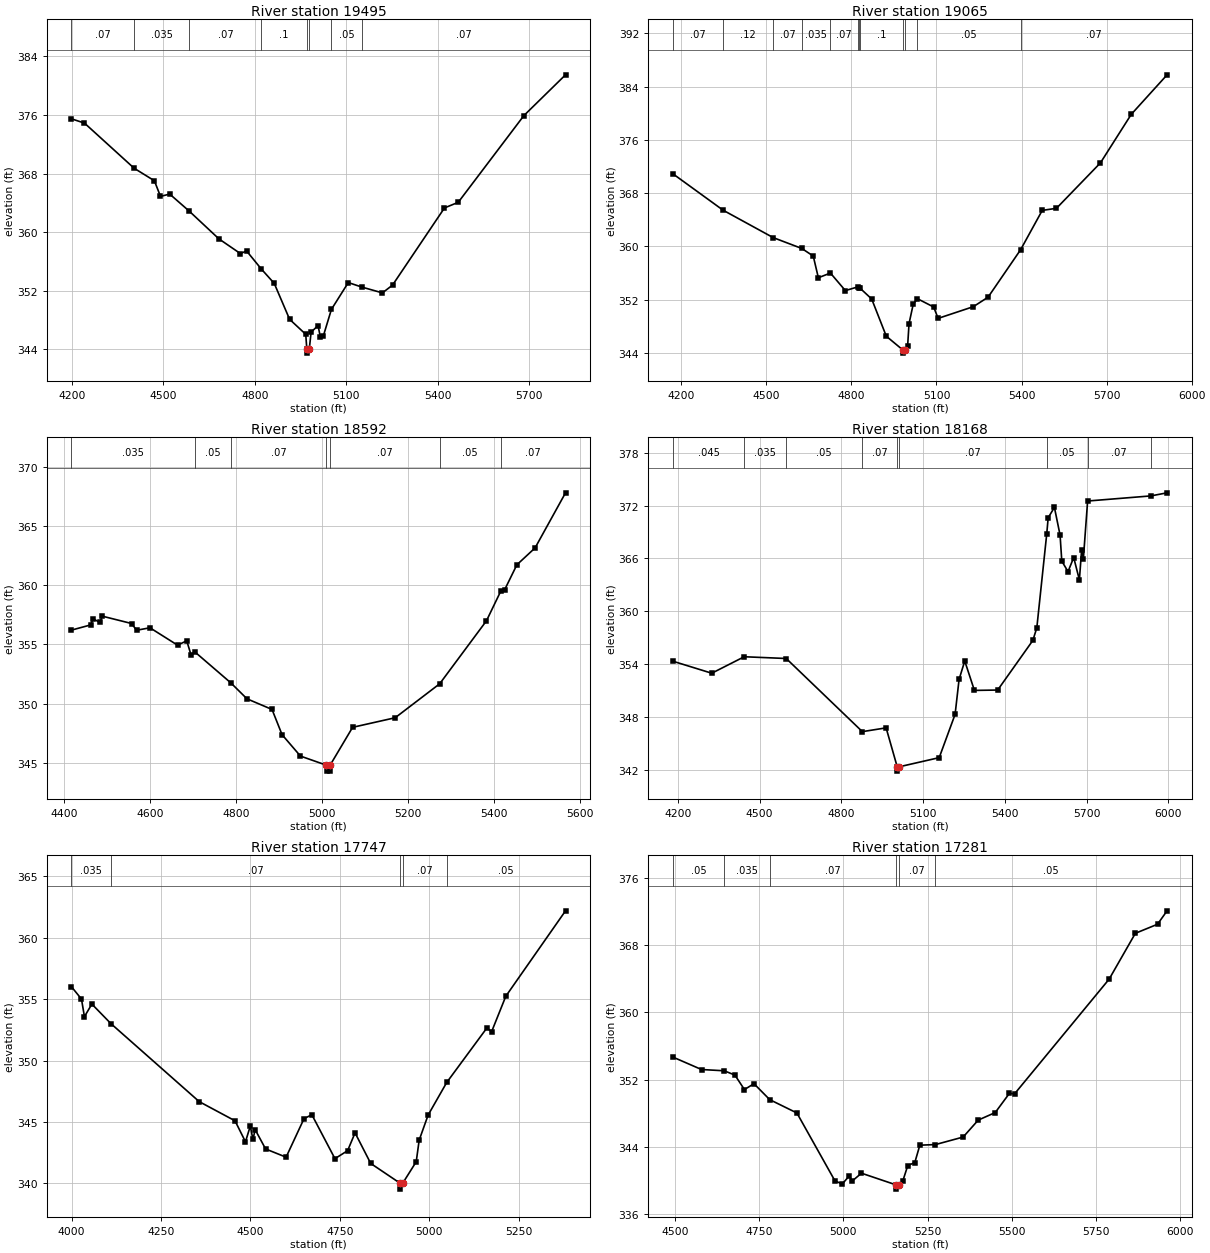
Type RM Length L Ch R = 1 ,19495   ,430,430,430
BEGIN DESCRIPTION:
Stream0799 40.0
END DESCRIPTION:
XS GIS Cut Line= 3
      2429874.99     13595674.95        2429775.       13594875.
        2429625.     13594075.02
#Sta/Elev= 30
  4198.2  375.48    4241   374.9  4403.9  368.73  4470.3  367.02  4490.4  364.88
  4520.6   365.2  4584.6  362.87  4681.9  359.08  4752.4  357.07  4772.6  357.43
  4821.4  354.94  4863.3     353  4913.7  348.09  4966.6  346.04  4970.2  343.97
  4970.7  343.47  4978.1  343.97  4984.2  346.34  5006.9  347.23  5014.6  345.67
  5024.7  345.87  5050.8  349.45  5106.1  353.11  5151.6  352.48    5218   351.7
  5251.1  352.76  5421.5  363.31  5466.5  364.07  5681.8  375.92  5818.3  381.49
#Mann= 8 ,-1 , 0
  4198.2     .07       0  4403.9    .035       0  4584.6     .07       0
  4821.4      .1       0  4970.2     .05       0  4978.1      .1       0
  5050.8     .05       0  5151.6     .07       0
Bank Sta=4970.2,4978.1
XS Rating Curve= 0 ,0
Exp/Cntr=0.3,0.1

Type RM Length L Ch R = 1 ,19065   ,473,473,473
BEGIN DESCRIPTION:
Stream0799 39.0
END DESCRIPTION:
XS GIS Cut Line= 3
      2429975.01     13595574.98        2430175.       13594775.
      2429724.99     13593974.98
#Sta/Elev= 30
  4170.8   370.9  4347.6  365.44  4524.4  361.32  4625.2  359.69  4665.6  358.55
  4683.6  355.29  4726.1     356  4778.9  353.36  4822.7  353.92  4826.9  353.82
  4830.2  353.74  4871.7   352.1  4923.2  346.51  4980.9  344.47  4981.4  343.97
  4989.3  344.47  4998.3  344.99  5003.4  348.41  5018.3  351.35  5033.2  352.14
  5090.1   350.9    5106  349.19  5230.3  350.95  5282.2  352.38  5396.8   359.5
  5473.1  365.41  5523.2  365.72  5678.4  372.55  5787.1  379.84  5913.3  385.77
#Mann= 12 ,-1 , 0
  4170.8     .07       0  4347.6     .12       0  4524.4     .07       0
  4625.2    .035       0  4726.1     .07       0  4822.7    .035       0
  4826.9     .07       0  4830.2      .1       0  4980.9     .05       0
  4989.3      .1       0  5033.2     .05       0  5396.8     .07       0
Bank Sta=4980.9,4989.3
XS Rating Curve= 0 ,0
Exp/Cntr=0.3,0.1

Type RM Length L Ch R = 1 ,18592   ,424,424,424
BEGIN DESCRIPTION:
Stream0799 38.0
END DESCRIPTION:
XS GIS Cut Line= 3
      2430875.01     13595075.01        2430575.       13594575.
        2430175.       13594175.
#Sta/Elev= 30
  4416.9  356.21  4461.6  356.65  4467.5  357.17    4483  356.86  4488.8  357.39
  4556.9  356.77  4568.5   356.2  4599.6  356.41  4663.8  354.94  4685.1  355.31
  4694.9  354.14  4705.3  354.33  4787.5  351.76  4825.1  350.41  4883.4  349.51
  4906.7  347.38  4949.5  345.57  5009.9   344.8  5010.4   344.3  5017.9   344.3
  5018.4   344.8  5070.7     348  5169.7  348.81  5273.2  351.68  5381.9     357
  5415.5  359.53  5424.3  359.63  5452.6  361.73    5495  363.16  5565.7  367.81
#Mann= 7 ,-1 , 0
  4416.9    .035       0  4705.3     .05       0  4787.5     .07       0
  5009.9     .05       0  5018.4     .07       0  5273.2     .05       0
  5415.5     .07       0
Bank Sta=5009.9,5018.4
XS Rating Curve= 0 ,0
Exp/Cntr=0.3,0.1

Type RM Length L Ch R = 1 ,18168   ,421,421,421
BEGIN DESCRIPTION:
Stream0799 37.0
END DESCRIPTION:
XS GIS Cut Line= 3
        2431075.     13595175.02        2430925.       13594375.
      2430124.97     13593774.97
#Sta/Elev= 30
  4181.7  354.34  4324.2  352.98  4443.4  354.85  4597.6  354.65  4877.1  346.35
  4964.3  346.78  5004.9  342.37  5005.4  341.87  5013.4  342.37  5159.2   343.4
  5217.5  348.31  5232.1  352.27  5252.9  354.37  5288.4  351.03  5373.8  351.07
  5502.9   356.7  5517.5  358.13    5554  368.81  5559.2  370.62  5582.1   371.8
  5602.9  368.65  5609.2   365.7  5632.1  364.51  5652.9  366.11  5673.8  363.57
  5682.1  367.01  5688.4  365.98    5704  372.52    5936   373.1  5995.7  373.45
#Mann= 9 ,-1 , 0
  4181.7    .045       0  4443.4    .035       0  4597.6     .05       0
  4877.1     .07       0  5004.9     .05       0  5013.4     .07       0
    5554     .05       0    5704     .07       0    5936     .05       0
Bank Sta=5004.9,5013.4
XS Rating Curve= 0 ,0
Exp/Cntr=0.3,0.1

Type RM Length L Ch R = 1 ,17747   ,466,466,466
BEGIN DESCRIPTION:
Stream0799 36.0
END DESCRIPTION:
XS GIS Cut Line= 3
      2431775.02     13594875.03        2431175.       13594075.
      2431025.01     13593725.02
#Sta/Elev= 30
  3999.5  356.02  4027.7  355.01    4036  353.58  4056.8   354.6    4110  353.01
  4356.8  346.66  4456.8   345.1    4486  343.39  4499.5  344.68  4506.8  343.58
  4513.1  344.38  4542.2  342.81  4599.5  342.14  4649.5  345.27  4671.4   345.6
    4736  342.02  4771.4  342.67  4792.2  344.12    4836  341.63  4917.1  340.04
  4917.6  339.54  4925.8  340.04  4963.1  341.77  4971.4  343.53  4996.4  345.57
  5048.3  348.22  5160.9  352.67  5173.6  352.34  5213.5  355.24  5380.3  362.19
#Mann= 5 ,-1 , 0
  3999.5    .035       0    4110     .07       0  4917.1     .05       0
  4925.8     .07       0  5048.3     .05       0
Bank Sta=4917.1,4925.8
XS Rating Curve= 0 ,0
Exp/Cntr=0.3,0.1

Type RM Length L Ch R = 1 ,17281   ,471,471,471
BEGIN DESCRIPTION:
Stream0799 35.0
END DESCRIPTION:
XS GIS Cut Line= 3
      2431924.99     13594624.99        2431575.       13594275.
      2431024.99     13593474.98
#Sta/Elev= 30
  4494.5  354.68  4579.3   353.2  4646.4  353.05  4678.3  352.54  4706.6  350.81
  4734.9  351.51  4781.6  349.61  4862.2  348.02  4975.3  339.91  4996.9  339.56
  5017.9  340.53  5025.9  339.89  5053.7  340.84  5156.9  339.44  5157.4  338.94
  5165.6  339.44  5176.2  339.89  5191.1  341.75    5212  342.11  5226.9  344.18
    5273  344.25  5355.4  345.15  5400.1  347.17  5450.6  348.07  5492.8  350.37
  5507.7  350.29  5788.5  363.98  5866.2  369.44  5931.9  370.52  5960.3  372.12
#Mann= 6 ,-1 , 0
  4494.5     .05       0  4646.4    .035       0  4781.6     .07       0
  5156.9     .05       0  5165.6     .07       0    5273     .05       0
Bank Sta=5156.9,5165.6
XS Rating Curve= 0 ,0
Exp/Cntr=0.3,0.1