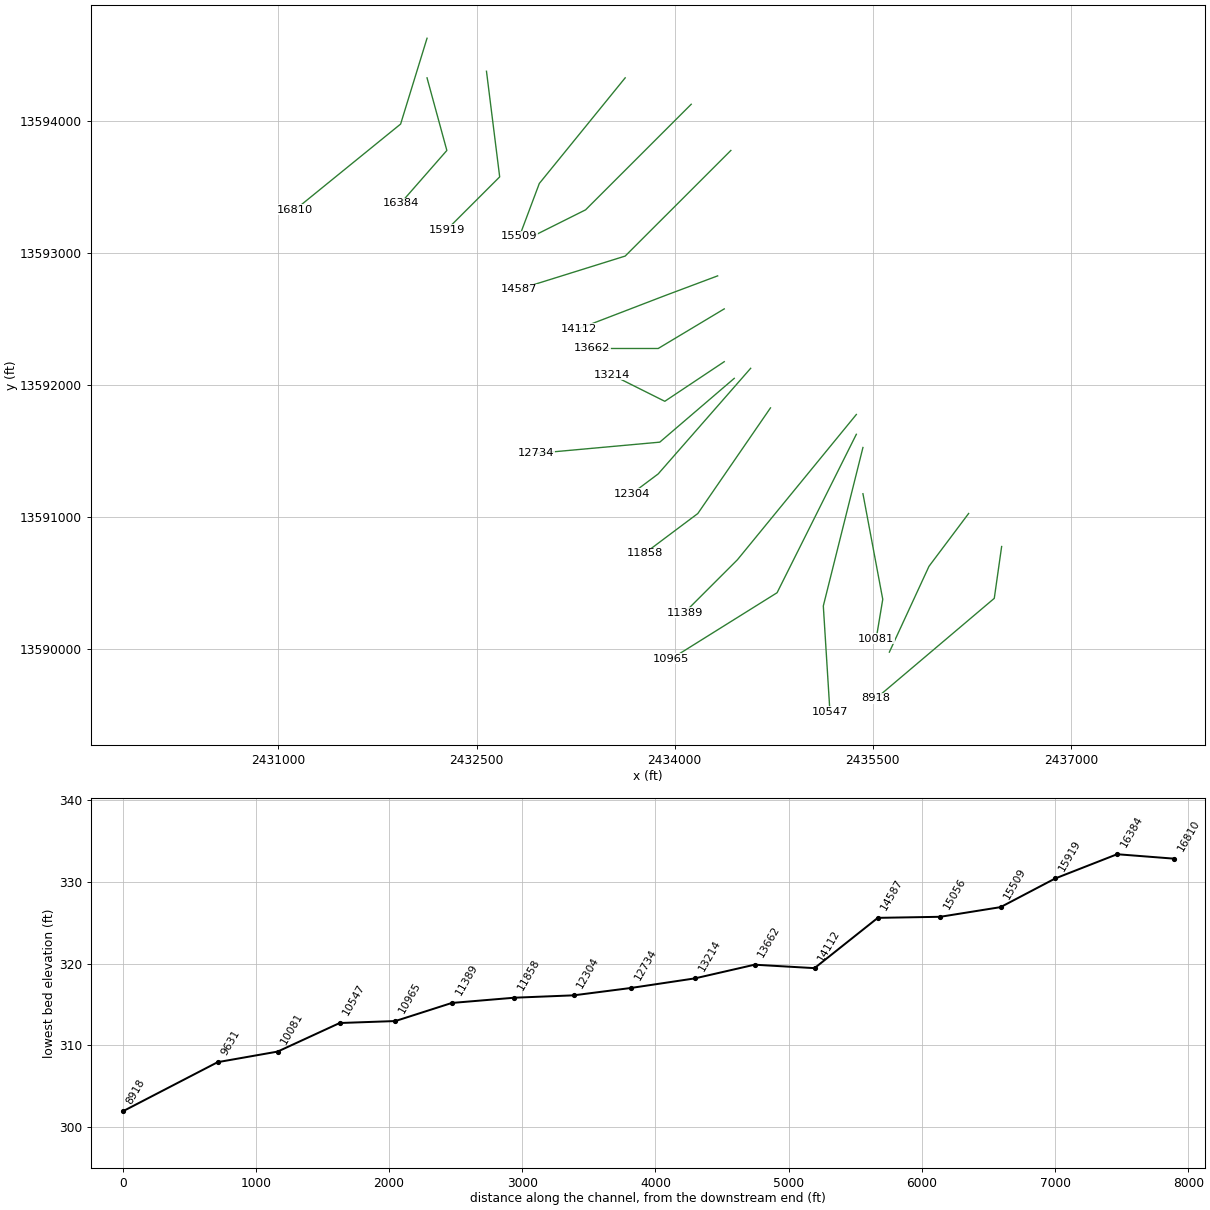
HEC-RAS study Stream0799.prj: Stream0799 Base Level Engineering

--- Stream0799.g01 (geometry) --- (continued)

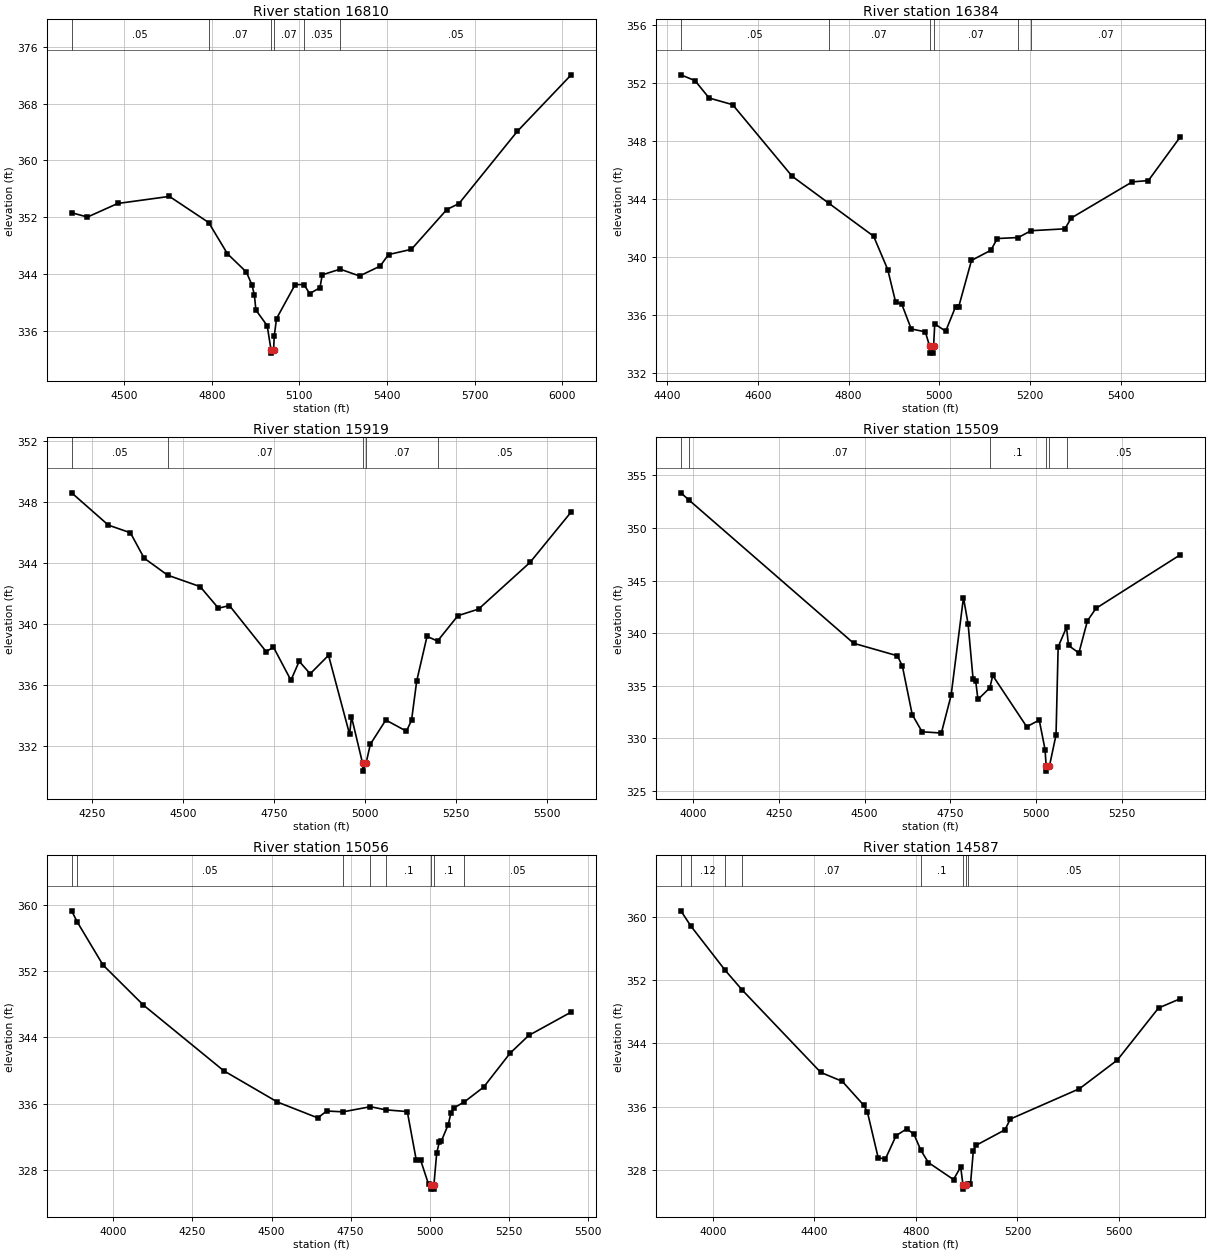
Type RM Length L Ch R = 1 ,16810   ,426,426,426
BEGIN DESCRIPTION:
Stream0799 34.0
END DESCRIPTION:
XS GIS Cut Line= 3
      2432124.99     13594624.98        2431925.       13593975.
      2431125.02     13593325.02
#Sta/Elev= 30
  4320.2  352.62  4374.5  352.02  4477.8  353.93    4655  354.93  4789.5  351.24
  4853.8  346.83  4918.5  344.26  4937.5  342.46    4946  341.04  4951.2  338.89
  4989.8  336.69  5002.9  333.31  5003.4  332.81  5011.9  333.31  5013.9  335.16
  5021.8  337.68  5085.7  342.49  5115.9  342.48  5135.3  341.22  5170.5  342.03
  5178.4  343.86  5239.8  344.66  5306.3   343.7  5376.6  345.09  5405.4  346.72
  5483.7  347.46  5605.1  353.08  5646.7  353.92  5846.4  364.11    6031  372.09
#Mann= 6 ,-1 , 0
  4320.2     .05       0  4789.5     .07       0  5002.9     .05       0
  5011.9     .07       0  5115.9    .035       0  5239.8     .05       0
Bank Sta=5002.9,5011.9
XS Rating Curve= 0 ,0
Exp/Cntr=0.3,0.1

Type RM Length L Ch R = 1 ,16384   ,465,465,465
BEGIN DESCRIPTION:
Stream0799 33.0
END DESCRIPTION:
XS GIS Cut Line= 3
      2432124.99     13594325.04        2432275.       13593775.
      2431925.02     13593375.02
#Sta/Elev= 30
  4430.2  352.56  4461.3  352.16  4492.4  350.96  4544.3   350.5  4675.5  345.56
  4756.2   343.7  4855.2  341.42  4886.3  339.12  4903.6  336.89  4917.4  336.72
  4938.1  335.02  4969.2  334.82  4978.5  333.85    4979  333.35    4987  333.35
  4987.5  333.85    4990  335.37  5014.1  334.86  5035.9  336.55  5042.6  336.52
    5071  339.75  5113.7  340.45    5128  341.26  5174.3  341.33  5202.3   341.8
    5277  341.93  5291.2  342.68  5425.5  345.17  5461.1  345.26  5531.8  348.29
#Mann= 6 ,-1 , 0
  4430.2     .05       0  4756.2     .07       0  4978.5     .05       0
  4987.5     .07       0  5174.3     .05       0  5202.3     .07       0
Bank Sta=4978.5,4987.5
XS Rating Curve= 0 ,0
Exp/Cntr=0.3,0.1

Type RM Length L Ch R = 1 ,15919   ,410,410,410
BEGIN DESCRIPTION:
Stream0799 32.0
END DESCRIPTION:
XS GIS Cut Line= 3
        2432575.     13594375.04        2432675.       13593575.
      2432275.03     13593175.03
#Sta/Elev= 30
  4194.4  348.58  4295.2  346.47  4355.7  345.97  4393.5  344.31  4457.9   343.2
  4547.2  342.45  4597.5  341.04  4627.8  341.21  4728.6   338.2  4748.7  338.49
  4796.6  336.33  4819.3  337.57  4849.5  336.75  4899.9  337.96  4957.8  332.79
  4962.9  333.94  4993.5  330.89    4994  330.39  5002.7  330.89  5014.8  332.15
  5057.2  333.73  5113.8     333  5127.9  333.72  5142.1  336.29  5170.4   339.2
  5199.2  338.89  5255.2  340.55  5311.8  340.98  5453.2  344.03  5566.3  347.33
#Mann= 5 ,-1 , 0
  4194.4     .05       0  4457.9     .07       0  4993.5     .05       0
  5002.7     .07       0  5199.2     .05       0
Bank Sta=4993.5,5002.7
XS Rating Curve= 0 ,0
Exp/Cntr=0.3,0.1

Type RM Length L Ch R = 1 ,15509   ,453,453,453
BEGIN DESCRIPTION:
Stream0799 31.0
END DESCRIPTION:
XS GIS Cut Line= 3
      2433625.02     13594325.03        2432975.       13593525.
        2432825.     13593125.01
#Sta/Elev= 30
  3963.6  353.34  3986.6  352.67  4467.9  339.04  4595.7  337.85  4610.1  336.86
  4638.8  332.26  4667.6  330.63  4723.8  330.51  4752.3   334.1  4788.3  343.38
  4801.9  340.86  4816.3  335.68  4824.2  335.41  4830.6   333.7  4865.4  334.81
  4873.7  335.98  4972.9  331.11  5009.5  331.74  5026.5  328.94  5029.6  327.39
  5030.1  326.89  5039.4  327.39  5058.5  330.33  5064.7   338.7  5089.1  340.56
    5095  338.83  5125.2  338.12  5150.2  341.18  5175.1  342.36  5421.6  347.46
#Mann= 6 ,-1 , 0
  3963.6     .05       0  3986.6     .07       0  4865.4      .1       0
  5029.6     .05       0  5039.4      .1       0  5089.1     .05       0
Bank Sta=5029.6,5039.4
XS Rating Curve= 0 ,0
Exp/Cntr=0.3,0.1

Type RM Length L Ch R = 1 ,15056   ,469,469,469
BEGIN DESCRIPTION:
Stream0799 30.0
END DESCRIPTION:
XS GIS Cut Line= 3
        2434125.       13594125.        2433325.       13593325.
      2432924.99     13593124.99
#Sta/Elev= 30
  3868.4  359.27  3885.9  357.94  3967.4  352.74  4094.7  347.92  4349.2  339.98
  4518.9  336.21  4646.2   334.3  4674.5  335.13  4726.1  335.03  4812.5  335.65
  4861.4  335.27  4929.1  335.06  4957.3  329.24  4971.5  329.17  4996.2   326.3
  5003.3  326.21  5003.8  325.71  5012.6  325.71  5013.1  326.21  5022.1   330.1
  5030.5   331.4  5036.1  331.46  5058.5   333.5  5066.9  334.87  5075.2  335.48
    5109  336.22  5170.3  338.01  5254.1  342.11  5312.8  344.24    5447  347.06
#Mann= 8 ,-1 , 0
  3868.4    .035       0  3885.9     .05       0  4726.1    .035       0
  4812.5     .05       0  4861.4      .1       0  5003.3     .05       0
  5013.1      .1       0    5109     .05       0
Bank Sta=5003.3,5013.1
XS Rating Curve= 0 ,0
Exp/Cntr=0.3,0.1

Type RM Length L Ch R = 1 ,14587   ,475,475,475
BEGIN DESCRIPTION:
Stream0799 29.0
END DESCRIPTION:
XS GIS Cut Line= 3
      2434424.99     13593774.99        2433625.       13592975.
        2432825.       13592725.
#Sta/Elev= 30
  3873.3  360.75  3912.5  358.83  4047.8  353.24  4115.7  350.72  4424.8  340.33
  4509.7   339.2  4594.5  336.17  4608.7  335.32  4651.1  329.55  4679.4  329.38
  4721.8  332.34  4764.2  333.21  4792.5  332.49  4819.5  330.48  4849.1  328.94
  4948.1  326.79  4976.4  328.38  4985.6  326.08  4986.1  325.58  4995.5  326.08
  5004.2  326.21  5015.1  326.22  5026.1  330.35  5036.1   331.1  5150.8  333.07
  5172.3  334.44  5444.7  338.27    5594  341.89  5756.4  348.47  5842.8  349.65
#Mann= 8 ,-1 , 0
  3873.3     .05       0  3912.5     .12       0  4047.8     .05       0
  4115.7     .07       0  4819.5      .1       0  4985.6     .05       0
  4995.5      .1       0  5004.2     .05       0
Bank Sta=4985.6,4995.5
XS Rating Curve= 0 ,0
Exp/Cntr=0.3,0.1

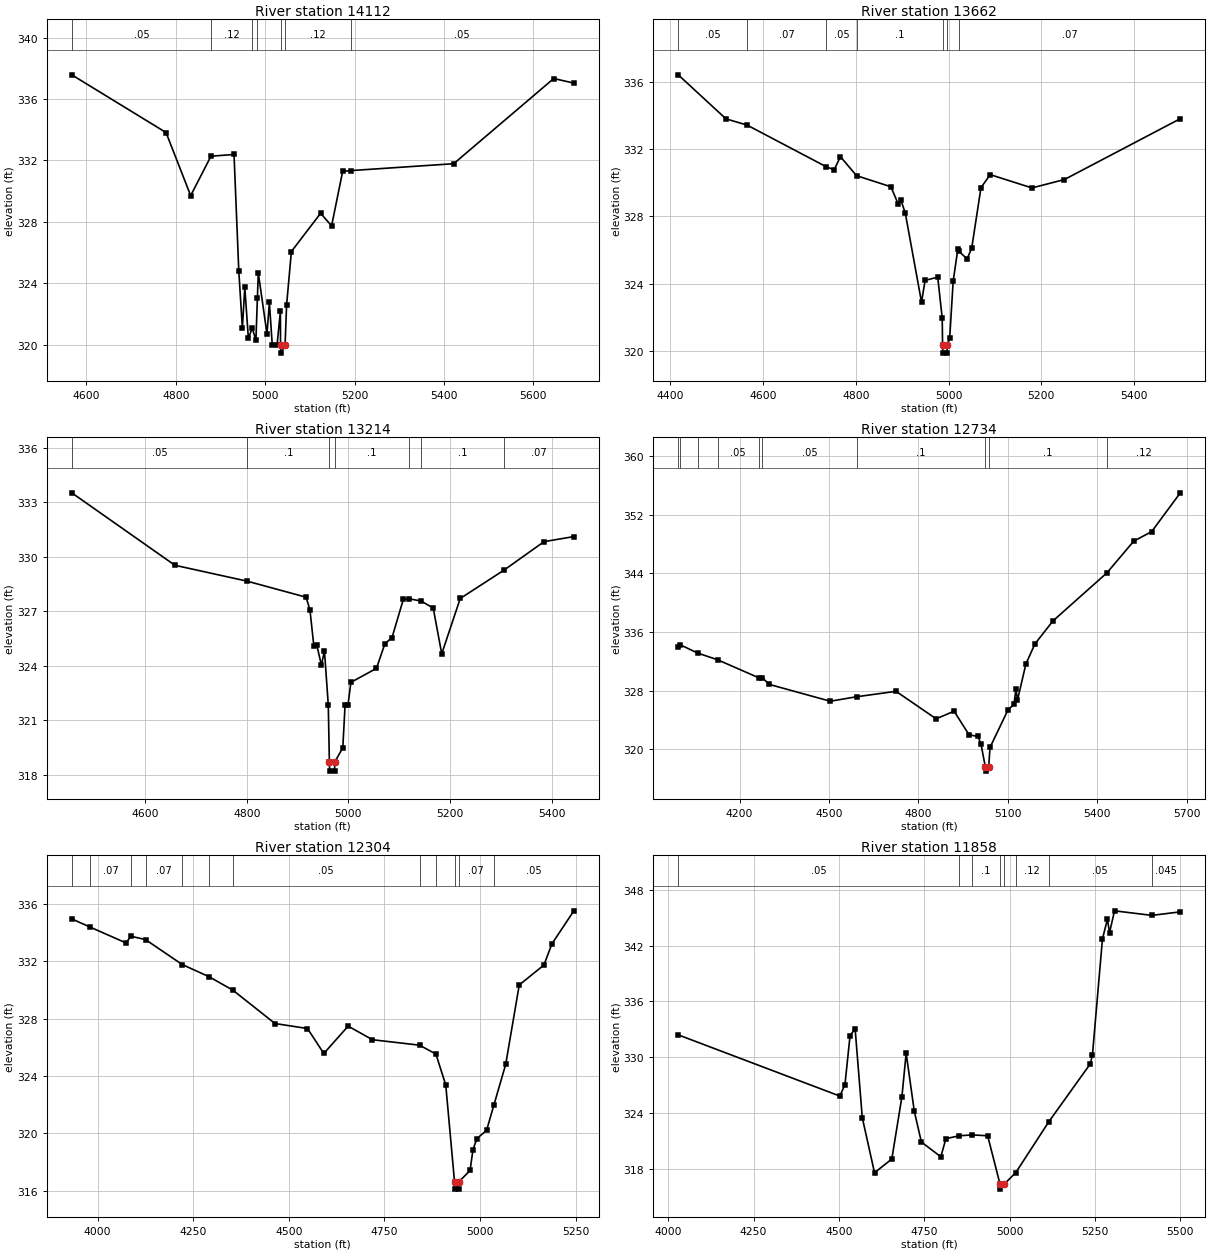
Type RM Length L Ch R = 1 ,14112   ,450,450,450
BEGIN DESCRIPTION:
Stream0799 28.0
END DESCRIPTION:
XS GIS Cut Line= 3
      2434325.02     13592825.01        2433925.       13592675.
      2433275.04     13592425.02
#Sta/Elev= 30
  4567.2  337.57  4778.2  333.81  4833.3   329.7  4878.7  332.27  4930.3  332.38
    4941  324.78    4949  321.08  4954.4  323.72  4962.4  320.42  4971.2  321.06
  4979.3  320.28  4982.6  323.01  4984.6  324.67  5004.1  320.69  5009.4  322.74
  5015.9  319.96  5026.6  319.95  5034.1  322.17  5034.4  319.94  5034.9  319.44
  5044.5  319.94    5048  322.59  5058.7  326.06  5124.1  328.55  5148.7  327.73
  5173.4  331.28  5191.1  331.33  5421.9  331.78  5645.8  337.33  5690.8  337.03
#Mann= 7 ,-1 , 0
  4567.2     .05       0  4878.7     .12       0  4971.2      .1       0
  4982.6     .12       0  5034.4     .05       0  5044.5     .12       0
  5191.1     .05       0
Bank Sta=5034.4,5044.5
XS Rating Curve= 0 ,0
Exp/Cntr=0.3,0.1

Type RM Length L Ch R = 1 ,13662   ,448,448,448
BEGIN DESCRIPTION:
Stream0799 27.0
END DESCRIPTION:
XS GIS Cut Line= 3
      2434375.01       13592575.        2433875.       13592275.
        2433375.       13592275.
#Sta/Elev= 30
  4416.9  336.42  4519.9   333.8  4565.4  333.43  4736.2  330.95  4753.2  330.77
  4766.8  331.55  4801.5  330.42  4875.6  329.76  4891.2  328.75    4897  328.99
  4906.7  328.19  4941.7   322.9  4949.5  324.19  4976.7  324.38  4986.4  321.93
  4987.1  320.36  4987.6  319.86  4996.8  319.86  4997.3  320.36  5002.5  320.76
    5010  324.14    5020  326.04    5023  325.91    5040  325.46    5050  326.11
    5070  329.71    5090  330.48    5180  329.69    5250  330.19    5500  333.81
#Mann= 7 ,-1 , 0
  4416.9     .05       0  4565.4     .07       0  4736.2     .05       0
  4801.5      .1       0  4987.1     .05       0  4997.3      .1       0
    5023     .07       0
Bank Sta=4987.1,4997.3
XS Rating Curve= 0 ,0
Exp/Cntr=0.3,0.1

Type RM Length L Ch R = 1 ,13214   ,480,480,480
BEGIN DESCRIPTION:
Stream0799 26.0
END DESCRIPTION:
XS GIS Cut Line= 3
      2434375.03     13592175.02        2433925.       13591875.
      2433524.99     13592075.01
#Sta/Elev= 30
  4455.6  333.52  4658.5  329.53  4801.2  328.65  4916.8  327.77  4924.4  327.06
  4931.9  325.11  4937.9  325.12  4946.9  324.03  4952.9  324.81  4960.4  321.85
  4962.6  318.69  4963.1  318.19  4972.7  318.19  4973.2  318.69    4989  319.48
  4993.5  321.84  4999.3  321.84  5004.9  323.08  5055.2  323.85  5071.9  325.21
  5085.9  325.55  5108.3  327.67  5120.1  327.68  5143.1  327.56    5167  327.17
  5183.7  324.65  5220.1   327.7  5306.7  329.27    5385  330.83  5443.7  331.11
#Mann= 7 ,-1 , 0
  4455.6     .05       0  4801.2      .1       0  4962.6     .05       0
  4973.2      .1       0  5120.1     .07       0  5143.1      .1       0
  5306.7     .07       0
Bank Sta=4962.6,4973.2
XS Rating Curve= 0 ,0
Exp/Cntr=0.3,0.1

Type RM Length L Ch R = 1 ,12734   ,430,430,430
BEGIN DESCRIPTION:
H21073
END DESCRIPTION:
XS GIS Cut Line= 3
      2434450.76     13592048.81      2433886.89     13591565.49
      2432949.32     13591480.25
#Sta/Elev= 30
  3994.2  333.98  4000.4  334.25  4059.3  333.12  4126.8  332.19  4263.5  329.76
  4275.9  329.77  4298.9  328.85  4504.2  326.55  4592.5  327.16  4724.8   327.9
  4859.3  324.15  4919.5  325.19  4969.7  321.97  4999.8  321.75  5009.9  320.67
  5024.6  317.52  5025.1  317.02  5035.4  317.52    5040  320.25  5100.2  325.36
  5120.3  326.14  5127.1   328.2  5132.1   326.7  5160.5  331.65  5190.6  334.36
  5250.9  337.49  5432.1  344.05    5522  348.37  5582.2  349.67  5678.3  354.96
#Mann= 10 ,-1 , 0
  3994.2     .07       0  4000.4     .05       0  4059.3     .07       0
  4126.8     .05       0  4263.5     .07       0  4275.9     .05       0
  4592.5      .1       0  5024.6     .05       0  5035.4      .1       0
  5432.1     .12       0
Bank Sta=5024.6,5035.4
XS Rating Curve= 0 ,0
Exp/Cntr=0.3,0.1

Type RM Length L Ch R = 1 ,12304   ,446,446,446
BEGIN DESCRIPTION:
Stream0799 25.0
END DESCRIPTION:
XS GIS Cut Line= 3
      2434575.03     13592125.03        2433875.       13591325.
      2433674.96     13591174.97
#Sta/Elev= 30
  3932.3  334.97  3980.7  334.39  4074.2  333.29  4087.1  333.76  4125.3  333.52
  4221.4  331.78    4291  330.94  4353.5     330  4463.8  327.67  4548.8  327.32
  4591.5  325.58  4655.1  327.49  4718.7  326.54  4841.8  326.16  4884.7  325.54
  4910.4  323.38  4933.4  316.62  4933.9  316.12  4943.8  316.12  4944.3  316.62
    4974  317.42  4981.6  318.88    4992  319.65  5017.2  320.22    5036  321.96
  5067.2  324.82  5102.6  330.36  5167.2  331.75  5188.1  333.23  5245.4  335.53
#Mann= 12 ,-1 , 0
  3932.3     .05       0  3980.7     .07       0  4087.1     .05       0
  4125.3     .07       0  4221.4     .05       0    4291     .07       0
  4353.5     .05       0  4841.8      .1       0  4884.7     .07       0
  4933.4     .05       0  4944.3     .07       0    5036     .05       0
Bank Sta=4933.4,4944.3
XS Rating Curve= 0 ,0
Exp/Cntr=0.3,0.1

Type RM Length L Ch R = 1 ,11858   ,469,469,469
BEGIN DESCRIPTION:
Stream0799 24.0
END DESCRIPTION:
XS GIS Cut Line= 3
      2434724.97     13591824.96        2434175.       13591025.
      2433774.98     13590724.99
#Sta/Elev= 30
  4029.2  332.41  4502.7  325.83  4517.6  327.07  4532.5  332.32  4547.4  333.06
  4568.3  323.52  4604.2  317.59  4654.9  319.07  4684.5  325.78  4696.9  330.44
  4720.6  324.22  4741.5  320.89  4798.4  319.31  4813.3  321.25  4851.6  321.56
  4890.9  321.66  4935.7  321.56  4972.1  316.33  4972.6  315.83  4983.1  316.33
  5018.1  317.61    5114  323.03  5236.4   329.3  5242.7  330.29  5271.9  342.72
  5286.4  344.83  5292.7  343.41  5307.3  345.74  5416.6  345.25    5500  345.63
#Mann= 8 ,-1 , 0
  4029.2     .05       0  4851.6     .07       0  4890.9      .1       0
  4972.1     .05       0  4983.1      .1       0  5018.1     .12       0
    5114     .05       0  5416.6    .045       0
Bank Sta=4972.1,4983.1
XS Rating Curve= 0 ,0
Exp/Cntr=0.3,0.1

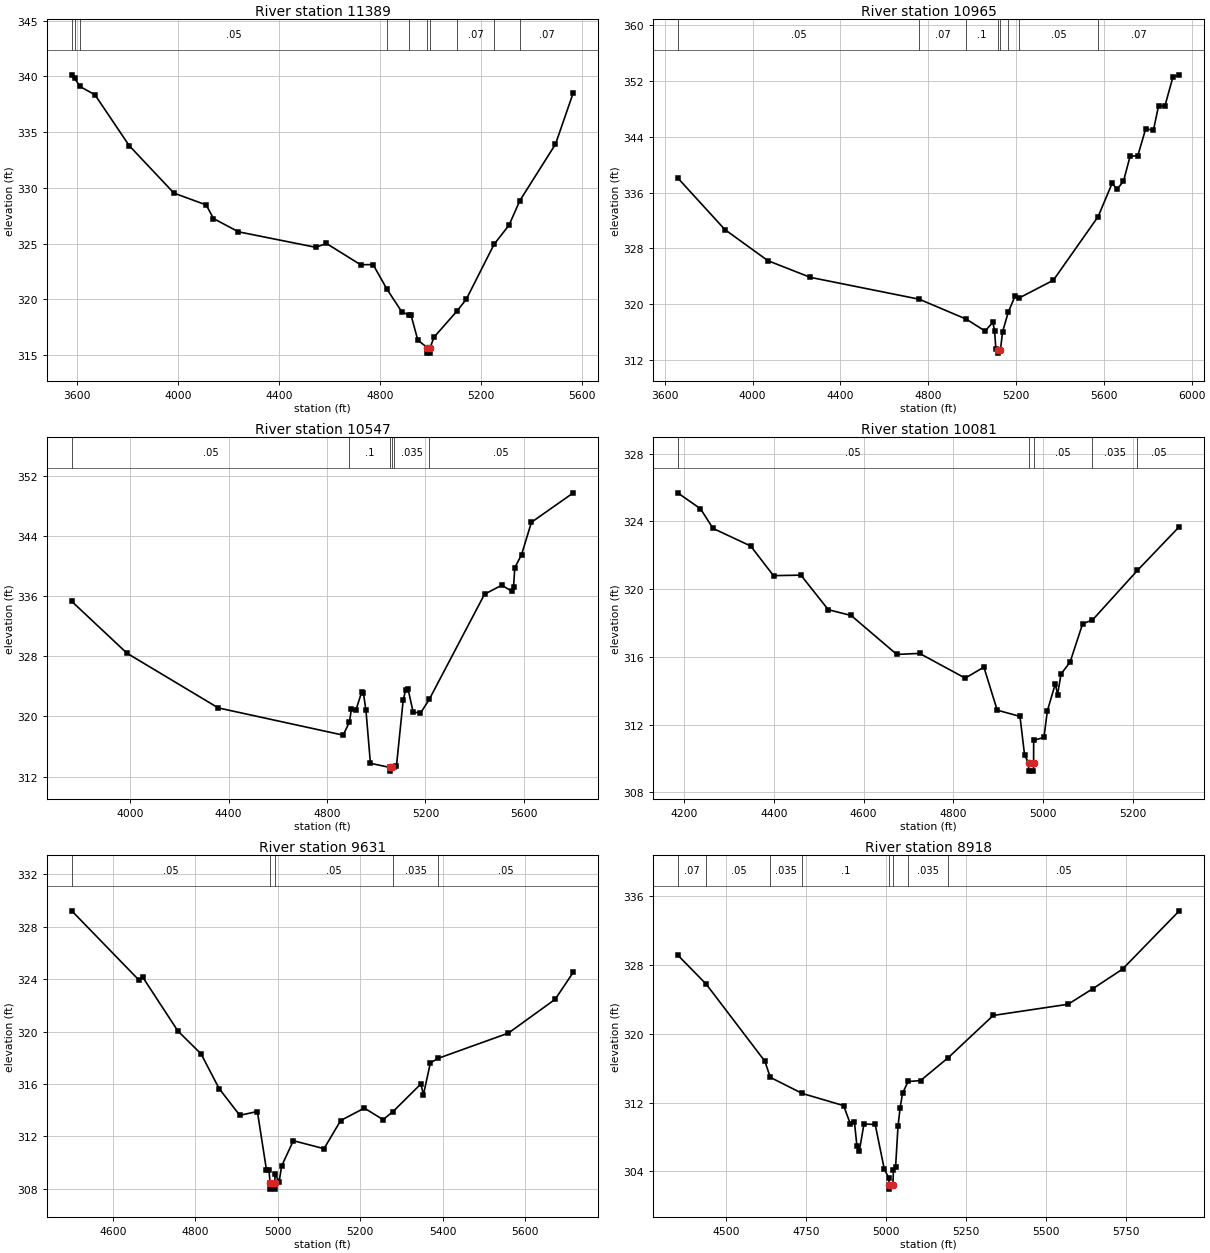
Type RM Length L Ch R = 1 ,11389   ,424,424,424
BEGIN DESCRIPTION:
Stream0799 23.0
END DESCRIPTION:
XS GIS Cut Line= 3
      2435375.03     13591775.03        2434475.       13590675.
        2434075.       13590275.
#Sta/Elev= 30
  3578.9  340.15  3590.9  339.83  3611.1  339.11  3670.8  338.36  3806.5   333.8
  3983.8  329.54  4111.6  328.48  4140.3  327.26  4239.3  326.07  4545.8  324.68
  4587.5  325.03  4723.1  323.12  4772.7  323.13  4827.8  320.92  4886.1   318.9
  4916.7  318.58  4922.7  318.62    4950  316.34  4987.5  315.69    4988  315.19
  4998.1  315.19  4998.6  315.69  5014.4  316.63  5104.1  318.94  5141.6  320.01
  5252.2  324.96  5311.3  326.67  5353.8  328.86  5495.2  333.93  5565.9  338.56
#Mann= 10 ,-1 , 0
  3578.9     .05       0  3590.9    .035       0  3611.1     .05       0
  4827.8     .07       0  4916.7      .1       0  4987.5     .05       0
  4998.6      .1       0  5104.1     .07       0  5252.2     .12       0
  5353.8     .07       0
Bank Sta=4987.5,4998.6
XS Rating Curve= 0 ,0
Exp/Cntr=0.3,0.1

Type RM Length L Ch R = 1 ,10965   ,418,418,418
BEGIN DESCRIPTION:
Stream0799 22.0
END DESCRIPTION:
XS GIS Cut Line= 3
      2435375.01     13591625.03        2434775.       13590425.
      2433974.97     13589924.98
#Sta/Elev= 30
  3658.6  338.11  3873.9  330.69  4069.5  326.24  4262.4  323.85  4759.1  320.71
  4973.6  317.85  5059.2  316.15  5094.6  317.41  5102.3  316.15  5108.2  313.62
    5118  313.48  5118.5  312.98  5129.1  313.48  5138.8  316.03  5164.4  318.83
  5196.6  321.24  5213.6  320.88    5370  323.43  5574.1  332.56  5637.7  337.33
  5660.6  336.49  5689.5  337.63  5719.6   341.2    5755   341.3  5790.4  345.11
  5826.3  344.99  5849.3  348.44  5878.2   348.4  5914.8  352.58  5943.7  352.89
#Mann= 8 ,-1 , 0
  3658.6     .05       0  4759.1     .07       0  4973.6      .1       0
    5118     .05       0  5129.1      .1       0  5164.4     .07       0
  5213.6     .05       0  5574.1     .07       0
Bank Sta=5118,5129.1
XS Rating Curve= 0 ,0
Exp/Cntr=0.3,0.1

Type RM Length L Ch R = 1 ,10547   ,466,466,466
BEGIN DESCRIPTION:
Stream0799 21.0
END DESCRIPTION:
XS GIS Cut Line= 3
      2435425.01     13591525.03        2435125.       13590325.
        2435175.     13589525.02
#Sta/Elev= 30
  3762.6  335.29  3986.8  328.41  4357.9  321.14  4865.6  317.52  4891.1  319.25
  4899.1  320.95  4917.1   320.8  4940.3  323.19    4948  323.08  4958.3  320.82
  4976.4  313.78  5054.1  313.24  5054.6  312.74  5065.3  313.24    5071  313.33
  5082.2   313.4  5109.8  322.23  5119.8  323.53  5129.8  323.59  5149.9   320.6
  5179.9  320.45  5215.6  322.27  5440.4  336.25  5510.6  337.44  5550.6  336.64
  5558.1  337.22  5563.2  339.77  5590.7   341.5  5630.8   345.8  5801.1  349.71
#Mann= 6 ,-1 , 0
  3762.6     .05       0  4891.1      .1       0  5054.1     .05       0
  5065.3      .1       0    5071    .035       0  5215.6     .05       0
Bank Sta=5054.1,5065.3
XS Rating Curve= 0 ,0
Exp/Cntr=0.3,0.1

Type RM Length L Ch R = 1 ,10081   ,450,450,450
BEGIN DESCRIPTION:
Stream0799 20.0
END DESCRIPTION:
XS GIS Cut Line= 3
      2435425.01     13591174.96        2435575.       13590375.
      2435525.01     13590075.03
#Sta/Elev= 30
  4185.7  325.68  4236.5  324.74  4264.5  323.58  4348.4  322.54  4399.3  320.79
  4460.4  320.82  4521.4  318.78  4572.3  318.44    4674  316.14  4724.9   316.2
  4826.6  314.74  4868.2  315.39  4897.9  312.85  4948.7  312.48  4958.9   310.2
  4967.7  309.75  4968.2  309.25  4978.5  309.25    4979  309.75  4979.2  311.07
  5002.1  311.24  5009.7  312.81  5027.5  314.41  5032.5  313.77  5040.1  314.98
  5060.4  315.69  5088.3  317.95  5110.2  318.17  5210.5   321.1  5303.7  323.68
#Mann= 5 ,-1 , 0
  4185.7     .05       0  4967.7     .05       0    4979     .05       0
  5110.2    .035       0  5210.5     .05       0
Bank Sta=4967.7,4979
XS Rating Curve= 0 ,0
Exp/Cntr=0.3,0.1

Type RM Length L Ch R = 1 ,9631    ,713,713,713
BEGIN DESCRIPTION:
Stream0799 19.0
END DESCRIPTION:
XS GIS Cut Line= 3
        2436225.     13591025.01        2435925.       13590625.
        2435625.       13589975.
#Sta/Elev= 30
  4500.6  329.22  4664.1  323.91  4672.5  324.16  4757.9  320.04  4814.1  318.29
  4857.9  315.64  4907.9   313.6  4950.6  313.89  4972.5  309.45  4978.7  309.41
  4981.3  308.46  4981.8  307.96  4992.4  307.96  4992.9  308.46  4993.3  309.13
  5003.4  308.52  5009.3  309.72  5037.8  311.66  5112.1  311.05  5152.5   313.2
  5209.9  314.15  5255.3  313.27  5279.6  313.89  5347.1     316    5353  315.16
    5370  317.61  5389.6  317.96  5559.1  319.88  5672.4  322.46  5716.5  324.53
#Mann= 5 ,-1 , 0
  4500.6     .05       0  4981.3     .05       0  4992.9     .05       0
  5279.6    .035       0  5389.6     .05       0
Bank Sta=4981.3,4992.9
XS Rating Curve= 0 ,0
Exp/Cntr=0.3,0.1

Type RM Length L Ch R = 1 ,8918    ,232,232,232
BEGIN DESCRIPTION:
Stream0799 18.0
END DESCRIPTION:
XS GIS Cut Line= 3
        2436475.     13590774.98      2436419.29     13590382.48
      2435525.01     13589625.01
#Sta/Elev= 30
  4348.3  329.14  4438.1  325.73    4621   316.8  4637.9  314.93  4737.9  313.06
    4867  311.65  4887.9  309.57  4901.1  309.72  4908.7  306.97  4916.5  306.42
  4930.8  309.51  4965.9  309.46  4994.5  304.25  5008.7  303.25  5009.5  302.45
    5010  301.95  5021.1  302.45    5023  304.18  5029.6  304.48  5037.3  309.27
  5043.9   311.4  5051.6   313.1  5068.9  314.45  5107.6  314.55  5194.7  317.23
    5335  322.12    5569  323.42    5647  325.24  5739.3   327.5  5916.7  334.27
#Mann= 8 ,-1 , 0
  4348.3     .07       0  4438.1     .05       0  4637.9    .035       0
  4737.9      .1       0  5009.5     .05       0  5021.1      .1       0
  5068.9    .035       0  5194.7     .05       0
Bank Sta=5009.5,5021.1
XS Rating Curve= 0 ,0
Exp/Cntr=0.3,0.1