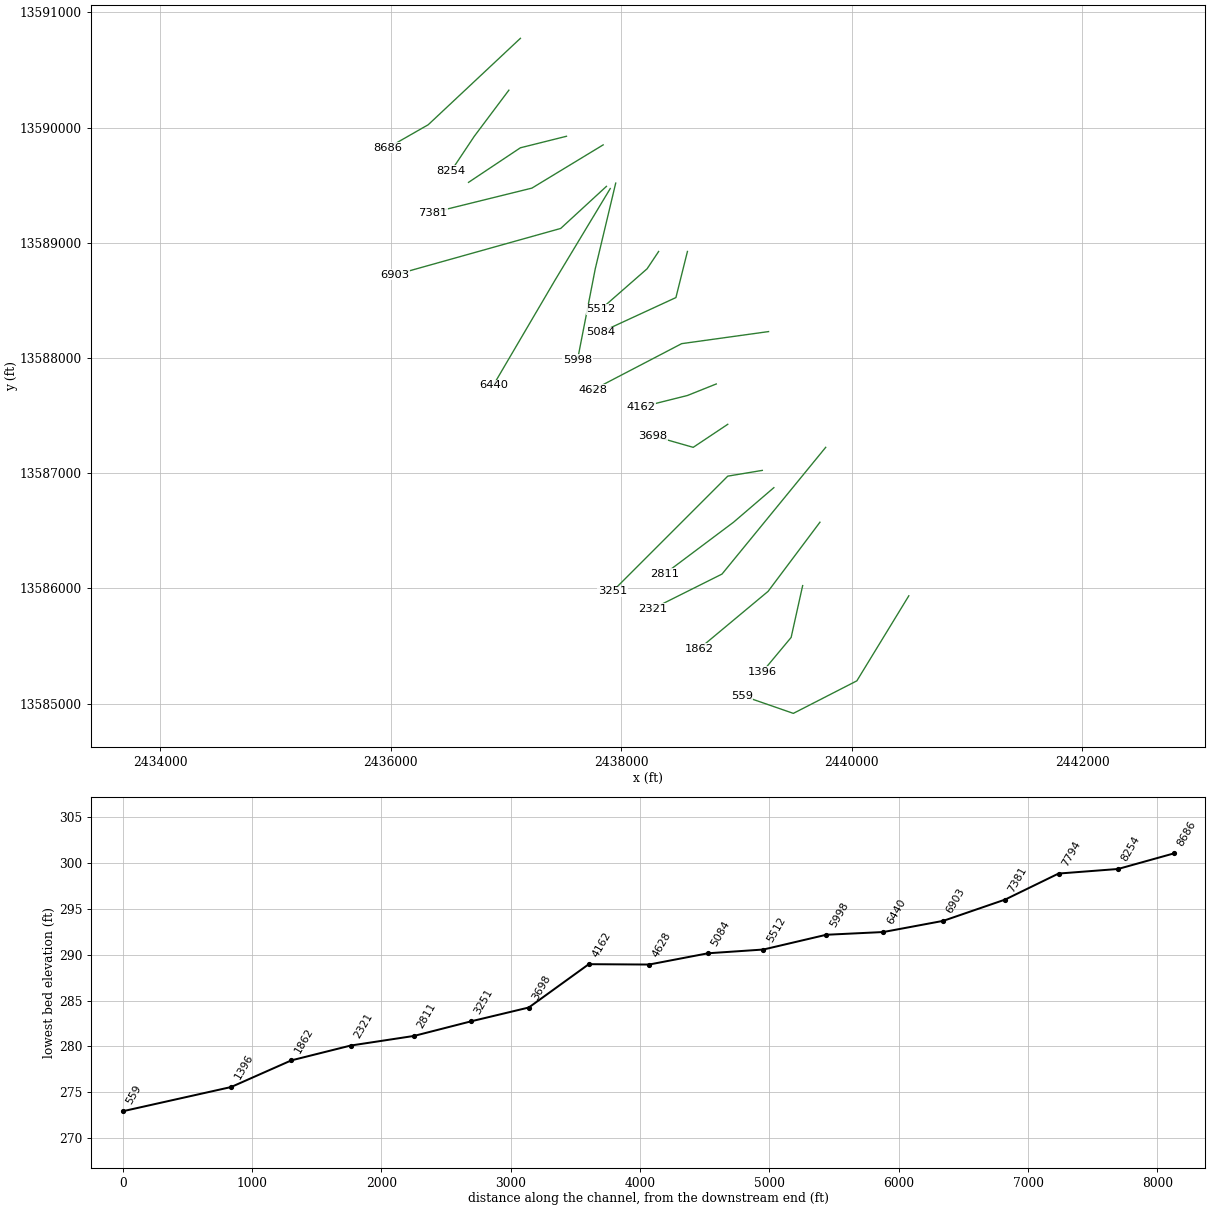
HEC-RAS study Stream0799.prj: Stream0799 Base Level Engineering

--- Stream0799.g01 (geometry) --- (continued)

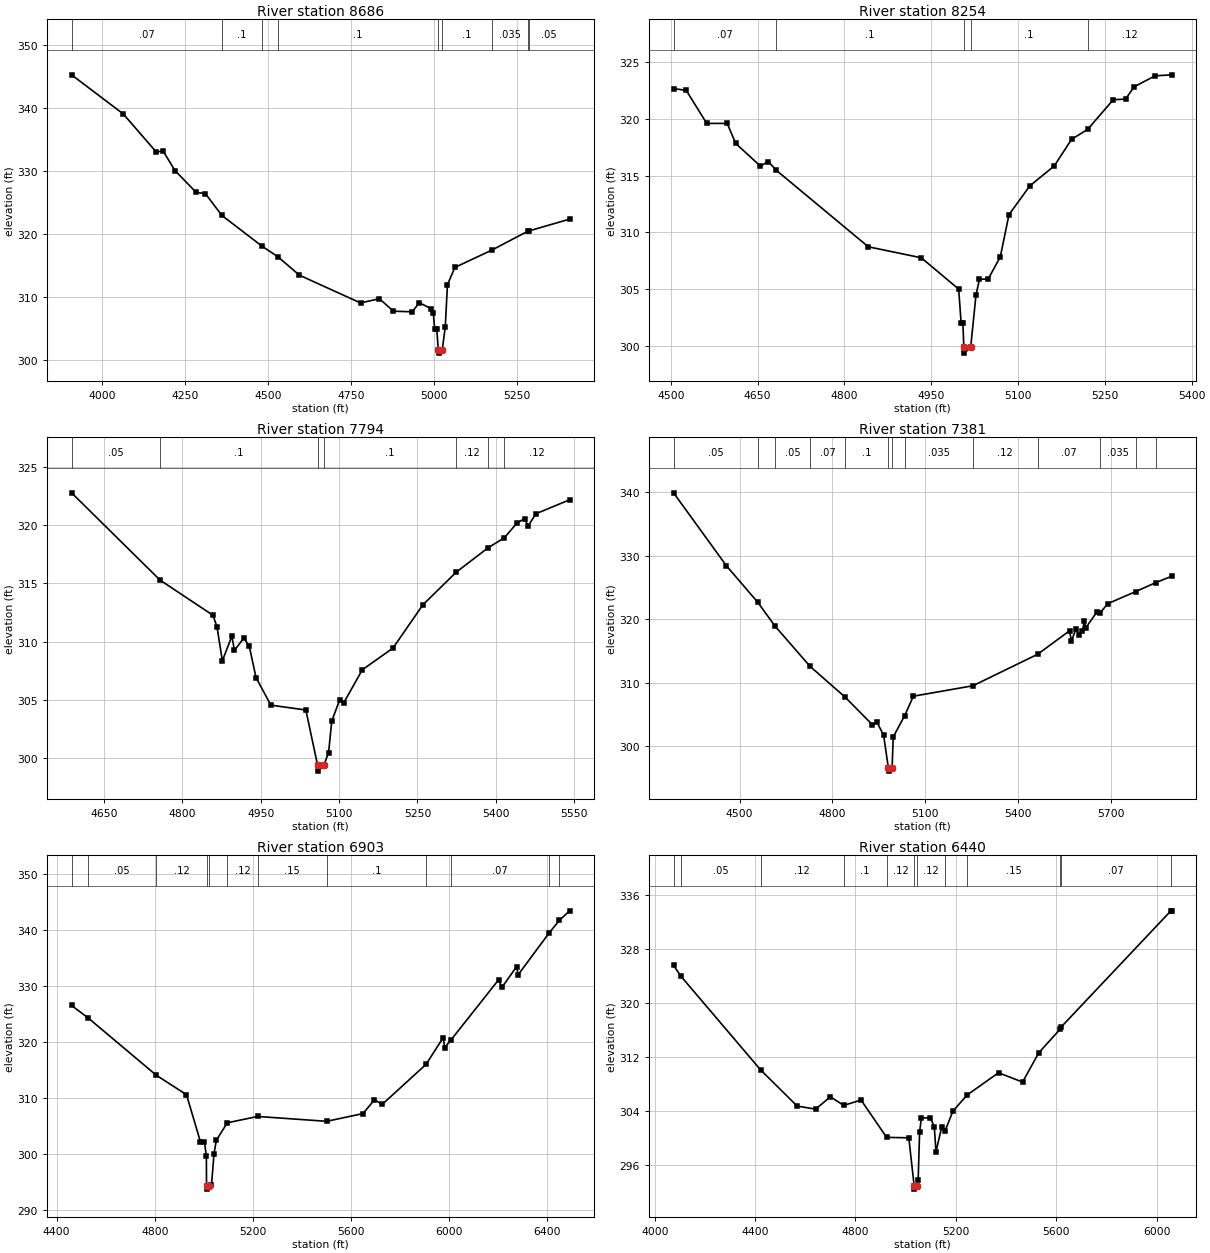
Type RM Length L Ch R = 1 ,8686    ,432,432,432
BEGIN DESCRIPTION:
Stream0799 17.0
END DESCRIPTION:
XS GIS Cut Line= 3
      2437125.03     13590775.03        2436325.       13590025.
      2435975.03     13589825.02
#Sta/Elev= 30
  3907.7  345.27  4063.3  339.06  4162.5  333.03  4183.5  333.16  4219.1  330.06
  4282.6  326.62    4311  326.39  4360.1  322.95  4480.1   318.1  4529.1  316.37
  4593.8  313.45  4777.9  309.04  4834.6  309.71  4877.1  307.73  4933.7  307.63
  4954.7  309.08  4990.4  308.13  4997.2  307.37  5000.9  304.94  5007.2  304.94
  5012.2  301.57  5012.7  301.07  5023.9  301.57  5033.1  305.27  5039.6  311.93
  5061.9  314.68  5172.9  317.42  5282.7  320.46  5284.4  320.47  5407.4  322.35
#Mann= 9 ,-1 , 0
  3907.7     .07       0  4360.1      .1       0  4480.1     .07       0
  4529.1      .1       0  5012.2     .05       0  5023.9      .1       0
  5172.9    .035       0  5282.7     .12       0  5284.4     .05       0
Bank Sta=5012.2,5023.9
XS Rating Curve= 0 ,0
Exp/Cntr=0.3,0.1

Type RM Length L Ch R = 1 ,8254    ,460,460,460
BEGIN DESCRIPTION:
Stream0799 16.0
END DESCRIPTION:
XS GIS Cut Line= 3
      2437025.01     13590325.02        2436725.       13589925.
      2436524.99     13589624.98
#Sta/Elev= 30
  4504.7  322.68  4526.6  322.52    4562  319.61  4597.4  319.61    4612  317.85
  4654.7  315.85  4668.3  316.25  4682.2  315.48  4841.2  308.74  4932.8  307.77
  4997.4  305.01  5001.6  302.03  5004.7  302.03  5006.3  299.87  5006.8  299.37
  5018.1  299.87  5027.3  304.49  5033.3  305.89  5048.3  305.89  5069.3  307.85
  5084.3  311.57  5120.4  314.11  5162.5  315.86  5192.5  318.21  5220.2  319.08
  5264.6   321.7  5285.7  321.75  5300.7  322.84  5336.7   323.8  5365.3  323.89
#Mann= 5 ,-1 , 0
  4504.7     .07       0  4682.2      .1       0  5006.3     .05       0
  5018.1      .1       0  5220.2     .12       0
Bank Sta=5006.3,5018.1
XS Rating Curve= 0 ,0
Exp/Cntr=0.3,0.1

Type RM Length L Ch R = 1 ,7794    ,413,413,413
BEGIN DESCRIPTION:
Stream0799 15.0
END DESCRIPTION:
XS GIS Cut Line= 3
        2437525.       13589925.        2437125.       13589825.
      2436675.03     13589525.02
#Sta/Elev= 30
    4588  322.78  4757.4  315.28  4858.6  312.26  4866.3  311.27  4876.6  308.35
  4894.7  310.46  4899.8  309.24  4917.8  310.32  4928.2  309.58    4941  306.91
  4969.4  304.54  5036.4  304.12  5058.9  299.37  5059.4  298.87  5070.9  299.37
  5079.9  300.47  5085.9  303.16    5101  304.98  5108.5  304.71  5144.5  307.58
  5203.1  309.44  5260.2  313.15  5323.8  315.95  5384.3  318.03  5416.5  318.93
  5440.5  320.19  5455.5  320.57  5461.5  319.91  5476.5  320.98  5541.1  322.18
#Mann= 7 ,-1 , 0
    4588     .05       0  4757.4      .1       0  5058.9     .05       0
  5070.9      .1       0  5323.8     .12       0  5384.3    .035       0
  5416.5     .12       0
Bank Sta=5058.9,5070.9
XS Rating Curve= 0 ,0
Exp/Cntr=0.3,0.1

Type RM Length L Ch R = 1 ,7381    ,478,478,478
BEGIN DESCRIPTION:
Stream0799 14.0
END DESCRIPTION:
XS GIS Cut Line= 3
      2437843.43     13589850.23        2437225.       13589475.
      2436364.99     13589262.65
#Sta/Elev= 30
  4286.9   339.9  4457.8  328.39  4558.9  322.65  4614.7  318.89  4727.8  312.55
  4840.9  307.71  4928.9  303.37  4944.4  303.73  4965.7  301.67    4981  296.53
  4981.5  296.03    4993  296.53  4996.7  301.43  5033.3  304.74  5061.8  307.84
  5254.4  309.49  5463.2  314.45  5566.5  318.15  5572.5  316.54  5587.1  318.44
  5597.4  317.52  5607.7   318.1    5614  319.62  5619.1  318.64  5655.4  321.15
  5664.4  320.94  5690.1  322.43  5779.9  324.33  5845.5  325.76  5896.1  326.74
#Mann= 13 ,-1 , 0
  4286.9     .05       0  4558.9     .07       0  4614.7     .05       0
  4727.8     .07       0  4840.9      .1       0    4981     .05       0
    4993      .1       0  5033.3    .035       0  5254.4     .12       0
  5463.2     .07       0  5664.4    .035       0  5779.9     .07       0
  5845.5    .035       0
Bank Sta=4981,4993
XS Rating Curve= 0 ,0
Exp/Cntr=0.3,0.1

Type RM Length L Ch R = 1 ,6903    ,463,463,463
BEGIN DESCRIPTION:
Stream0799 13.0
END DESCRIPTION:
XS GIS Cut Line= 3
      2437871.83      13589490.1        2437475.       13589125.
      2436039.01     13588722.75
#Sta/Elev= 30
  4460.8  326.48  4528.7  324.25  4806.3  314.03  4929.4  310.56  4986.1  302.18
  5002.6  302.18  5010.4  299.55  5011.1  294.21  5011.6  293.71  5023.1  294.21
  5031.2  294.38  5041.6  300.03  5051.2  302.44  5095.5  305.54  5219.4  306.68
  5500.8  305.81  5648.9  307.19  5695.8  309.65  5727.6  308.84  5906.2  315.98
  5976.2  320.76  5981.9  318.96  6007.5  320.32  6202.2  331.08  6215.1  329.69
  6275.6  333.42  6280.8  331.91  6409.1  339.49  6449.6  341.66  6491.3  343.37
#Mann= 12 ,-1 , 0
  4460.8    .035       0  4528.7     .05       0  4806.3     .12       0
  5011.1     .05       0  5023.1     .12       0  5095.5     .12       0
  5219.4     .15       0  5500.8      .1       0  5906.2     .12       0
  6007.5     .07       0  6409.1    .035       0  6449.6     .05       0
Bank Sta=5011.1,5023.1
XS Rating Curve= 0 ,0
Exp/Cntr=0.3,0.1

Type RM Length L Ch R = 1 ,6440    ,442,442,442
BEGIN DESCRIPTION:
Stream0799 12.0
END DESCRIPTION:
XS GIS Cut Line= 3
      2437904.97     13589471.11        2437425.       13588675.
        2436891.     13587765.36
#Sta/Elev= 30
  4075.2  325.59  4104.4     324  4422.1  310.13    4568  304.77  4641.7  304.33
    4700  306.16    4753  304.88  4822.3  305.67  4924.1  300.15  5012.6  300.08
  5033.8  292.99  5034.3  292.49    5046  292.99  5049.8  293.83  5055.6  300.96
  5062.8  303.02  5098.5  303.05  5114.2  301.69  5120.8  298.01  5143.9  301.72
  5157.1  301.12  5188.5  304.05    5246  306.45  5370.1  309.71  5465.9  308.33
  5530.3  312.66  5616.6   316.2  5620.7  316.52  6056.4  333.65  6059.6  333.67
#Mann= 12 ,-1 , 0
  4075.2    .035       0  4104.4     .05       0  4422.1     .12       0
    4753      .1       0  4924.1     .12       0  5033.8     .05       0
    5046     .12       0  5157.1     .07       0    5246     .15       0
  5616.6      .1       0  5620.7     .07       0  6056.4     .05       0
Bank Sta=5033.8,5046
XS Rating Curve= 0 ,0
Exp/Cntr=0.3,0.1

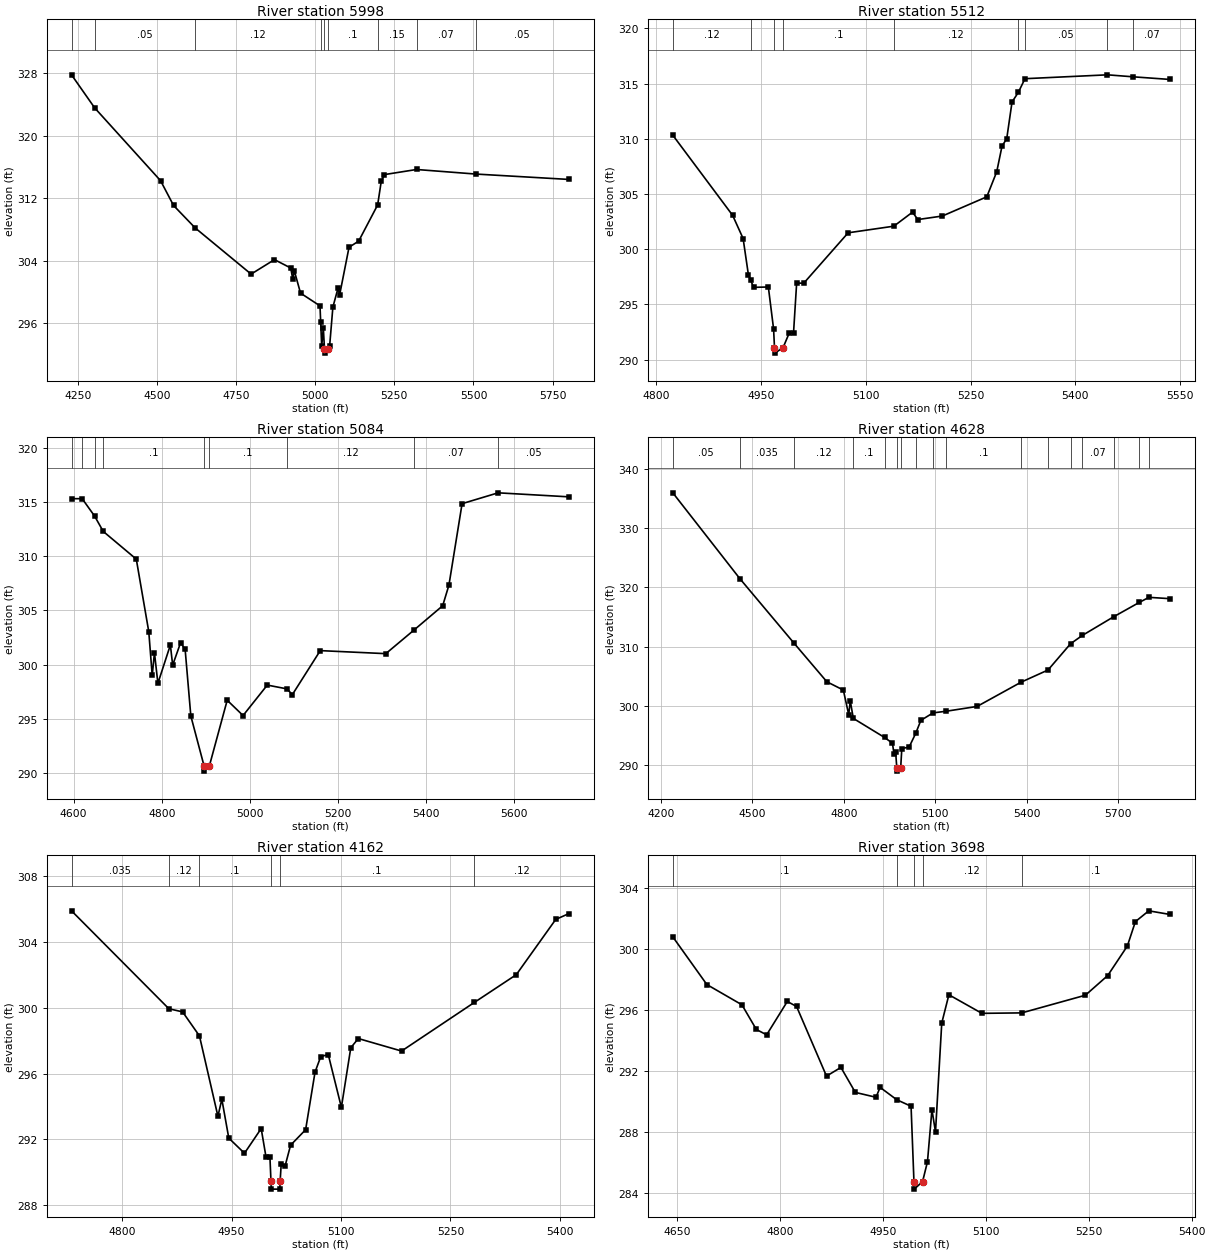
Type RM Length L Ch R = 1 ,5998    ,486,486,486
BEGIN DESCRIPTION:
Stream0799 11.0
END DESCRIPTION:
XS GIS Cut Line= 3
      2437952.37     13589518.53        2437775.       13588775.
      2437620.69     13587983.29
#Sta/Elev= 30
  4230.4  327.76  4303.6  323.53  4511.6  314.23  4552.7  311.06  4620.7   308.2
  4797.6  302.29  4871.4  304.14  4922.8  303.07  4929.1  301.68  4934.2   302.7
  4953.7  299.86  5015.2  298.23  5017.3  296.22  5020.6  293.06  5025.7  295.46
  5029.4  292.69  5029.9  292.19  5041.6  292.69  5045.7  293.13  5055.9  298.07
  5072.2   300.5  5077.3  299.65  5106.9  305.72  5137.4  306.51  5197.3  311.13
  5208.7  314.16  5218.9  315.01  5320.2  315.66  5506.5  315.08  5801.4  314.39
#Mann= 9 ,-1 , 0
  4230.4    .035       0  4303.6     .05       0  4620.7     .12       0
  5017.3      .1       0  5029.4     .05       0  5041.6      .1       0
  5197.3     .15       0  5320.2     .07       0  5506.5     .05       0
Bank Sta=5029.4,5041.6
XS Rating Curve= 0 ,0
Exp/Cntr=0.3,0.1

Type RM Length L Ch R = 1 ,5512    ,428,428,428
BEGIN DESCRIPTION:
Stream0799 10.0
END DESCRIPTION:
XS GIS Cut Line= 3
      2438324.97     13588924.96        2438225.       13588775.
      2437825.03     13588425.02
#Sta/Elev= 30
    4824  310.32  4909.6  303.06  4924.6  300.96  4932.1   297.7  4935.5  297.17
  4939.6  296.54  4960.7  296.57  4968.2  292.77  4969.5  291.08    4970  290.58
  4981.8  291.08  4990.7  292.42  4996.7  292.38  5001.2  296.93  5011.3  296.91
  5074.9  301.48  5140.3  302.08    5167  303.35  5174.6  302.68  5209.7     303
  5273.3  304.74  5287.5  307.01  5295.1  309.34  5301.8     310  5309.4  313.33
  5318.4   314.2  5327.9  315.44    5446  315.79  5482.7  315.61  5535.7  315.37
#Mann= 9 ,-1 , 0
    4824     .12       0  4935.5      .1       0  4969.5     .05       0
  4981.8      .1       0  5140.3     .12       0  5318.4     .15       0
  5327.9     .05       0    5446     .15       0  5482.7     .07       0
Bank Sta=4969.5,4981.8
XS Rating Curve= 0 ,0
Exp/Cntr=0.3,0.1

Type RM Length L Ch R = 1 ,5084    ,456,456,456
BEGIN DESCRIPTION:
Stream0799 9.0
END DESCRIPTION:
XS GIS Cut Line= 3
        2438575.     13588925.01        2438475.       13588525.
      2437825.01     13588225.01
#Sta/Elev= 30
  4595.5  315.31  4619.6  315.31  4647.9   313.7  4667.4  312.29  4742.4  309.73
  4770.7  303.04  4778.5     299  4783.6  301.09  4791.4  298.27  4819.7  301.81
  4824.9  299.95  4842.9  302.02  4853.2   301.4  4866.1  295.26    4896  290.67
  4896.5  290.17  4908.3  290.67  4948.6  296.71  4984.6   295.3  5039.5  298.11
  5084.1  297.76  5096.4  297.23  5159.7  301.29  5308.4  301.01  5373.3  303.22
  5437.4  305.43  5451.6  307.34  5481.4  314.85  5563.2  315.85  5723.7  315.48
#Mann= 9 ,-1 , 0
  4595.5     .12       0  4619.6     .07       0  4647.9     .12       0
  4667.4      .1       0    4896     .05       0  4908.3      .1       0
  5084.1     .12       0  5373.3     .07       0  5563.2     .05       0
Bank Sta=4896,4908.3
XS Rating Curve= 0 ,0
Exp/Cntr=0.3,0.1

Type RM Length L Ch R = 1 ,4628    ,466,466,466
BEGIN DESCRIPTION:
Stream0799 8.0
END DESCRIPTION:
XS GIS Cut Line= 3
      2439279.06      13588229.7        2438525.       13588125.
      2437753.37      13587722.7
#Sta/Elev= 30
  4238.7  335.97  4458.4  321.48  4636.5  310.55    4744  304.04  4798.1  302.64
  4815.7  298.48  4820.8  300.81  4830.8  297.85  4933.2  294.63  4959.1  293.66
  4964.1  291.91  4969.7  292.12  4973.5  289.44    4974  288.94  4986.1  289.44
  4989.9  292.75  5013.9  293.01  5035.5  295.33  5052.4  297.52  5092.2  298.78
  5136.4  299.07  5236.8  299.87  5381.1  303.97  5469.5  306.03  5543.3  310.46
    5582  311.87  5684.6  315.02  5768.9  317.45  5800.6  318.31  5870.2  318.08
#Mann= 17 ,-1 , 0
  4238.7     .05       0  4458.4    .035       0  4636.5     .12       0
  4830.8      .1       0  4933.2     .12       0  4973.5     .05       0
  4986.1     .12       0  5035.5      .1       0  5092.2     .12       0
  5136.4      .1       0  5381.1     .12       0  5469.5     .07       0
  5543.3     .05       0    5582     .07       0  5684.6     .05       0
  5768.9     .07       0  5800.6     .05       0
Bank Sta=4973.5,4986.1
XS Rating Curve= 0 ,0
Exp/Cntr=0.3,0.1

Type RM Length L Ch R = 1 ,4162    ,464,464,464
BEGIN DESCRIPTION:
Stream0799 7.0
END DESCRIPTION:
XS GIS Cut Line= 3
      2438825.04     13587775.02        2438575.       13587675.
      2438175.02       13587575.
#Sta/Elev= 30
  4730.7  305.89  4864.1  299.94  4882.9  299.75    4906  298.29  4931.3  293.41
  4936.7  294.44  4946.2  292.08  4967.7  291.16  4990.6  292.66  4997.3  290.91
  5002.6  290.91    5004  289.48  5004.5  288.98  5016.1  288.98  5016.6  289.48
    5018  290.48  5023.2  290.36  5030.9  291.65  5051.5  292.59  5064.4  296.09
  5072.2  297.03  5082.5  297.16  5100.5  293.95  5113.4  297.57  5123.7  298.13
    5183  297.37  5282.6  300.32  5340.2  302.01  5394.3  305.37  5412.3  305.72
#Mann= 6 ,-1 , 0
  4730.7    .035       0  4864.1     .12       0    4906      .1       0
    5004     .05       0  5016.6      .1       0  5282.6     .12       0
Bank Sta=5004,5016.6
XS Rating Curve= 0 ,0
Exp/Cntr=0.3,0.1

Type RM Length L Ch R = 1 ,3698    ,447,447,447
BEGIN DESCRIPTION:
Stream0799 6.0
END DESCRIPTION:
XS GIS Cut Line= 3
      2438925.02     13587425.01        2438625.       13587225.
      2438274.99       13587325.
#Sta/Elev= 30
  4644.1  300.81  4693.7  297.68  4744.8  296.35  4765.8  294.73  4780.8  294.38
  4810.9  296.57  4824.4  296.24    4868  291.67    4889  292.24    4910   290.6
  4940.1  290.28  4946.1  290.93  4970.3  290.12  4991.2  289.69  4995.4  284.75
  4995.9  284.25    5008  284.75  5015.1  286.05  5021.6  289.47  5026.8     288
  5035.9  295.15  5046.3  297.01  5094.4  295.79  5152.5  295.82  5245.2  296.98
  5277.7  298.27  5306.3  300.21    5318  301.81  5337.5  302.52  5368.7  302.28
#Mann= 5 ,-1 , 0
  4644.1      .1       0  4970.3     .12       0  4995.4     .05       0
    5008     .12       0  5152.5      .1       0
Bank Sta=4995.4,5008
XS Rating Curve= 0 ,0
Exp/Cntr=0.3,0.1

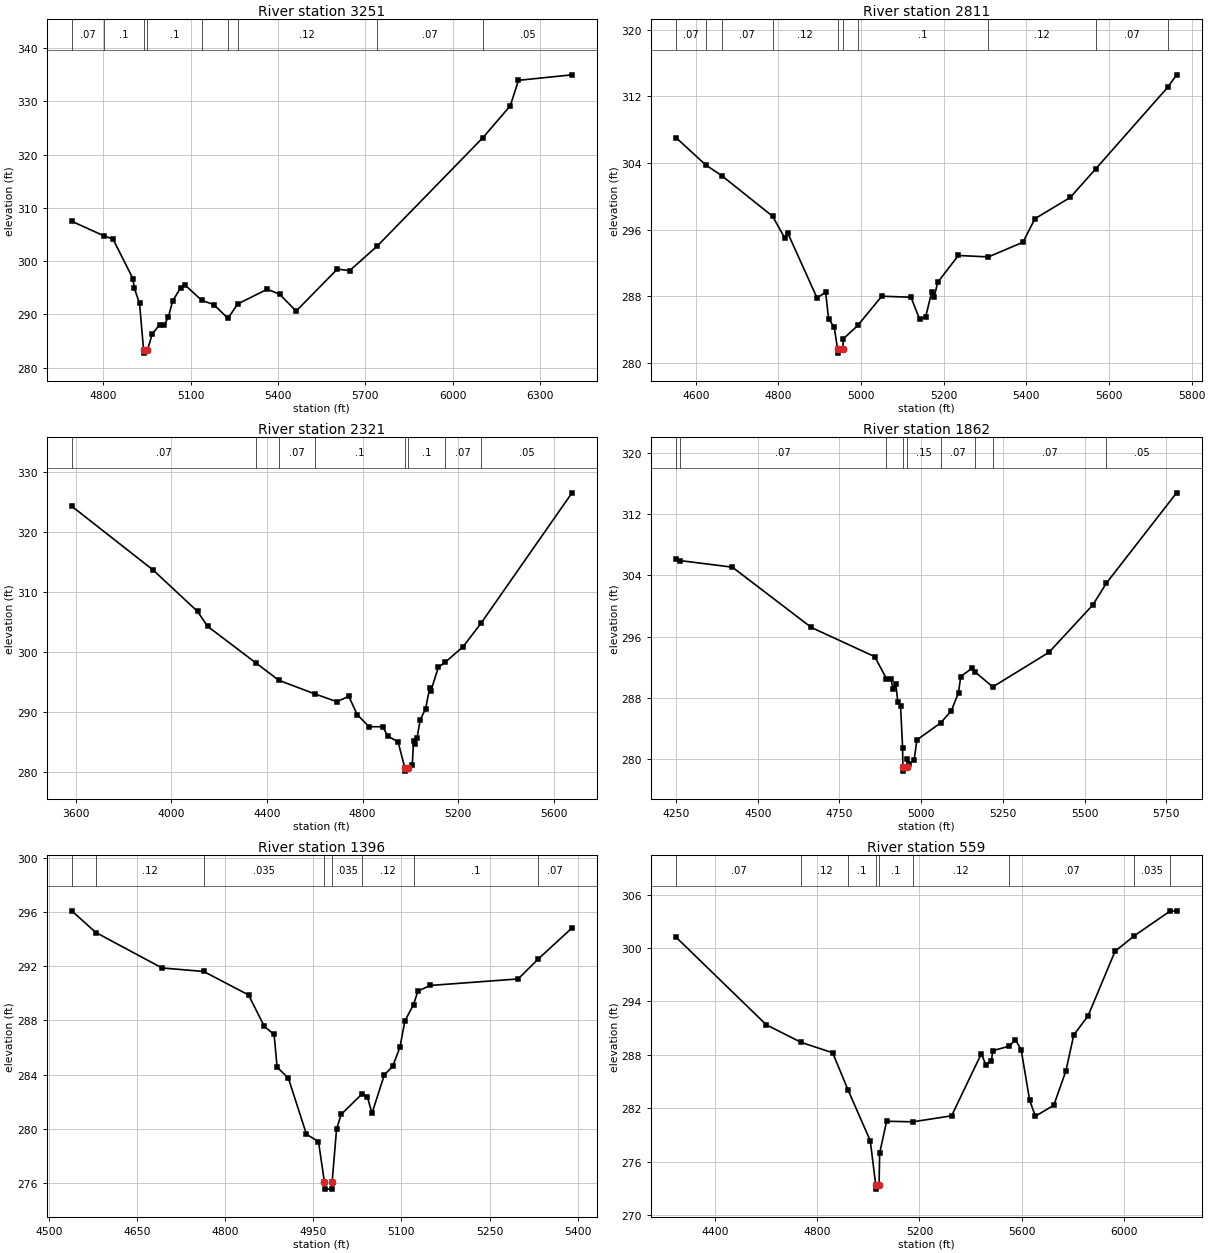
Type RM Length L Ch R = 1 ,3251    ,440,440,440
BEGIN DESCRIPTION:
Stream0799 5.0
END DESCRIPTION:
XS GIS Cut Line= 3
      2439224.95     13587024.99        2438925.       13586975.
        2437925.       13585975.
#Sta/Elev= 30
  4691.3  307.48  4802.5  304.73  4833.2  304.13  4901.6  296.73  4906.7  294.87
  4924.4  292.06  4938.4  283.24  4938.9  282.74  4951.1  283.24  4967.5  286.24
  4992.9  288.08  5009.5  288.05  5023.7  289.56  5037.8  292.51  5066.1  295.03
  5080.2  295.53  5138.3  292.63  5179.2  291.85  5228.1  289.26  5261.3  291.97
  5363.1  294.72  5405.5  293.79  5462.1  290.63  5603.5   298.5  5645.9  298.21
  5739.8  302.78  6103.4  323.15  6197.5  329.13  6225.8  333.92  6409.6  334.95
#Mann= 9 ,-1 , 0
  4691.3     .07       0  4802.5      .1       0  4938.4     .05       0
  4951.1      .1       0  5138.3     .12       0  5228.1      .1       0
  5261.3     .12       0  5739.8     .07       0  6103.4     .05       0
Bank Sta=4938.4,4951.1
XS Rating Curve= 0 ,0
Exp/Cntr=0.3,0.1

Type RM Length L Ch R = 1 ,2811    ,490,490,490
BEGIN DESCRIPTION:
Stream0799 4.0
END DESCRIPTION:
XS GIS Cut Line= 3
      2439324.97     13586874.98        2438975.       13586575.
      2438375.03     13586125.02
#Sta/Elev= 30
  4552.6  307.01  4624.1  303.75    4663  302.46  4786.1  297.58  4815.4  294.95
    4822  295.63  4893.4  287.78  4914.2  288.47  4921.3  285.25  4935.1  284.26
    4943  281.65  4943.5  281.15  4955.7  281.65    4957  282.87  4991.9  284.47
    5050  287.99  5120.8  287.86  5141.7  285.22  5156.2   285.5  5170.8  288.47
  5177.1  287.93  5185.4  289.65  5235.4  292.88  5308.2  292.71  5391.7  294.47
  5420.8   297.3  5506.2  299.85  5568.1   303.3  5743.4  313.16  5763.5  314.58
#Mann= 10 ,-1 , 0
  4552.6     .07       0  4624.1     .12       0    4663     .07       0
  4786.1     .12       0    4943     .05       0  4955.7     .12       0
  4991.9      .1       0  5308.2     .12       0  5568.1     .07       0
  5743.4     .05       0
Bank Sta=4943,4955.7
XS Rating Curve= 0 ,0
Exp/Cntr=0.3,0.1

Type RM Length L Ch R = 1 ,2321    ,459,459,459
BEGIN DESCRIPTION:
Stream0799 3.0
END DESCRIPTION:
XS GIS Cut Line= 3
      2439775.01     13587225.02        2438875.       13586125.
      2438275.01       13585825.
#Sta/Elev= 30
  3583.2  324.25  3924.2  313.59  4109.4  306.71  4151.7  304.22    4354  298.11
  4449.3  295.24  4599.4  292.97  4692.2  291.67  4741.8  292.57  4776.9  289.53
  4826.5   287.5  4883.9   287.5  4904.7  285.95  4947.8     285  4976.5   280.6
    4977   280.1  4989.4   280.6  5007.3  281.08  5012.9  285.19  5018.5  284.54
  5026.8  285.55  5040.8  288.69  5063.2   290.5    5080  293.97  5085.5  293.51
  5116.3  297.39  5145.5  298.26  5219.7  300.82  5294.8  304.74  5675.3  326.47
#Mann= 8 ,-1 , 0
  3583.2     .07       0    4354     .12       0  4449.3     .07       0
  4599.4      .1       0  4976.5     .05       0  4989.4      .1       0
  5145.5     .07       0  5294.8     .05       0
Bank Sta=4976.5,4989.4
XS Rating Curve= 0 ,0
Exp/Cntr=0.3,0.1

Type RM Length L Ch R = 1 ,1862    ,466,466,466
BEGIN DESCRIPTION:
Stream0799 2.0
END DESCRIPTION:
XS GIS Cut Line= 3
      2439724.98     13586574.97        2439275.       13585975.
      2438674.99     13585474.99
#Sta/Elev= 30
  4250.5  306.17    4262  305.92  4422.3  305.06    4664   297.2  4857.8   293.4
  4893.6  290.55  4907.8  290.46    4914  289.16  4922.3   289.8  4928.6   287.5
  4936.9  287.02  4943.2   281.5    4944  278.98  4944.5  278.48    4957  278.98
  4957.8  280.09    4964  279.41  4978.6  279.95  4986.9  282.55  5059.8  284.77
  5092.2  286.34  5114.4  288.72  5120.9  290.81  5156.7  291.93    5166  291.36
  5219.2  289.46    5391  293.96  5525.7  300.16  5566.6  302.97  5781.5  314.75
#Mann= 9 ,-1 , 0
  4250.5     .12       0    4262     .07       0  4893.6     .15       0
    4944     .05       0    4957     .15       0  5059.8     .07       0
    5166     .12       0  5219.2     .07       0  5566.6     .05       0
Bank Sta=4944,4957
XS Rating Curve= 0 ,0
Exp/Cntr=0.3,0.1

Type RM Length L Ch R = 1 ,1396    ,837,837,837
BEGIN DESCRIPTION:
Stream0799 1.0
END DESCRIPTION:
XS GIS Cut Line= 3
      2439575.01     13586025.04        2439475.       13585575.
      2439225.02     13585275.03
#Sta/Elev= 30
  4538.9  296.08  4580.1  294.48  4692.6  291.87  4763.6  291.61  4839.9  289.88
  4866.8  287.56  4883.4  286.97  4888.5  284.56  4907.7  283.74  4938.5  279.61
  4958.9  279.08  4969.1  276.07  4969.6  275.57  4981.6  275.57  4982.1  276.07
  4989.7  279.99  4997.4  281.07  5033.4   282.6  5042.2  282.36    5050  281.16
  5070.9  283.98  5085.2  284.62  5097.6  286.03    5106  287.97  5120.7  289.17
  5128.1  290.16    5149  290.58  5298.7  291.06  5332.7  292.52  5390.4  294.82
#Mann= 8 ,-1 , 0
  4538.9     .07       0  4580.1     .12       0  4763.6    .035       0
  4969.1    .035       0  4982.1    .035       0  5033.4     .12       0
  5120.7      .1       0  5332.7     .07       0
Bank Sta=4969.1,4982.1
XS Rating Curve= 0 ,0
Exp/Cntr=0.3,0.1

Type RM Length L Ch R = 1 ,559     ,0,0,0
BEGIN DESCRIPTION:
XS7742
END DESCRIPTION:
XS GIS Cut Line= 4
      2440496.42     13585936.31      2440045.44     13585198.35
      2439494.23     13584915.91      2439047.75     13585070.82
#Sta/Elev= 30
  4248.8   301.2  4601.2  291.38  4737.3  289.41  4860.6  288.24  4920.9  284.05
  5007.6  278.37  5028.9  273.43  5029.4  272.93  5042.2  273.43  5044.4  276.97
  5071.6  280.55  5174.6  280.49  5325.7  281.16  5442.3  288.15  5458.9  286.92
  5481.1  287.29  5486.7  288.48  5548.8  288.96  5575.5  289.68  5597.7   288.6
  5630.9  282.93  5653.1  281.12  5725.3  282.34  5772.6  286.19  5803.7  290.25
  5859.2  292.37  5965.1  299.64  6040.5  301.38  6179.3  304.13  6205.6  304.18
#Mann= 9 ,-1 , 0
  4248.8     .07       0  4737.3     .12       0  4920.9      .1       0
  5028.9     .05       0  5042.2      .1       0  5174.6     .12       0
  5548.8     .07       0  6040.5    .035       0  6179.3     .05       0
Bank Sta=5028.9,5042.2
XS Rating Curve= 0 ,0
Exp/Cntr=0.3,0.1

Chan Stop Cuts=-1
Use User Specified Reach Order=0
Composite Channel Slope=5