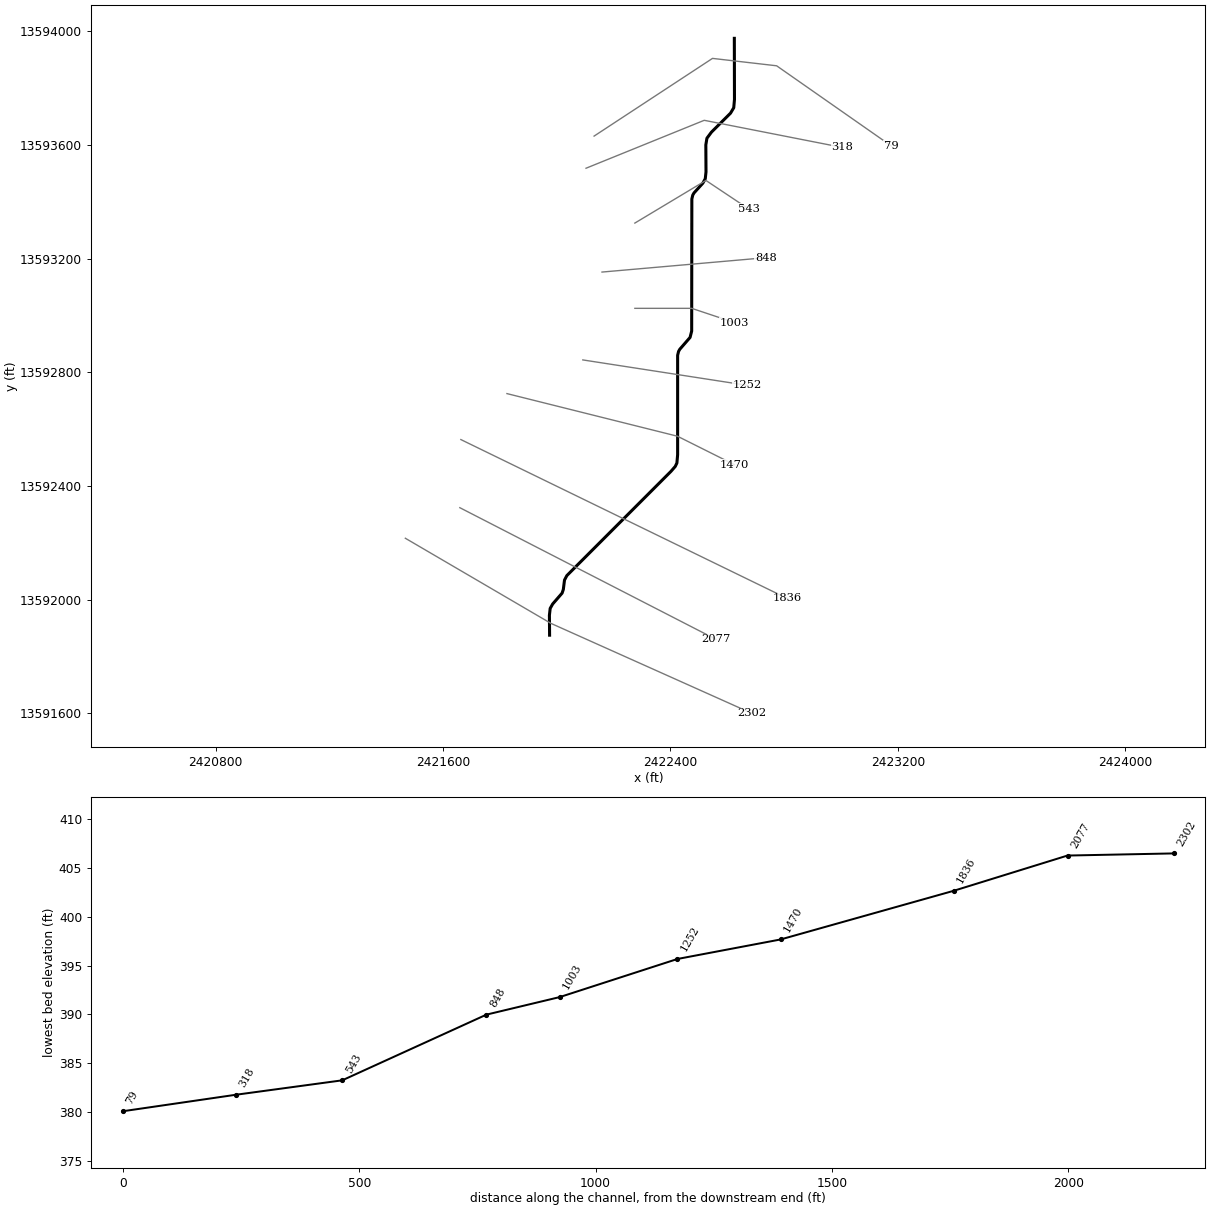
--- Stream0800.prj (project) ---

Proj Title=Stream0800 Base Level Engineering
Current Plan=p01
Default Exp/Contr=0.3,0.1
English Units
Geom File=g01
Flow File=f01
Plan File=p01
BEGIN DESCRIPTION:
Stream0800
END DESCRIPTION:

--- Stream0800.p01 (plan) ---

Plan Title=Multiple Run
Short Identifier=Multiple
Geom File=g01
Flow File=f01
Subcritical Flow
K Sum by GR= 0
Std Step Tol= 0.01
Critical Tol= 0.01
Num of Std Step Trials= 20
Max Error Tol= 0.3
Flow Tol Ratio= 0.001
Split Flow NTrial= 30
Split Flow Tol= 0.02
Split Flow Ratio= 0.02
Log Output Level= 0
Friction Slope Method= 1
Unsteady Friction Slope Method= 2
Unsteady Bridges Friction Slope Method= 1
Parabolic Critical Depth
Global Vel Dist=  1 , 1 , 1
Global Log Level= 0
CheckData=True
Encroach Param= -1, 0, 0, 0
BEGIN DESCRIPTION:
Multiple Run
END DESCRIPTION:

--- Stream0800.f01 (steady flow) ---

Flow Title=Multiple
Number of Profiles=7
Profile Names=10-year,25-year,50-year,1pct_min,100-year,1pct_plu,500-year
River Rch & RM= Stream0800,Reach-1,2302
     436     694     926     599    1196    2386    1975
Boundary for River Rch & Prof#=Stream0800,Reach-1,1
Up Type=0
Dn Type=3
Dn Slope=0.005
Boundary for River Rch & Prof#=Stream0800,Reach-1,2
Up Type=0
Dn Type=3
Dn Slope=0.005
Boundary for River Rch & Prof#=Stream0800,Reach-1,3
Up Type=0
Dn Type=3
Dn Slope=0.005
Boundary for River Rch & Prof#=Stream0800,Reach-1,4
Up Type=0
Dn Type=3
Dn Slope=0.005
Boundary for River Rch & Prof#=Stream0800,Reach-1,5
Up Type=0
Dn Type=3
Dn Slope=0.005
Boundary for River Rch & Prof#=Stream0800,Reach-1,6
Up Type=0
Dn Type=3
Dn Slope=0.005
Boundary for River Rch & Prof#=Stream0800,Reach-1,7
Up Type=0
Dn Type=3
Dn Slope=0.005

--- Stream0800.g01 (geometry) ---

Geom Title=Existing Conditions

River Reach=Stream0800,Reach-1
Reach XY= 30
      2421975.00     13591875.00      2421974.36     13591945.27
      2421977.07     13591969.14      2421985.79     13591984.67
      2422018.89     13592022.82      2422023.29     13592035.71
      2422027.49     13592068.97      2422035.76     13592084.68
      2422402.14     13592451.47      2422417.19     13592468.81
      2422422.94     13592480.85      2422425.49     13592509.80
      2422425.52     13592859.78      2422428.78     13592873.43
      2422433.14     13592881.06      2422469.25     13592922.67
      2422474.93     13592945.03      2422475.52     13593409.78
      2422478.78     13593423.43      2422483.14     13593431.06
      2422514.14     13593465.36      2422522.73     13593480.94
      2422525.32     13593504.87      2422524.73     13593600.11
      2422528.56     13593623.53      2422544.65     13593645.14
      2422611.60     13593711.69      2422622.94     13593730.86
      2422625.49     13593759.80      2422625.00     13593975.00

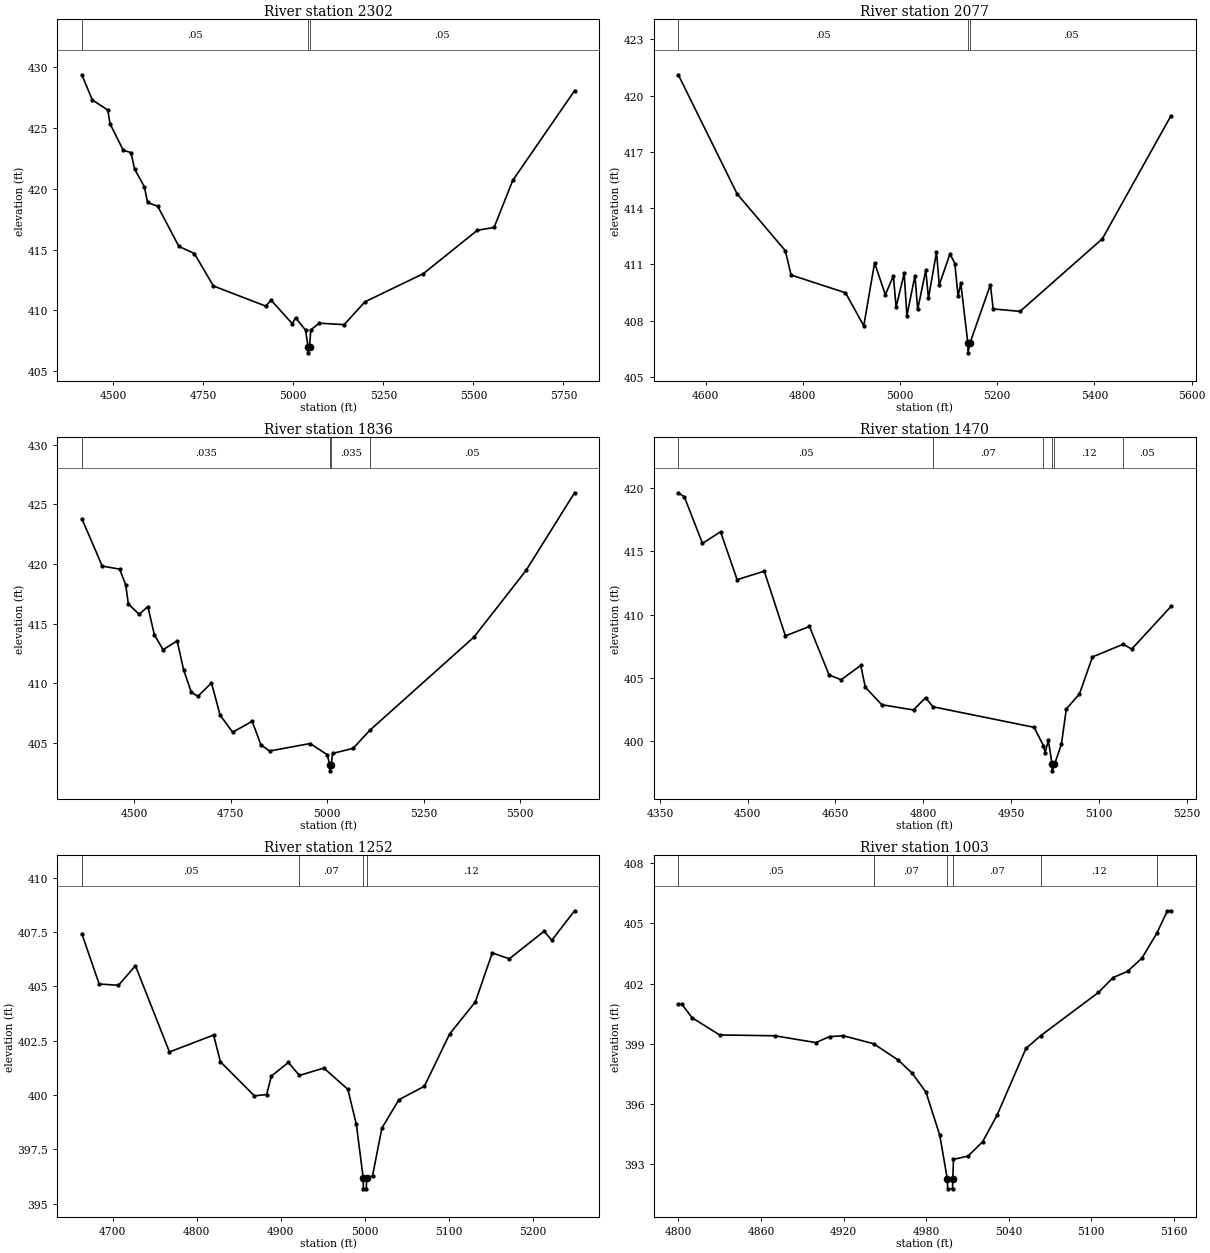
Type RM Length L Ch R = 1,2302,225,225,225
BEGIN DESCRIPTION:
Stream0800 4.0
END DESCRIPTION:
XS GIS Cut Line= 3
      2421467.46     13592216.05      2421979.60     13591916.58
      2422686.75     13591599.88
#Sta/Elev= 30
  4412.7  429.38  4441.7  427.31  4484.6  426.48  4490.9  425.35  4527.6  423.17
  4549.1  422.98  4559.0  421.63  4586.3  420.17  4595.2  418.88  4623.5  418.56
  4682.2  415.26  4725.1  414.68  4778.0  412.01  4922.7  410.36  4938.3  410.83
  4997.0  408.91  5006.0  409.40  5033.8  408.38  5040.9  407.01  5041.2  406.51
  5044.9  407.01  5048.4  408.39  5071.6  408.95  5141.1  408.83  5198.5  410.70
  5360.8  413.02  5510.9  416.59  5557.3  416.82  5609.1  420.69  5780.8  428.07
#Mann=3,-1,0
  4412.7    0.05       0  5040.9    0.05       0  5044.9    0.05       0
Bank Sta=5040.9,5044.9
Exp/Cntr=0.3,0.1

Type RM Length L Ch R = 1,2077,241,241,241
BEGIN DESCRIPTION:
H21077
END DESCRIPTION:
XS GIS Cut Line= 2
      2421659.16     13592323.61      2422560.55     13591860.28
#Sta/Elev= 30
  4544.0  421.11  4665.0  414.76  4764.2  411.73  4775.9  410.44  4887.9  409.49
  4925.5  407.73  4947.7  411.08  4969.9  409.39  4986.4  410.39  4992.0  408.73
  5008.6  410.52  5014.2  408.27  5030.8  410.40  5036.4  408.60  5053.0  410.69
  5058.6  409.21  5075.1  411.66  5080.8  409.91  5102.9  411.57  5112.8  411.05
  5119.5  409.31  5125.1  410.00  5139.7  406.79  5139.9  406.29  5143.7  406.79
  5186.0  409.92  5191.7  408.63  5247.0  408.50  5416.3  412.37  5557.5  418.93
#Mann=3,-1,0
  4544.0    0.05       0  5139.7    0.05       0  5143.7    0.05       0
Bank Sta=5139.7,5143.7
Exp/Cntr=0.3,0.1

Type RM Length L Ch R = 1,1836,366,366,366
BEGIN DESCRIPTION:
XS7743
END DESCRIPTION:
XS GIS Cut Line= 2
      2421662.80     13592563.26      2422811.43     13592004.12
#Sta/Elev= 30
  4363.8  423.80  4416.6  419.83  4461.7  419.57  4477.5  418.26  4484.3  416.65
  4512.4  415.79  4534.9  416.43  4551.9  414.06  4574.4  412.82  4610.9  413.56
  4627.6  411.14  4647.6  409.26  4664.6  408.91  4699.9  410.04  4722.2  407.34
  4754.8  405.91  4805.5  406.82  4828.0  404.85  4850.6  404.33  4955.7  404.96
  5000.2  404.02  5006.4  403.17  5006.6  402.67  5010.4  403.17  5013.9  404.13
  5066.9  404.55  5110.5  406.07  5380.2  413.87  5515.5  419.46  5641.3  425.97
#Mann=4,-1,0
  4363.8   0.035       0  5006.4   0.035       0  5010.4   0.035       0
  5110.5    0.05       0
Bank Sta=5006.4,5010.4
Exp/Cntr=0.3,0.1

Type RM Length L Ch R = 1,1470,218,218,218
BEGIN DESCRIPTION:
Stream0800 3.0
END DESCRIPTION:
XS GIS Cut Line= 3
      2421824.97     13592725.01      2422425.00     13592575.00
      2422625.00     13592475.00
#Sta/Elev= 30
  4381.4  419.60  4391.7  419.28  4422.7  415.61  4453.6  416.53  4481.9  412.75
  4528.3  413.42  4564.4  408.32  4605.6  409.06  4639.1  405.24  4659.7  404.86
  4693.2  405.99  4701.0  404.27  4729.3  402.89  4783.4  402.48  4804.0  403.45
  4816.7  402.73  4989.6  401.11  5005.5  399.66  5008.3  399.12  5013.9  400.08
  5020.3  398.18  5020.5  397.68  5024.3  398.18  5036.2  399.78  5044.6  402.56
  5067.0  403.74  5089.3  406.66  5141.8  407.66  5156.4  407.28  5223.5  410.64
#Mann=6,-1,0
  4381.4    0.05       0  4816.7    0.07       0  5005.5    0.12       0
  5020.3    0.05       0  5024.3    0.12       0  5141.8    0.05       0
Bank Sta=5020.3,5024.3
Exp/Cntr=0.3,0.1

Type RM Length L Ch R = 1,1252,249,249,249
BEGIN DESCRIPTION:
H21076
END DESCRIPTION:
XS GIS Cut Line= 2
      2422091.90     13592843.51      2422671.81     13592753.86
#Sta/Elev= 30
  4663.1  407.42  4683.7  405.11  4706.7  405.05  4726.9  405.95  4767.4  401.98
  4820.0  402.76  4828.1  401.53  4868.6  399.96  4883.1  400.02  4888.8  400.87
  4909.1  401.50  4922.1  400.90  4951.3  401.24  4979.9  400.26  4990.0  398.65
  4998.2  396.18  4998.4  395.68  5001.9  395.68  5002.2  396.18  5009.3  396.28
  5020.4  398.47  5040.6  399.78  5071.0  400.40  5101.3  402.82  5131.7  404.28
  5151.9  406.54  5172.2  406.27  5213.7  407.54  5222.8  407.12  5249.9  408.48
#Mann=4,-1,0
  4663.1    0.05       0  4922.1    0.07       0  4998.2    0.05       0
  5002.2    0.12       0
Bank Sta=4998.2,5002.2
Exp/Cntr=0.3,0.1

Type RM Length L Ch R = 1,1003,155,155,155
BEGIN DESCRIPTION:
Stream0800 2.0
END DESCRIPTION:
XS GIS Cut Line= 3
      2422275.00     13593025.00      2422475.00     13593025.00
      2422624.99     13592975.00
#Sta/Elev= 30
  4799.9  400.98  4802.4  400.98  4809.9  400.30  4829.9  399.44  4869.9  399.40
  4899.9  399.06  4909.9  399.36  4919.9  399.40  4941.9  399.00  4959.9  398.18
  4969.9  397.53  4979.9  396.59  4989.9  394.45  4995.4  392.27  4995.7  391.77
  4999.2  391.77  4999.4  392.27  4999.9  393.24  5010.4  393.40  5021.0  394.11
  5031.5  395.43  5052.6  398.77  5063.2  399.40  5105.3  401.56  5115.9  402.30
  5126.4  402.61  5136.9  403.27  5147.6  404.50  5155.4  405.63  5158.0  405.63
#Mann=6,-1,0
  4799.9    0.05       0  4941.9    0.07       0  4995.4    0.05       0
  4999.4    0.07       0  5063.2    0.12       0  5147.6    0.07       0
Bank Sta=4995.4,4999.4
Exp/Cntr=0.3,0.1

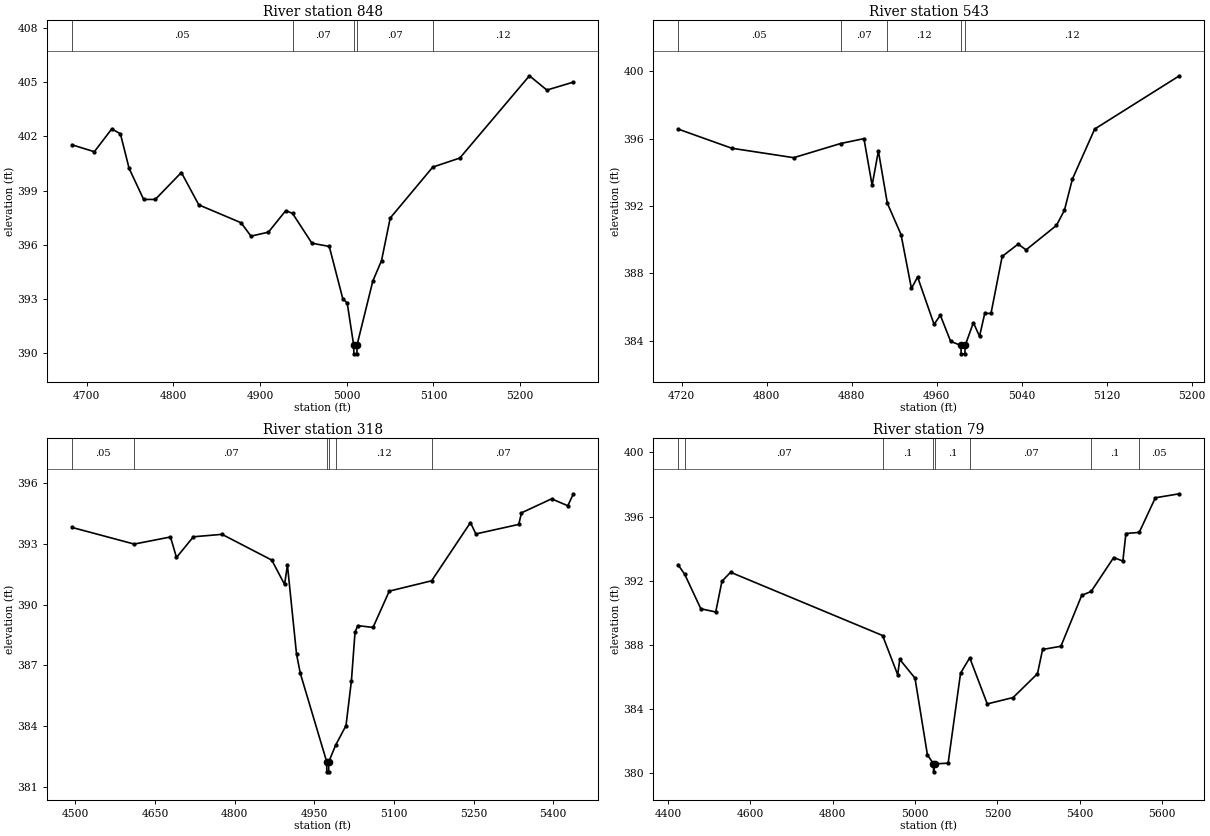
Type RM Length L Ch R = 1,848,305,305,305
BEGIN DESCRIPTION:
H21075
END DESCRIPTION:
XS GIS Cut Line= 2
      2422159.41     13593152.63      2422735.49     13593203.21
#Sta/Elev= 30
  4683.2  401.53  4708.9  401.15  4729.0  402.41  4739.0  402.14  4749.0  400.23
  4765.8  398.51  4779.2  398.51  4809.3  400.00  4829.4  398.21  4878.2  397.22
  4889.6  396.48  4909.7  396.70  4929.7  397.89  4937.5  397.74  4959.9  396.09
  4979.9  395.91  4995.5  393.02  5000.6  392.78  5008.0  390.47  5008.3  389.97
  5011.8  389.97  5012.0  390.47  5030.1  393.99  5040.2  395.13  5050.2  397.48
  5099.3  400.30  5130.5  400.80  5210.8  405.35  5230.9  404.56  5261.5  405.00
#Mann=5,-1,0
  4683.2    0.05       0  4937.5    0.07       0  5008.0    0.05       0
  5012.0    0.07       0  5099.3    0.12       0
Bank Sta=5008,5012
Exp/Cntr=0.3,0.1

Type RM Length L Ch R = 1,543,225,225,225
BEGIN DESCRIPTION:
Stream0800 1.0
END DESCRIPTION:
XS GIS Cut Line= 3
      2422274.97     13593324.98      2422525.00     13593475.00
      2422675.04     13593374.98
#Sta/Elev= 30
  4716.5  396.57  4767.1  395.43  4825.4  394.87  4869.5  395.71  4891.5  396.00
  4899.2  393.23  4905.1  395.27  4913.5  392.17  4926.4  390.31  4936.2  387.11
  4942.0  387.79  4957.5  384.98  4963.4  385.52  4973.1  383.97  4982.8  383.73
  4983.0  383.23  4986.5  383.23  4986.8  383.73  4994.5  385.08  5000.3  384.27
  5005.2  385.63  5011.1  385.63  5021.6  389.01  5036.6  389.74  5044.1  389.40
  5072.7  390.85  5080.2  391.75  5087.7  393.60  5108.7  396.57  5188.4  399.73
#Mann=5,-1,0
  4716.5    0.05       0  4869.5    0.07       0  4913.5    0.12       0
  4982.8    0.05       0  4986.8    0.12       0
Bank Sta=4982.8,4986.8
Exp/Cntr=0.3,0.1

Type RM Length L Ch R = 1,318,239,239,239
BEGIN DESCRIPTION:
H21074
END DESCRIPTION:
XS GIS Cut Line= 3
      2422103.16     13593517.95      2422519.08     13593686.57
      2423005.28     13593591.02
#Sta/Elev= 30
  4493.7  393.80  4610.8  392.98  4679.1  393.33  4690.4  392.32  4722.3  393.34
  4776.2  393.46  4869.9  392.19  4894.0  390.99  4899.4  391.94  4916.5  387.56
  4923.5  386.62  4973.3  382.25  4973.5  381.75  4977.0  381.75  4977.3  382.25
  4990.1  383.06  5009.7  384.03  5019.9  386.24  5026.7  388.63  5031.8  388.96
  5060.6  388.87  5091.2  390.66  5171.0  391.17  5244.1  394.04  5254.3  393.48
  5335.1  393.95  5340.2  394.52  5396.9  395.21  5427.5  394.87  5438.0  395.46
#Mann=6,-1,0
  4493.7    0.05       0  4610.8    0.07       0  4973.3    0.05       0
  4977.3    0.07       0  4990.1    0.12       0  5171.0    0.07       0
Bank Sta=4973.3,4977.3
Exp/Cntr=0.3,0.1

Type RM Length L Ch R = 1,79,0,0,0
BEGIN DESCRIPTION:
XS7744
END DESCRIPTION:
XS GIS Cut Line= 4
      2422131.54     13593631.01      2422548.18     13593904.43
      2422773.87     13593878.39      2423177.52     13593596.26
#Sta/Elev= 30
  4424.3  392.99  4440.4  392.40  4479.7  390.24  4515.9  390.04  4531.0  391.96
  4552.0  392.52  4921.3  388.57  4958.0  386.12  4963.0  387.08  5000.0  385.91
  5030.2  381.12  5044.9  380.56  5045.1  380.06  5048.9  380.56  5080.5  380.60
  5110.7  386.22  5133.0  387.18  5175.6  384.30  5238.5  384.70  5297.6  386.19
  5310.0  387.70  5354.5  387.90  5405.1  391.08  5428.0  391.32  5482.7  393.44
  5505.0  393.22  5512.4  394.94  5544.8  395.01  5583.9  397.17  5642.3  397.42
#Mann=8,-1,0
  4424.3    0.05       0  4440.4    0.07       0  4921.3     0.1       0
  5044.9    0.05       0  5048.9     0.1       0  5133.0    0.07       0
  5428.0     0.1       0  5544.8    0.05       0
Bank Sta=5044.9,5048.9
Exp/Cntr=0.3,0.1

Chan Stop Cuts=-1