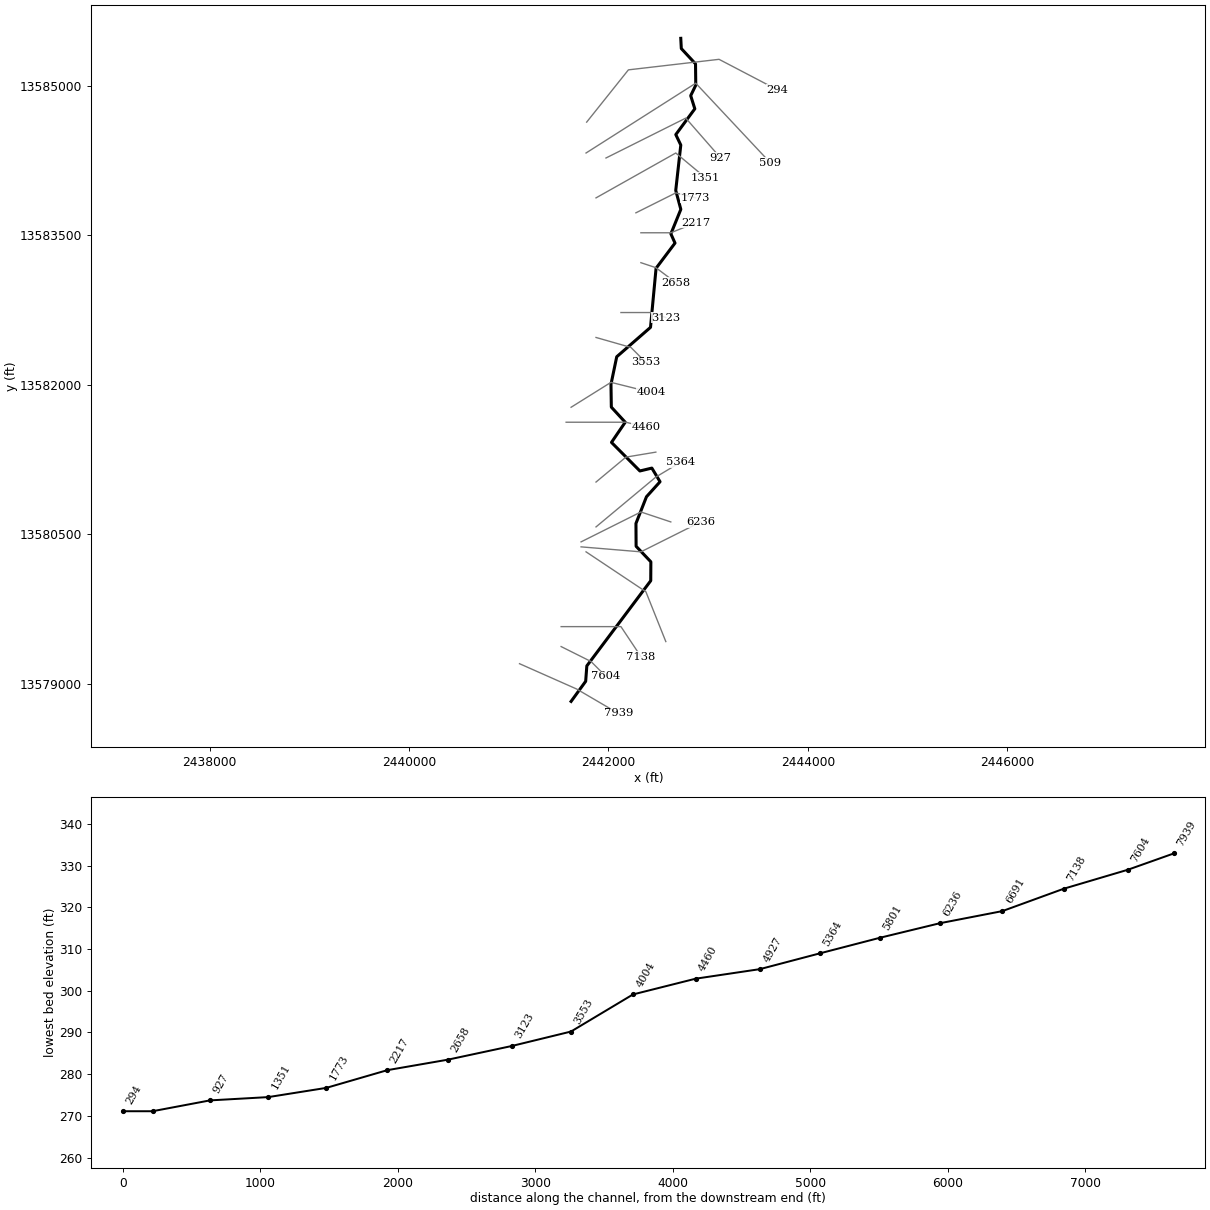
--- Stream0801.prj (project) ---

Proj Title=Stream0801 Base Level Engineering
Current Plan=p01
Default Exp/Contr=0.3,0.1
English Units
Geom File=g01
Flow File=f01
Plan File=p01
BEGIN DESCRIPTION:
Stream0801
END DESCRIPTION:

--- Stream0801.p01 (plan) ---

Plan Title=Multiple Run
Short Identifier=Multiple
Geom File=g01
Flow File=f01
Subcritical Flow
K Sum by GR= 0
Std Step Tol= 0.01
Critical Tol= 0.01
Num of Std Step Trials= 20
Max Error Tol= 0.3
Flow Tol Ratio= 0.001
Split Flow NTrial= 30
Split Flow Tol= 0.02
Split Flow Ratio= 0.02
Log Output Level= 0
Friction Slope Method= 1
Unsteady Friction Slope Method= 2
Unsteady Bridges Friction Slope Method= 1
Parabolic Critical Depth
Global Vel Dist=  1 , 1 , 1
Global Log Level= 0
CheckData=True
Encroach Param= -1, 0, 0, 0
BEGIN DESCRIPTION:
Multiple Run
END DESCRIPTION:

--- Stream0801.f01 (steady flow) ---

Flow Title=Multiple
Number of Profiles=7
Profile Names=10-year,25-year,50-year,1pct_min,100-year,1pct_plu,500-year
River Rch & RM= Stream0801,Reach-1,7939
     369     580     767     492     983    1960    1595
River Rch & RM= Stream0801,Reach-1,6236
     737    1212    1649    1087    2169    4328    3719
River Rch & RM= Stream0801,Reach-1,3553
     849    1403    1915    1266    2526    5040    4354
Boundary for River Rch & Prof#=Stream0801,Reach-1,1
Up Type=0
Dn Type=3
Dn Slope=0.005
Boundary for River Rch & Prof#=Stream0801,Reach-1,2
Up Type=0
Dn Type=3
Dn Slope=0.005
Boundary for River Rch & Prof#=Stream0801,Reach-1,3
Up Type=0
Dn Type=3
Dn Slope=0.005
Boundary for River Rch & Prof#=Stream0801,Reach-1,4
Up Type=0
Dn Type=3
Dn Slope=0.005
Boundary for River Rch & Prof#=Stream0801,Reach-1,5
Up Type=0
Dn Type=3
Dn Slope=0.005
Boundary for River Rch & Prof#=Stream0801,Reach-1,6
Up Type=0
Dn Type=3
Dn Slope=0.005
Boundary for River Rch & Prof#=Stream0801,Reach-1,7
Up Type=0
Dn Type=3
Dn Slope=0.005

--- Stream0801.g01 (geometry) ---

Geom Title=Existing Conditions

River Reach=Stream0801,Reach-1
Reach XY= 30
      2441625.00     13578825.00      2441771.24     13579026.56
      2441782.83     13579181.18      2442423.81     13580035.49
      2442425.00     13580225.00      2442277.05     13580380.85
      2442275.52     13580609.78      2442380.83     13580877.30
      2442517.17     13581028.23      2442435.00     13581164.93
      2442314.95     13581136.11      2442030.06     13581422.71
      2442167.93     13581625.00      2442028.54     13581776.46
      2442025.07     13582004.97      2442082.69     13582281.48
      2442421.46     13582576.47      2442477.24     13583169.07
      2442667.18     13583421.59      2442625.82     13583514.29
      2442725.47     13583759.84      2442674.60     13583950.00
      2442725.20     13584404.80      2442675.08     13584509.61
      2442865.87     13584768.26      2442824.61     13584900.00
      2442875.36     13585004.85      2442872.94     13585219.15
      2442730.35     13585372.50      2442725.00     13585475.00

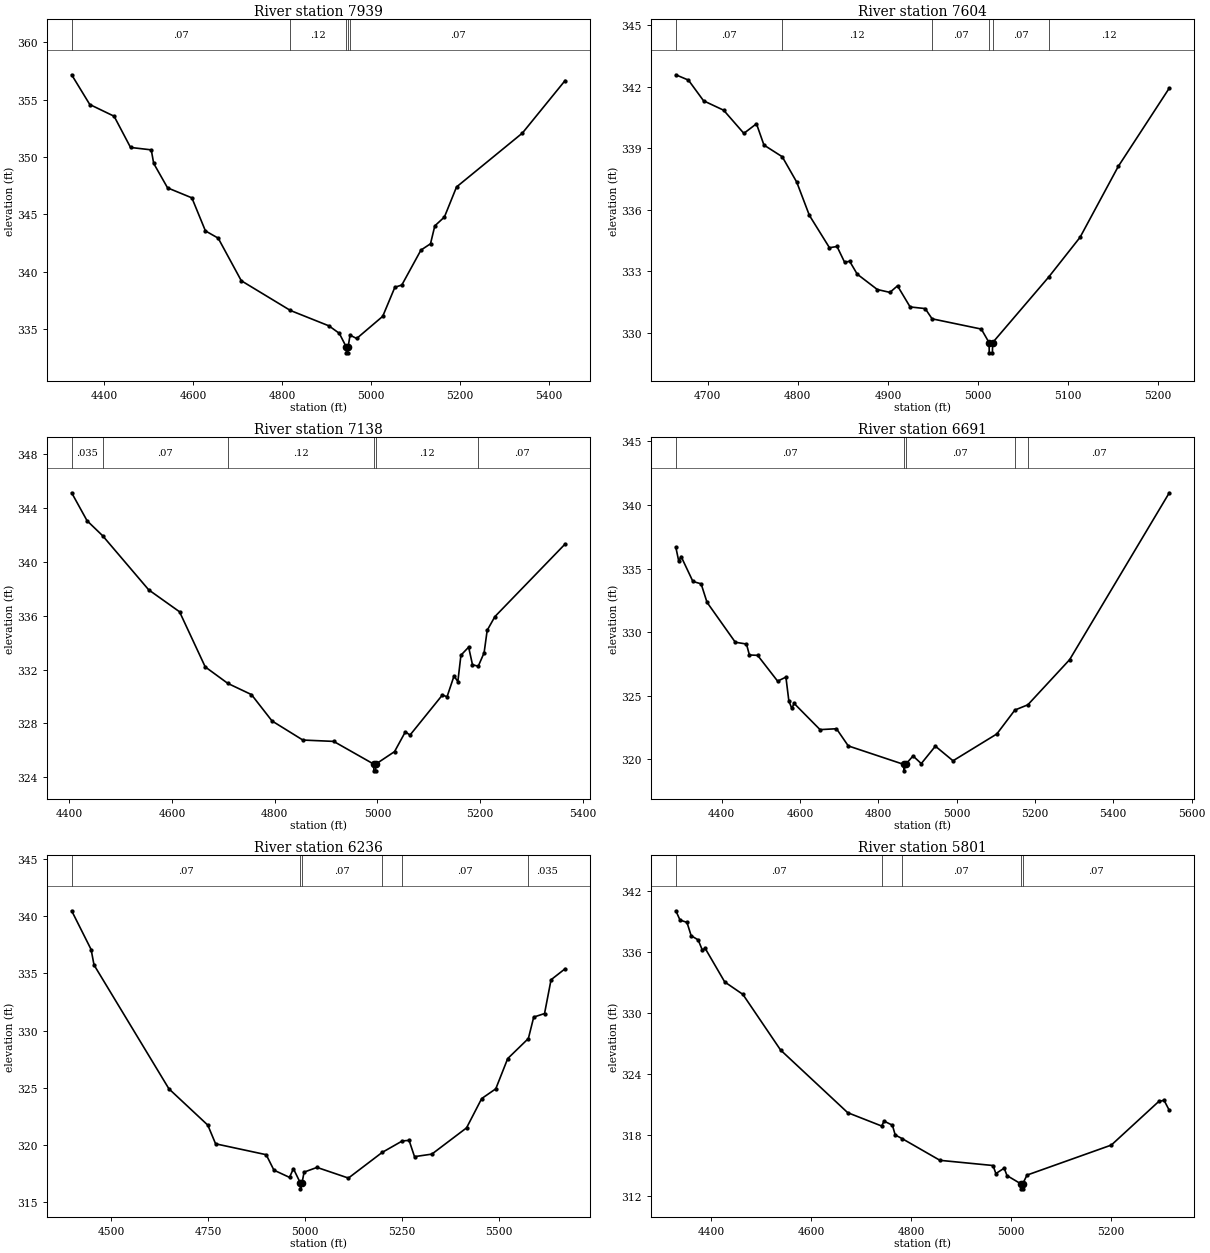
Type RM Length L Ch R = 1,7939,335,335,335
BEGIN DESCRIPTION:
XS7746
END DESCRIPTION:
XS GIS Cut Line= 3
      2441107.73     13579203.22      2441680.28     13578949.44
      2442098.03     13578704.98
#Sta/Elev= 30
  4326.9  357.16  4367.7  354.57  4422.4  353.55  4459.4  350.83  4506.0  350.62
  4511.5  349.44  4542.7  347.31  4597.4  346.44  4627.9  343.56  4656.6  342.93
  4708.6  339.22  4819.1  336.63  4905.8  335.29  4929.1  334.64  4944.9  333.44
  4945.1  332.94  4948.6  332.94  4948.9  333.44  4953.3  334.48  4968.2  334.19
  5026.8  336.12  5054.1  338.65  5069.8  338.85  5112.8  341.89  5134.3  342.44
  5144.0  344.00  5165.6  344.77  5192.9  347.39  5341.0  352.08  5437.2  356.66
#Mann=5,-1,0
  4326.9    0.07       0  4819.1    0.12       0  4944.9    0.05       0
  4948.9    0.12       0  4953.3    0.07       0
Bank Sta=4944.9,4948.9
Exp/Cntr=0.3,0.1

Type RM Length L Ch R = 1,7604,466,466,466
BEGIN DESCRIPTION:
Stream0801 17.0
END DESCRIPTION:
XS GIS Cut Line= 3
      2441524.98     13579375.01      2441825.00     13579225.00
      2441975.03     13579074.97
#Sta/Elev= 30
  4664.6  342.59  4678.6  342.33  4695.4  341.32  4717.7  340.86  4740.1  339.73
  4754.1  340.20  4762.4  339.16  4782.7  338.59  4798.8  337.35  4812.8  335.73
  4835.1  334.15  4843.5  334.21  4851.9  333.44  4857.5  333.49  4865.9  332.86
  4888.2  332.11  4902.2  331.97  4910.6  332.29  4924.6  331.26  4941.3  331.18
  4949.0  330.68  5003.6  330.18  5012.2  329.52  5012.4  329.02  5015.9  329.02
  5016.2  329.52  5078.4  332.72  5113.2  334.66  5155.6  338.12  5212.2  341.94
#Mann=6,-1,0
  4664.6    0.07       0  4782.7    0.12       0  4949.0    0.07       0
  5012.2    0.05       0  5016.2    0.07       0  5078.4    0.12       0
Bank Sta=5012.2,5016.2
Exp/Cntr=0.3,0.1

Type RM Length L Ch R = 1,7138,447,447,447
BEGIN DESCRIPTION:
Stream0801 16.0
END DESCRIPTION:
XS GIS Cut Line= 3
      2441525.04     13579575.00      2442125.00     13579575.00
      2442324.99     13579275.01
#Sta/Elev= 30
  4404.8  345.15  4434.8  343.07  4465.0  341.96  4554.8  337.93  4614.8  336.30
  4664.8  332.20  4708.9  330.97  4754.8  330.14  4794.8  328.18  4854.8  326.76
  4914.8  326.66  4992.8  324.97  4993.0  324.47  4996.5  324.47  4996.8  324.97
  5033.3  325.90  5054.3  327.37  5063.4  327.13  5126.4  330.11  5135.5  329.98
  5149.0  331.52  5156.5  331.11  5162.5  333.07  5177.5  333.67  5185.0  332.36
  5196.2  332.25  5207.6  333.25  5213.6  334.92  5228.6  335.94  5365.3  341.34
#Mann=6,-1,0
  4404.8   0.035       0  4465.0    0.07       0  4708.9    0.12       0
  4992.8    0.05       0  4996.8    0.12       0  5196.2    0.07       0
Bank Sta=4992.8,4996.8
Exp/Cntr=0.3,0.1

Type RM Length L Ch R = 1,6691,455,455,455
BEGIN DESCRIPTION:
Stream0801 15.0
END DESCRIPTION:
XS GIS Cut Line= 3
      2441774.98     13580325.01      2442375.00     13579925.00
      2442574.98     13579425.04
#Sta/Elev= 30
  4283.3  336.68  4290.8  335.58  4296.8  335.95  4326.9  333.99  4347.9  333.80
  4362.9  332.35  4435.1  329.21  4463.6  329.07  4471.1  328.21  4492.1  328.18
  4543.2  326.15  4564.3  326.47  4571.8  324.60  4579.3  324.01  4585.3  324.40
  4651.4  322.34  4693.4  322.41  4723.5  321.06  4865.7  319.60  4866.0  319.10
  4869.7  319.60  4888.8  320.27  4909.8  319.67  4945.8  321.04  4990.9  319.89
  5102.7  322.00  5148.8  323.88  5181.8  324.29  5288.5  327.84  5542.9  340.96
#Mann=5,-1,0
  4283.3    0.07       0  4865.7    0.05       0  4869.7    0.07       0
  5148.8    0.12       0  5181.8    0.07       0
Bank Sta=4865.7,4869.7
Exp/Cntr=0.3,0.1

Type RM Length L Ch R = 1,6236,435,435,435
BEGIN DESCRIPTION:
Stream0801 14.0
END DESCRIPTION:
XS GIS Cut Line= 3
      2441724.97     13580375.00      2442325.00     13580325.00
      2442924.97     13580624.99
#Sta/Elev= 30
  4398.3  340.46  4448.5  337.08  4456.0  335.73  4649.2  324.92  4749.5  321.75
  4769.6  320.12  4900.1  319.17  4920.1  317.82  4960.3  317.19  4970.3  317.95
  4988.4  316.69  4988.6  316.19  4992.4  316.69  4997.9  317.65  5031.2  318.06
  5112.2  317.13  5199.3  319.37  5251.2  320.37  5268.7  320.42  5282.7  319.00
  5327.4  319.22  5416.9  321.51  5456.0  324.07  5492.3  324.92  5523.1  327.56
  5576.4  329.31  5590.2  331.18  5618.1  331.49  5634.9  334.44  5671.2  335.40
#Mann=6,-1,0
  4398.3    0.07       0  4988.4    0.05       0  4992.4    0.07       0
  5199.3   0.035       0  5251.2    0.07       0  5576.4   0.035       0
Bank Sta=4988.4,4992.4
Exp/Cntr=0.3,0.1

Type RM Length L Ch R = 1,5801,437,437,437
BEGIN DESCRIPTION:
Stream0801 13.0
END DESCRIPTION:
XS GIS Cut Line= 3
      2441725.01     13580425.01      2442325.00     13580725.00
      2442624.97     13580625.01
#Sta/Elev= 30
  4329.2  340.02  4337.6  339.11  4351.5  338.88  4359.9  337.57  4373.9  337.16
  4382.3  336.15  4387.9  336.33  4427.0  333.03  4463.3  331.81  4538.8  326.34
  4673.0  320.19  4740.9  318.88  4745.7  319.36  4762.4  318.96  4768.0  318.00
  4781.6  317.65  4857.5  315.51  4963.7  315.00  4969.3  314.21  4986.0  314.74
  4991.6  314.01  5019.1  313.21  5019.3  312.71  5022.8  312.71  5023.1  313.21
  5031.6  314.06  5200.3  317.01  5295.1  321.29  5305.7  321.41  5316.2  320.42
#Mann=5,-1,0
  4329.2    0.07       0  4740.9   0.035       0  4781.6    0.07       0
  5019.1    0.05       0  5023.1    0.07       0
Bank Sta=5019.1,5023.1
Exp/Cntr=0.3,0.1

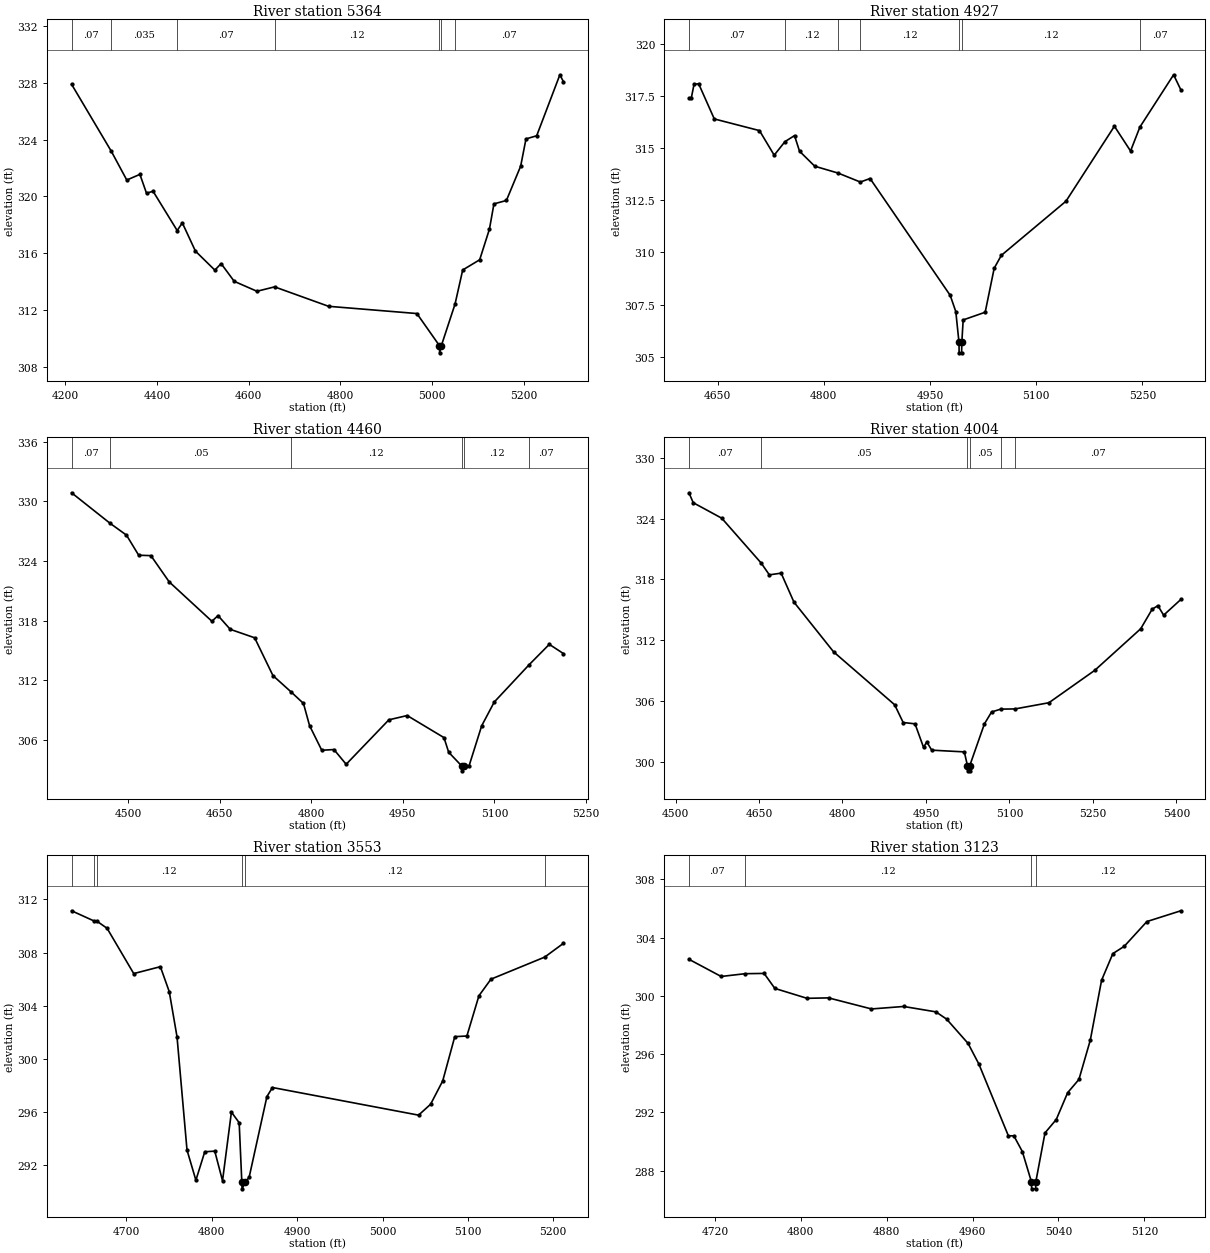
Type RM Length L Ch R = 1,5364,437,437,437
BEGIN DESCRIPTION:
Stream0801 12.0
END DESCRIPTION:
XS GIS Cut Line= 3
      2441875.01     13580575.01      2442475.00     13581075.00
      2442725.03     13581225.02
#Sta/Elev= 30
  4214.1  327.90  4300.7  323.18  4334.5  321.15  4363.1  321.55  4377.5  320.22
  4391.8  320.36  4444.4  317.59  4455.6  318.13  4484.2  316.14  4526.5  314.80
  4540.2  315.26  4568.8  314.01  4618.3  313.31  4656.8  313.62  4774.5  312.25
  4967.1  311.74  5016.4  309.47  5016.7  308.97  5020.4  309.47  5050.3  312.41
  5067.0  314.81  5104.0  315.53  5125.3  317.69  5135.1  319.47  5162.3  319.71
  5193.4  322.13  5205.0  324.05  5228.3  324.27  5278.9  328.57  5286.7  328.08
#Mann=7,-1,0
  4214.1    0.07       0  4300.7   0.035       0  4444.4    0.07       0
  4656.8    0.12       0  5016.4    0.05       0  5020.4    0.12       0
  5050.3    0.07       0
Bank Sta=5016.4,5020.4
Exp/Cntr=0.3,0.1

Type RM Length L Ch R = 1,4927,467,467,467
BEGIN DESCRIPTION:
Stream0801 11.0
END DESCRIPTION:
XS GIS Cut Line= 3
      2441874.99     13581024.99      2442175.00     13581275.00
      2442475.04     13581325.01
#Sta/Elev= 30
  4609.5  317.41  4612.8  317.41  4616.7  318.07  4623.2  318.10  4645.3  316.41
  4709.1  315.85  4729.9  314.67  4745.1  315.32  4758.6  315.61  4765.7  314.86
  4787.2  314.14  4820.2  313.81  4851.6  313.38  4865.3  313.55  4978.5  307.94
  4986.4  307.16  4990.9  305.68  4991.1  305.18  4994.6  305.18  4994.9  305.68
  4996.8  306.76  5027.9  307.13  5040.6  309.24  5050.7  309.86  5142.0  312.46
  5210.4  316.06  5233.2  314.87  5246.4  316.02  5294.0  318.53  5304.2  317.81
#Mann=7,-1,0
  4609.5    0.07       0  4745.1    0.12       0  4820.2    0.07       0
  4851.6    0.12       0  4990.9    0.05       0  4994.9    0.12       0
  5246.4    0.07       0
Bank Sta=4990.9,4994.9
Exp/Cntr=0.3,0.1

Type RM Length L Ch R = 1,4460,456,456,456
BEGIN DESCRIPTION:
Stream0801 10.0
END DESCRIPTION:
XS GIS Cut Line= 3
      2441575.03     13581625.00      2442175.00     13581625.00
      2442374.97     13581575.01
#Sta/Elev= 30
  4407.1  330.85  4470.4  327.77  4497.1  326.59  4517.1  324.57  4537.1  324.53
  4567.1  321.89  4637.1  317.93  4647.1  318.50  4667.1  317.12  4707.1  316.27
  4737.1  312.47  4766.2  310.86  4787.1  309.67  4797.1  307.44  4817.1  304.96
  4837.1  305.03  4857.1  303.55  4927.1  308.02  4957.1  308.45  5017.4  306.23
  5025.1  304.76  5046.3  303.39  5046.6  302.89  5050.3  303.39  5058.6  303.41
  5079.2  307.42  5099.8  309.81  5156.8  313.55  5190.0  315.61  5213.2  314.68
#Mann=6,-1,0
  4407.1    0.07       0  4470.4    0.05       0  4766.2    0.12       0
  5046.3    0.05       0  5050.3    0.12       0  5156.8    0.07       0
Bank Sta=5046.3,5050.3
Exp/Cntr=0.3,0.1

Type RM Length L Ch R = 1,4004,451,451,451
BEGIN DESCRIPTION:
Stream0801 9.0
END DESCRIPTION:
XS GIS Cut Line= 3
      2441624.99     13581774.99      2442025.00     13582025.00
      2442424.97     13581925.01
#Sta/Elev= 30
  4524.1  326.55  4531.8  325.57  4583.1  324.04  4654.0  319.61  4668.6  318.45
  4689.8  318.62  4712.8  315.76  4784.1  310.85  4893.8  305.63  4909.1  303.88
  4930.4  303.75  4945.7  301.43  4951.6  301.96  4960.4  301.15  5019.0  300.98
  5024.7  299.61  5025.0  299.11  5028.5  299.11  5028.7  299.61  5055.1  303.74
  5068.0  304.92  5084.5  305.20  5110.2  305.22  5171.0  305.83  5253.5  309.03
  5336.0  313.13  5356.6  315.06  5366.9  315.41  5377.2  314.47  5408.1  316.02
#Mann=6,-1,0
  4524.1    0.07       0  4654.0    0.05       0  5024.7    0.05       0
  5028.7    0.05       0  5084.5    0.12       0  5110.2    0.07       0
Bank Sta=5024.7,5028.7
Exp/Cntr=0.3,0.1

Type RM Length L Ch R = 1,3553,430,430,430
BEGIN DESCRIPTION:
Stream0801 8.0
END DESCRIPTION:
XS GIS Cut Line= 3
      2441875.04     13582474.99      2442225.00     13582375.00
      2442375.00     13582225.00
#Sta/Elev= 30
  4635.8  311.15  4662.2  310.38  4665.4  310.37  4677.4  309.83  4708.6  306.42
  4739.8  306.94  4750.2  305.06  4759.3  301.66  4771.0  293.13  4781.4  290.86
  4791.8  293.00  4803.5  293.05  4812.6  290.82  4823.0  295.99  4832.1  295.19
  4835.2  290.71  4835.5  290.21  4839.3  290.71  4843.8  291.09  4864.6  297.16
  4871.1  297.84  5042.2  295.76  5056.3  296.58  5070.5  298.34  5084.6  301.67
  5098.8  301.72  5112.9  304.75  5127.0  306.00  5189.9  307.66  5211.9  308.70
#Mann=6,-1,0
  4635.8    0.05       0  4662.2    0.07       0  4665.4    0.12       0
  4835.2    0.05       0  4839.3    0.12       0  5189.9    0.07       0
Bank Sta=4835.2,4839.3
Exp/Cntr=0.3,0.1

Type RM Length L Ch R = 1,3123,465,465,465
BEGIN DESCRIPTION:
Stream0801 7.0
END DESCRIPTION:
XS GIS Cut Line= 3
      2442125.03     13582725.00      2442425.00     13582725.00
      2442575.02     13582674.99
#Sta/Elev= 30
  4695.9  302.51  4725.9  301.33  4748.2  301.52  4765.9  301.54  4775.9  300.51
  4805.9  299.83  4825.9  299.86  4865.9  299.10  4895.9  299.27  4925.9  298.90
  4935.9  298.40  4955.9  296.73  4965.9  295.32  4993.4  290.39  4998.5  290.39
  5006.4  289.31  5014.8  287.25  5015.1  286.75  5018.7  286.75  5019.0  287.25
  5027.5  290.59  5038.0  291.51  5048.6  293.35  5059.1  294.26  5069.7  296.96
  5080.2  301.07  5090.7  302.90  5101.3  303.40  5122.4  305.10  5154.0  305.84
#Mann=4,-1,0
  4695.9    0.07       0  4748.2    0.12       0  5014.8    0.05       0
  5019.0    0.12       0
Bank Sta=5014.8,5019
Exp/Cntr=0.3,0.1

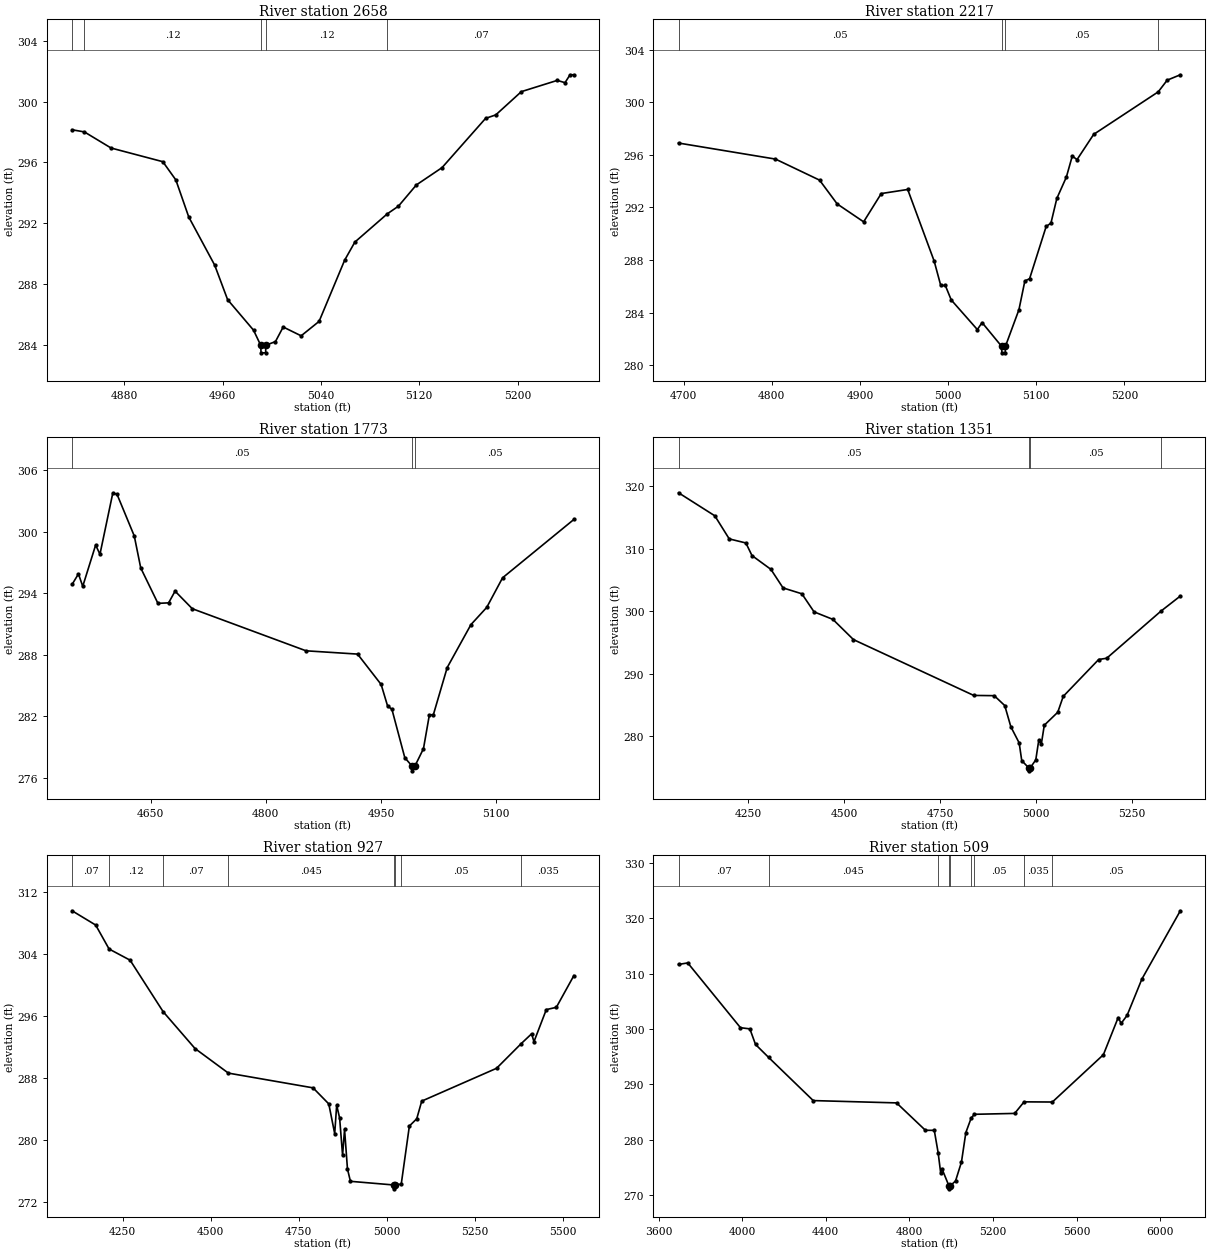
Type RM Length L Ch R = 1,2658,441,441,441
BEGIN DESCRIPTION:
Stream0801 6.0
END DESCRIPTION:
XS GIS Cut Line= 3
      2442324.97     13583225.01      2442475.00     13583175.00
      2442674.96     13583025.03
#Sta/Elev= 30
  4837.6  298.15  4847.6  298.01  4869.3  296.95  4911.4  296.05  4922.0  294.85
  4932.5  292.41  4953.6  289.24  4964.1  286.97  4985.2  284.96  4991.0  283.97
  4991.3  283.47  4995.0  283.47  4995.2  283.97  5003.0  284.21  5009.3  285.17
  5023.9  284.59  5038.5  285.54  5059.3  289.57  5067.6  290.76  5094.0  292.62
  5103.0  293.12  5117.6  294.52  5138.5  295.66  5173.9  298.90  5182.2  299.13
  5203.0  300.66  5232.2  301.40  5238.5  301.25  5242.6  301.77  5245.7  301.77
#Mann=5,-1,0
  4837.6    0.07       0  4847.6    0.12       0  4991.0    0.05       0
  4995.2    0.12       0  5094.0    0.07       0
Bank Sta=4991,4995.2
Exp/Cntr=0.3,0.1

Type RM Length L Ch R = 1,2217,444,444,444
BEGIN DESCRIPTION:
Stream0801 5.0
END DESCRIPTION:
XS GIS Cut Line= 3
      2442325.01     13583525.00      2442625.00     13583525.00
      2442875.04     13583625.02
#Sta/Elev= 30
  4694.2  296.90  4804.2  295.68  4854.2  294.08  4874.2  292.27  4904.2  290.91
  4924.2  293.06  4954.2  293.37  4984.2  287.93  4991.7  286.07  4996.9  286.07
  5003.6  284.97  5033.2  282.72  5038.6  283.25  5060.7  281.45  5061.0  280.95
  5064.8  280.95  5065.1  281.45  5080.4  284.23  5087.1  286.41  5092.5  286.59
  5111.3  290.56  5116.7  290.81  5123.4  292.69  5134.2  294.31  5140.9  295.91
  5146.3  295.64  5165.2  297.56  5238.4  300.79  5248.6  301.68  5263.5  302.09
#Mann=4,-1,0
  4694.2    0.05       0  5060.7    0.05       0  5065.1    0.05       0
  5238.4   0.035       0
Bank Sta=5060.7,5065.1
Exp/Cntr=0.3,0.1

Type RM Length L Ch R = 1,1773,422,422,422
BEGIN DESCRIPTION:
Stream0801 4.0
END DESCRIPTION:
XS GIS Cut Line= 3
      2442275.04     13583725.02      2442675.00     13583925.00
      2442874.98     13583875.00
#Sta/Elev= 30
  4547.8  294.85  4556.1  295.88  4561.7  294.67  4578.5  298.69  4584.1  297.79
  4600.9  303.78  4606.4  303.62  4628.8  299.57  4637.2  296.46  4659.6  293.01
  4673.5  293.06  4681.9  294.20  4704.3  292.49  4852.4  288.39  4919.5  288.07
  4950.2  285.11  4958.6  283.01  4964.2  282.70  4981.0  277.98  4990.0  277.20
  4990.3  276.70  4994.4  277.20  5005.3  278.86  5013.0  282.15  5018.2  282.17
  5036.2  286.76  5067.1  290.94  5087.7  292.62  5108.3  295.50  5201.1  301.18
#Mann=3,-1,0
  4547.8    0.05       0  4990.0    0.05       0  4994.4    0.05       0
Bank Sta=4990,4994.4
Exp/Cntr=0.3,0.1

Type RM Length L Ch R = 1,1351,424,424,424
BEGIN DESCRIPTION:
Stream0801 3.0
END DESCRIPTION:
XS GIS Cut Line= 3
      2441875.02     13583875.01      2442675.00     13584325.00
      2442975.02     13584074.98
#Sta/Elev= 30
  4067.7  318.92  4162.3  315.24  4199.9  311.55  4243.3  310.90  4259.2  308.89
  4308.6  306.68  4340.2  303.72  4389.3  302.78  4421.1  299.89  4470.2  298.69
  4523.8  295.46  4837.4  286.54  4890.9  286.50  4918.3  284.92  4934.2  281.53
  4955.9  278.95  4962.6  276.13  4980.4  274.99  4980.7  274.49  4984.9  274.99
  4999.2  276.24  5007.0  279.39  5013.5  278.71  5021.4  281.78  5056.5  283.85
  5070.8  286.39  5163.2  292.28  5184.1  292.48  5325.4  300.00  5376.1  302.42
#Mann=4,-1,0
  4067.7    0.05       0  4980.4    0.05       0  4984.9    0.05       0
  5325.4   0.035       0
Bank Sta=4980.4,4984.9
Exp/Cntr=0.3,0.1

Type RM Length L Ch R = 1,927,418,418,418
BEGIN DESCRIPTION:
Stream0801 2.0
END DESCRIPTION:
XS GIS Cut Line= 3
      2441974.99     13584274.99      2442775.00     13584675.00
      2443124.97     13584275.04
#Sta/Elev= 30
  4106.2  309.55  4173.3  307.71  4211.4  304.62  4271.1  303.18  4365.0  296.54
  4455.6  291.79  4550.4  288.62  4791.0  286.72  4835.7  284.65  4852.5  280.82
  4858.1  284.48  4866.5  282.83  4874.9  278.03  4880.5  281.36  4888.8  276.25
  4897.2  274.67  5019.7  274.20  5020.0  273.70  5024.2  274.20  5041.6  274.31
  5064.7  281.80  5085.6  282.73  5099.8  285.01  5312.4  289.24  5382.4  292.42
  5412.1  293.69  5418.7  292.67  5453.8  296.81  5482.3  297.10  5532.1  301.19
#Mann=8,-1,0
  4106.2    0.07       0  4211.4    0.12       0  4365.0    0.07       0
  4550.4   0.045       0  5019.7   0.045       0  5024.2   0.045       0
  5041.6    0.05       0  5382.4   0.035       0
Bank Sta=5019.7,5024.2
Exp/Cntr=0.3,0.1

Type RM Length L Ch R = 1,509,215,215,215
BEGIN DESCRIPTION:
Stream0801 1.0
END DESCRIPTION:
XS GIS Cut Line= 3
      2441775.03     13584325.02      2442875.00     13585025.00
      2443625.01     13584224.99
#Sta/Elev= 30
  3695.6  311.65  3739.6  311.93  3991.9  300.22  4036.8  300.01  4063.9  297.19
  4126.0  294.87  4339.9  287.05  4738.6  286.63  4876.6  281.68  4919.0  281.67
  4937.5  277.62  4949.5  274.01  4955.4  274.76  4989.5  271.60  4989.8  271.10
  4994.0  271.60  5020.7  272.52  5049.0  275.94  5070.0  281.27  5095.5  283.89
  5110.9  284.57  5303.5  284.73  5348.6  286.82  5483.9  286.79  5728.0  295.34
  5798.8  302.06  5812.9  301.00  5841.3  302.44  5912.1  309.01  6096.0  321.35
#Mann=9,-1,0
  3695.6    0.07       0  4126.0   0.045       0  4937.5    0.05       0
  4989.5    0.05       0  4994.0    0.05       0  5095.5   0.045       0
  5110.9    0.05       0  5348.6   0.035       0  5483.9    0.05       0
Bank Sta=4989.5,4994
Exp/Cntr=0.3,0.1

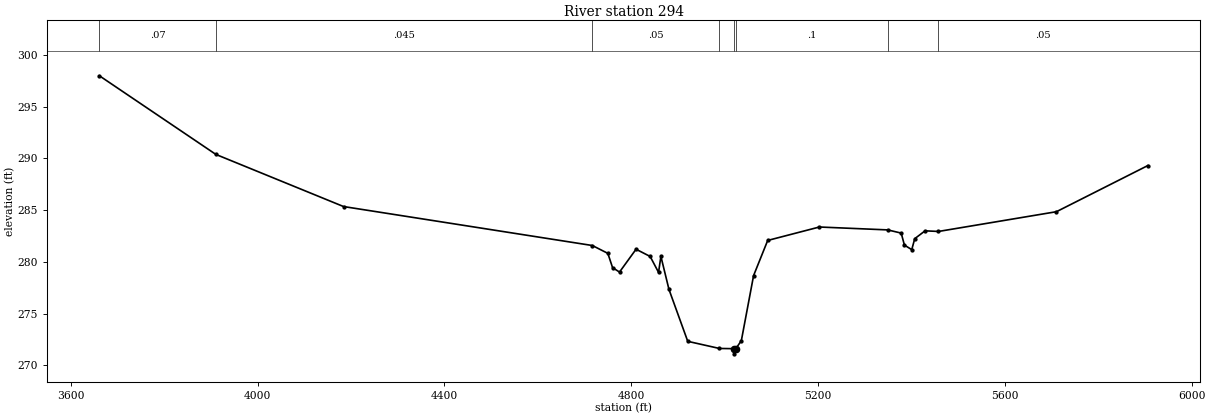
Type RM Length L Ch R = 1,294,0,0,0
BEGIN DESCRIPTION:
XS7745
END DESCRIPTION:
XS GIS Cut Line= 4
      2441781.22     13584634.70      2442199.83     13585158.90
      2443108.74     13585264.50      2443693.28     13584959.03
#Sta/Elev= 30
  3661.0  298.00  3910.5  290.39  4183.8  285.35  4716.6  281.58  4749.8  280.82
  4759.9  279.44  4774.8  279.01  4810.2  281.22  4840.4  280.52  4858.4  278.98
  4863.4  280.53  4880.7  277.33  4920.9  272.31  4988.8  271.62  5019.4  271.60
  5019.7  271.10  5023.9  271.60  5035.7  272.38  5061.9  278.67  5092.1  282.07
  5202.8  283.37  5349.2  283.09  5378.0  282.78  5384.9  281.62  5400.6  281.18
  5407.0  282.24  5429.1  283.00  5457.8  282.94  5710.4  284.85  5906.4  289.32
#Mann=8,-1,0
  3661.0    0.07       0  3910.5   0.045       0  4716.6    0.05       0
  4988.8     0.1       0  5019.4    0.05       0  5023.9     0.1       0
  5349.2   0.035       0  5457.8    0.05       0
Bank Sta=5019.4,5023.9
Exp/Cntr=0.3,0.1

Chan Stop Cuts=-1