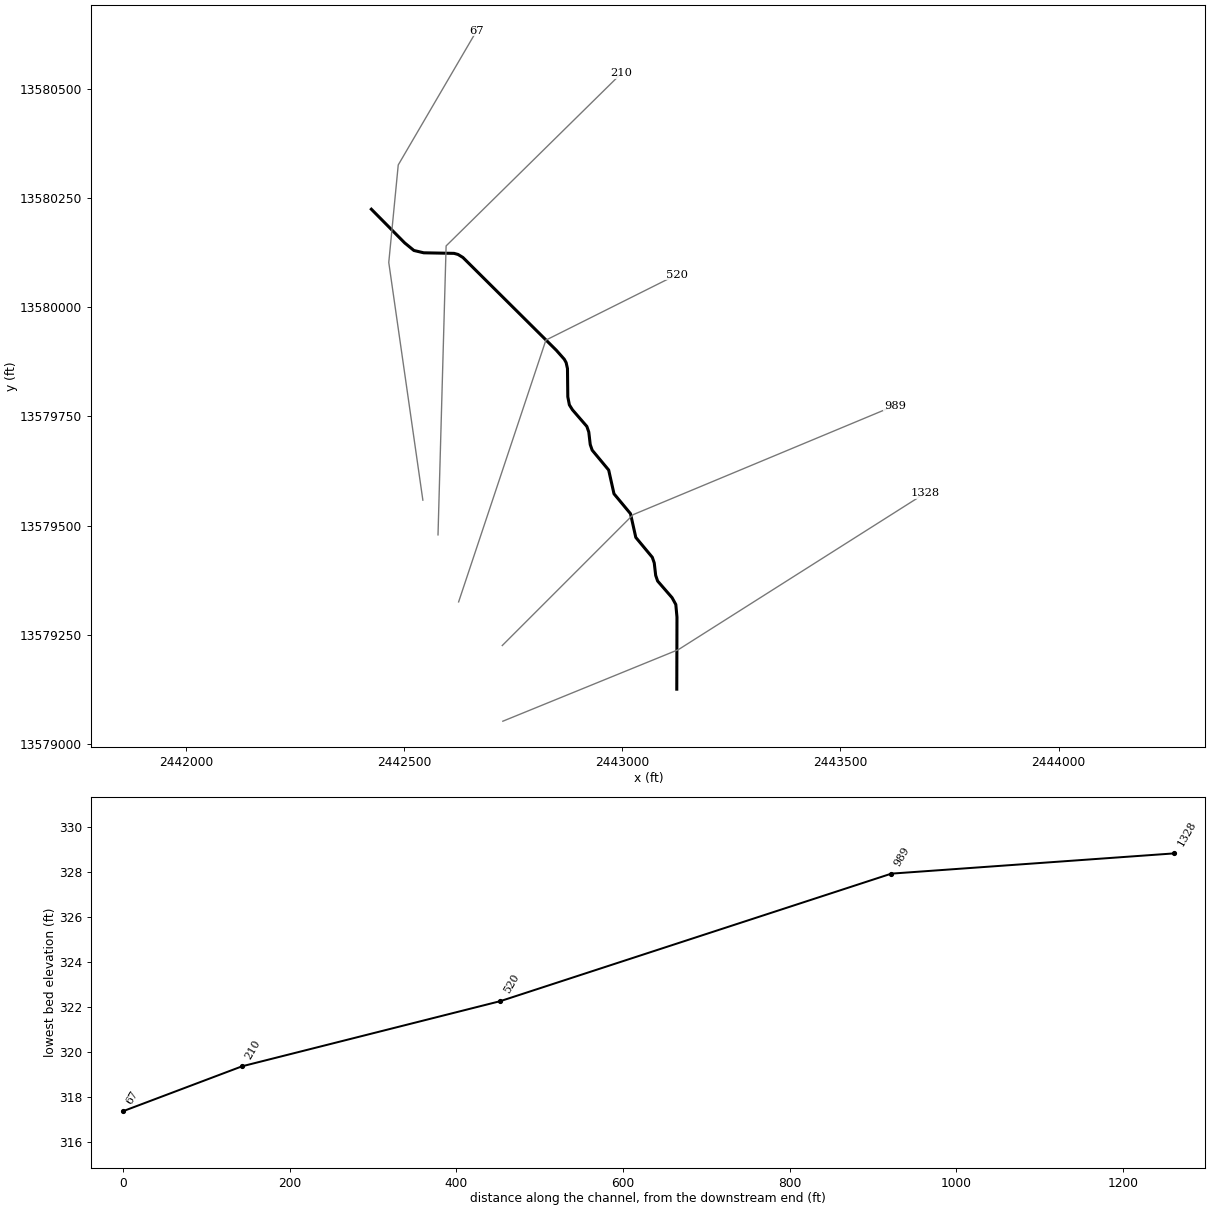
--- Stream0802.prj (project) ---

Proj Title=Stream0802 Base Level Engineering
Current Plan=p01
Default Exp/Contr=0.3,0.1
English Units
Geom File=g01
Flow File=f01
Plan File=p01
BEGIN DESCRIPTION:
Stream0802
END DESCRIPTION:

--- Stream0802.p01 (plan) ---

Plan Title=Multiple Run
Short Identifier=Multiple
Geom File=g01
Flow File=f01
Subcritical Flow
K Sum by GR= 0
Std Step Tol= 0.01
Critical Tol= 0.01
Num of Std Step Trials= 20
Max Error Tol= 0.3
Flow Tol Ratio= 0.001
Split Flow NTrial= 30
Split Flow Tol= 0.02
Split Flow Ratio= 0.02
Log Output Level= 0
Friction Slope Method= 1
Unsteady Friction Slope Method= 2
Unsteady Bridges Friction Slope Method= 1
Parabolic Critical Depth
Global Vel Dist=  1 , 1 , 1
Global Log Level= 0
CheckData=True
Encroach Param= -1, 0, 0, 0
BEGIN DESCRIPTION:
Multiple Run
END DESCRIPTION:

--- Stream0802.f01 (steady flow) ---

Flow Title=Multiple
Number of Profiles=7
Profile Names=10-year,25-year,50-year,1pct_min,100-year,1pct_plu,500-year
River Rch & RM= Stream0802,Reach-1,1328
     371     584     772     496     990    1975    1609
Boundary for River Rch & Prof#=Stream0802,Reach-1,1
Up Type=0
Dn Type=3
Dn Slope=0.005
Boundary for River Rch & Prof#=Stream0802,Reach-1,2
Up Type=0
Dn Type=3
Dn Slope=0.005
Boundary for River Rch & Prof#=Stream0802,Reach-1,3
Up Type=0
Dn Type=3
Dn Slope=0.005
Boundary for River Rch & Prof#=Stream0802,Reach-1,4
Up Type=0
Dn Type=3
Dn Slope=0.005
Boundary for River Rch & Prof#=Stream0802,Reach-1,5
Up Type=0
Dn Type=3
Dn Slope=0.005
Boundary for River Rch & Prof#=Stream0802,Reach-1,6
Up Type=0
Dn Type=3
Dn Slope=0.005
Boundary for River Rch & Prof#=Stream0802,Reach-1,7
Up Type=0
Dn Type=3
Dn Slope=0.005

--- Stream0802.g01 (geometry) ---

Geom Title=Existing Conditions

River Reach=Stream0802,Reach-1
Reach XY= 30
      2443125.00     13579125.00      2443125.45     13579290.19
      2443122.77     13579319.08      2443114.21     13579334.67
      2443081.12     13579372.82      2443076.67     13579385.69
      2443073.35     13579414.32      2443068.92     13579427.20
      2443031.08     13579472.80      2443018.92     13579527.20
      2442981.08     13579572.80      2442968.92     13579627.20
      2442931.08     13579672.80      2442926.65     13579685.68
      2442923.33     13579714.31      2442918.88     13579727.18
      2442885.84     13579765.35      2442878.83     13579776.59
      2442875.24     13579795.10      2442874.48     13579859.78
      2442871.39     13579873.50      2442867.14     13579881.17
      2442848.82     13579901.87      2442634.79     13580114.48
      2442623.50     13580121.39      2442614.52     13580123.84
      2442545.05     13580125.13      2442522.55     13580130.46
      2442501.43     13580147.77      2442425.00     13580225.00

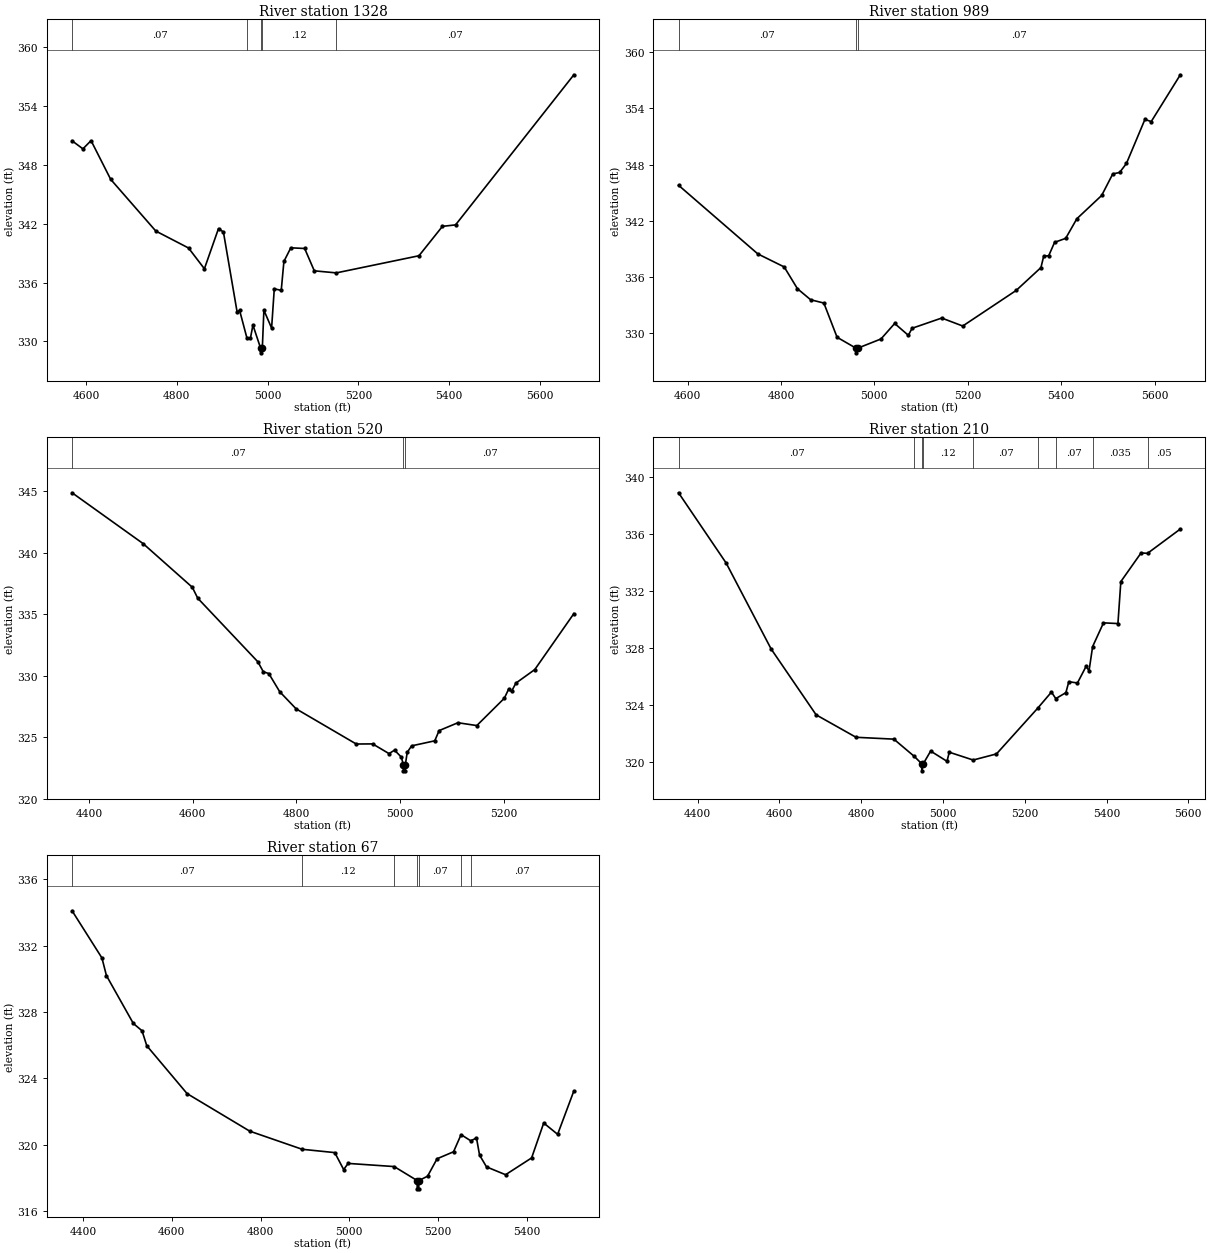
Type RM Length L Ch R = 1,1328,339,339,339
BEGIN DESCRIPTION:
XS7748
END DESCRIPTION:
XS GIS Cut Line= 3
      2442726.33     13579051.58      2443128.63     13579215.59
      2443694.99     13579574.60
#Sta/Elev= 30
  4569.4  350.47  4593.3  349.65  4611.2  350.49  4654.4  346.54  4753.8  341.26
  4825.9  339.53  4860.8  337.41  4891.9  341.52  4902.7  341.16  4932.9  332.98
  4938.3  333.17  4954.3  330.37  4962.3  330.36  4967.7  331.66  4984.4  329.33
  4984.6  328.83  4988.4  329.33  4991.8  333.18  5008.8  331.36  5014.7  335.37
  5030.0  335.20  5035.9  338.16  5051.1  339.55  5081.6  339.48  5102.8  337.20
  5151.3  336.99  5333.3  338.74  5385.0  341.74  5413.9  341.89  5674.4  357.21
#Mann=5,-1,0
  4569.4    0.07       0  4954.3    0.12       0  4984.4    0.05       0
  4988.4    0.12       0  5151.3    0.07       0
Bank Sta=4984.4,4988.4
Exp/Cntr=0.3,0.1

Type RM Length L Ch R = 1,989,469,469,469
BEGIN DESCRIPTION:
Stream0802 2.0
END DESCRIPTION:
XS GIS Cut Line= 3
      2442725.04     13579225.04      2443025.00     13579525.00
      2443624.99     13579774.99
#Sta/Elev= 30
  4580.8  345.80  4750.5  338.48  4807.0  337.09  4835.3  334.77  4863.6  333.59
  4891.9  333.24  4920.2  329.59  4960.6  328.43  4960.8  327.93  4964.6  328.43
  5014.2  329.41  5043.5  331.06  5072.7  329.80  5080.8  330.55  5144.2  331.64
  5189.2  330.79  5303.5  334.58  5356.6  337.02  5362.5  338.23  5373.3  338.29
  5385.8  339.71  5409.6  340.14  5433.5  342.23  5486.6  344.71  5510.4  347.01
  5525.0  347.16  5539.6  348.12  5579.2  352.82  5592.7  352.59  5655.0  357.58
#Mann=3,-1,0
  4580.8    0.07       0  4960.6    0.05       0  4964.6    0.07       0
Bank Sta=4960.6,4964.6
Exp/Cntr=0.3,0.1

Type RM Length L Ch R = 1,520,310,310,310
BEGIN DESCRIPTION:
Stream0802 1.0
END DESCRIPTION:
XS GIS Cut Line= 3
      2442625.01     13579325.04      2442825.00     13579925.00
      2443124.98     13580074.99
#Sta/Elev= 30
  4367.3  344.86  4504.3  340.73  4599.2  337.18  4609.7  336.29  4725.7  331.12
  4736.2  330.31  4746.7  330.17  4767.8  328.69  4799.4  327.30  4915.4  324.44
  4947.0  324.45  4978.6  323.66  4989.2  323.94  5002.5  323.37  5006.1  322.76
  5006.4  322.26  5009.9  322.26  5010.1  322.76  5013.7  323.76  5022.1  324.29
  5066.8  324.70  5075.2  325.53  5111.5  326.17  5147.9  325.94  5201.0  328.16
  5209.3  328.90  5214.9  328.72  5223.3  329.39  5259.7  330.49  5335.1  335.04
#Mann=3,-1,0
  4367.3    0.07       0  5006.1    0.05       0  5010.1    0.07       0
Bank Sta=5006.1,5010.1
Exp/Cntr=0.3,0.1

Type RM Length L Ch R = 1,210,143,143,143
BEGIN DESCRIPTION:
XS7747
END DESCRIPTION:
XS GIS Cut Line= 3
      2442577.76     13579478.62      2442596.33     13580140.93
      2442998.67     13580537.08
#Sta/Elev= 30
  4353.2  338.92  4469.6  333.98  4579.7  327.93  4689.7  323.30  4787.3  321.72
  4879.8  321.59  4930.0  320.37  4947.8  319.86  4948.1  319.36  4951.8  319.86
  4969.8  320.75  5009.8  320.03  5015.3  320.67  5073.8  320.12  5130.8  320.55
  5231.7  323.77  5265.2  324.90  5275.8  324.44  5300.5  324.86  5307.7  325.63
  5328.8  325.54  5350.1  326.72  5357.1  326.39  5365.9  328.10  5392.5  329.77
  5427.8  329.72  5434.9  332.67  5484.4  334.69  5500.2  334.66  5580.4  336.37
#Mann=9,-1,0
  4353.2    0.07       0  4930.0    0.12       0  4947.8    0.05       0
  4951.8    0.12       0  5073.8    0.07       0  5231.7   0.035       0
  5275.8    0.07       0  5365.9   0.035       0  5500.2    0.05       0
Bank Sta=4947.8,4951.8
Exp/Cntr=0.3,0.1

Type RM Length L Ch R = 1,67,0,0,0
BEGIN DESCRIPTION:
H21078
END DESCRIPTION:
XS GIS Cut Line= 4
      2442543.03     13579558.24      2442464.90     13580102.95
      2442486.60     13580326.48      2442666.72     13580634.63
#Sta/Elev= 30
  4374.9  334.09  4442.3  331.25  4452.4  330.19  4513.1  327.31  4532.7  326.87
  4543.4  325.97  4634.3  323.09  4775.7  320.83  4893.9  319.74  4967.4  319.54
  4987.5  318.52  4997.6  318.89  5101.4  318.70  5153.2  317.86  5153.4  317.36
  5156.9  317.36  5157.2  317.86  5176.7  318.12  5198.2  319.17  5235.3  319.59
  5252.3  320.62  5274.2  320.25  5287.1  320.42  5294.0  319.39  5309.7  318.68
  5352.7  318.21  5411.4  319.22  5438.7  321.32  5470.1  320.64  5506.7  323.25
#Mann=7,-1,0
  4374.9    0.07       0  4893.9    0.12       0  5101.4    0.07       0
  5153.2    0.05       0  5157.2    0.07       0  5252.3   0.035       0
  5274.2    0.07       0
Bank Sta=5153.2,5157.2
Exp/Cntr=0.3,0.1

Chan Stop Cuts=-1