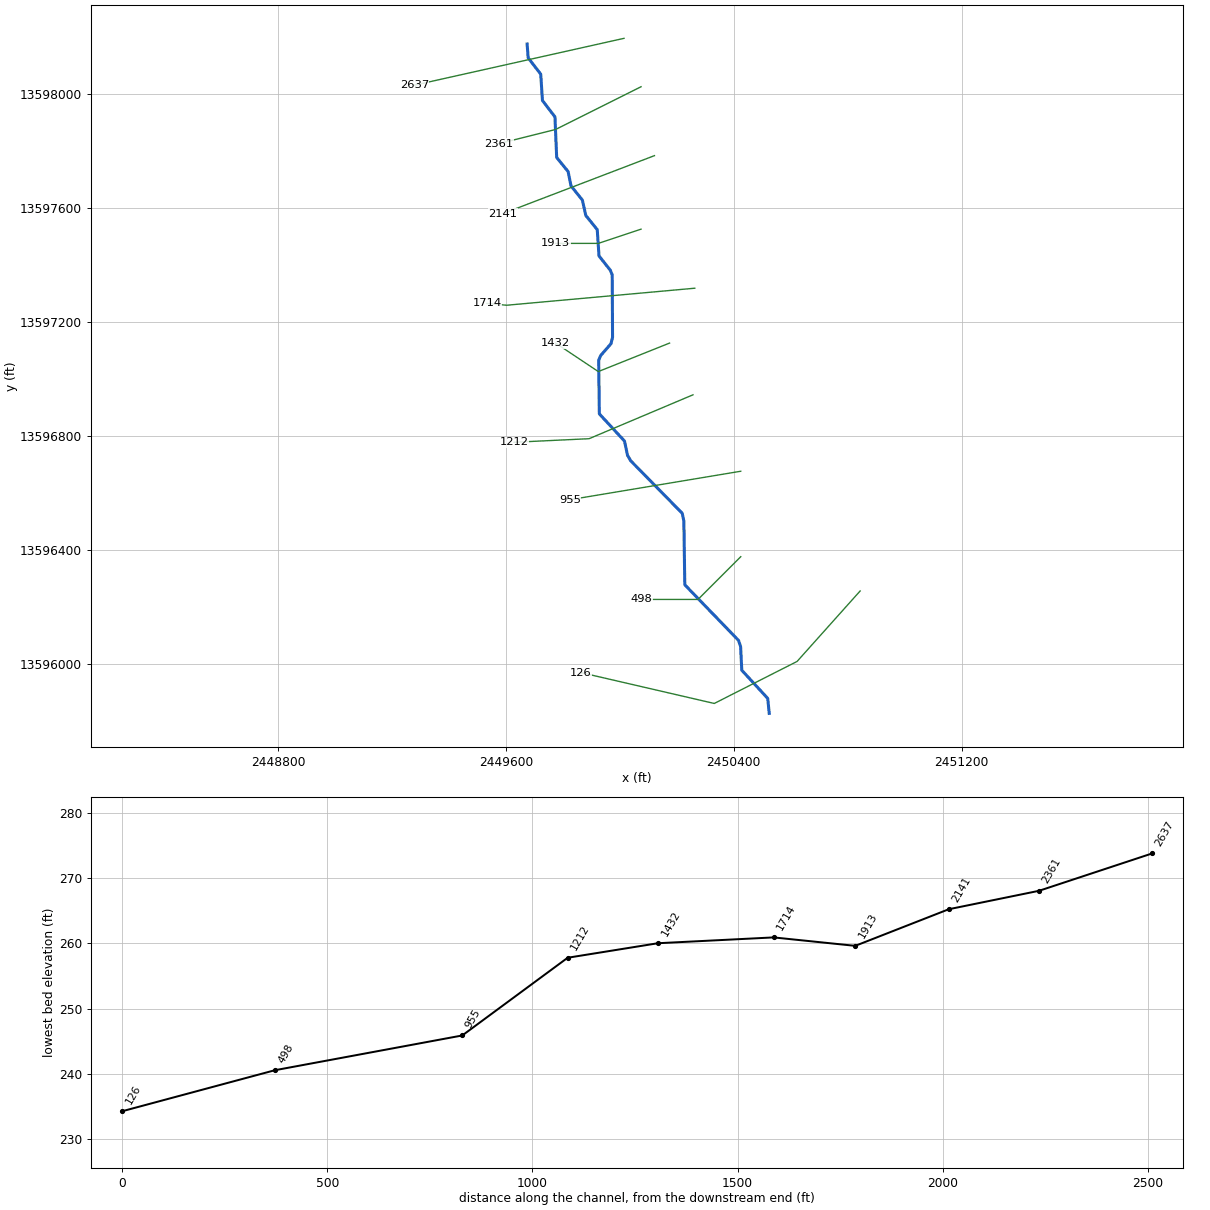
--- Stream0803.prj (project) ---

Proj Title=Stream0803 Base Level Engineering
Current Plan=p01
Default Exp/Contr=0.3,0.1
English Units
Geom File=g01
Flow File=f01
Plan File=p01
BEGIN DESCRIPTION:
Stream0803
END DESCRIPTION:

--- Stream0803.p01 (plan) ---

Plan Title=Multiple Run
Short Identifier=Multiple
Geom File=g01
Flow File=f01
Subcritical Flow
K Sum by GR= 0
Std Step Tol= 0.01
Critical Tol= 0.01
Num of Std Step Trials= 20
Max Error Tol= 0.3
Flow Tol Ratio= 0.001
Split Flow NTrial= 30
Split Flow Tol= 0.02
Split Flow Ratio= 0.02
Log Output Level= 0
Friction Slope Method= 1
Unsteady Friction Slope Method= 2
Unsteady Bridges Friction Slope Method= 1
Parabolic Critical Depth
Global Vel Dist=  1 , 1 , 1
Global Log Level= 0
CheckData=True
Encroach Param= -1, 0, 0, 0
BEGIN DESCRIPTION:
Multiple Run
END DESCRIPTION:

--- Stream0803.f01 (steady flow) ---

Flow Title=Multiple
Number of Profiles=7
Profile Names=10-year,25-year,50-year,1pct_min,100-year,1pct_plu,500-year
River Rch & RM= Stream0803,Reach-1,2637
     556     902    1218     798    1593    3179    2698
Boundary for River Rch & Prof#=Stream0803,Reach-1,1
Up Type=0
Dn Type=3
Dn Slope=0.005
Boundary for River Rch & Prof#=Stream0803,Reach-1,2
Up Type=0
Dn Type=3
Dn Slope=0.005
Boundary for River Rch & Prof#=Stream0803,Reach-1,3
Up Type=0
Dn Type=3
Dn Slope=0.005
Boundary for River Rch & Prof#=Stream0803,Reach-1,4
Up Type=0
Dn Type=3
Dn Slope=0.005
Boundary for River Rch & Prof#=Stream0803,Reach-1,5
Up Type=0
Dn Type=3
Dn Slope=0.005
Boundary for River Rch & Prof#=Stream0803,Reach-1,6
Up Type=0
Dn Type=3
Dn Slope=0.005
Boundary for River Rch & Prof#=Stream0803,Reach-1,7
Up Type=0
Dn Type=3
Dn Slope=0.005

--- Stream0803.g01 (geometry) ---

Geom Title=Existing Conditions

River Reach=Stream0803,Reach-1
Reach XY= 30
      2449675.00     13598175.00      2449678.64     13598126.51
      2449722.77     13598069.08      2449728.85     13597976.60
      2449772.73     13597919.06      2449778.76     13597776.56
      2449818.88     13597727.18      2449829.16     13597676.72
      2449868.92     13597627.20      2449881.12     13597572.82
      2449921.17     13597523.42      2449927.36     13597430.98
      2449966.86     13597381.06      2449973.78     13597364.50
      2449974.93     13597145.03      2449969.25     13597122.67
      2449933.14     13597081.06      2449926.22     13597064.49
      2449928.55     13596876.47      2450016.82     13596781.04
      2450027.53     13596731.05      2450038.63     13596711.79
      2450219.54     13596527.45      2450225.30     13596500.12
      2450228.54     13596276.46      2450417.14     13596081.17
      2450424.47     13596059.78      2450428.61     13595976.50
      2450519.67     13595877.51      2450525.00     13595825.00

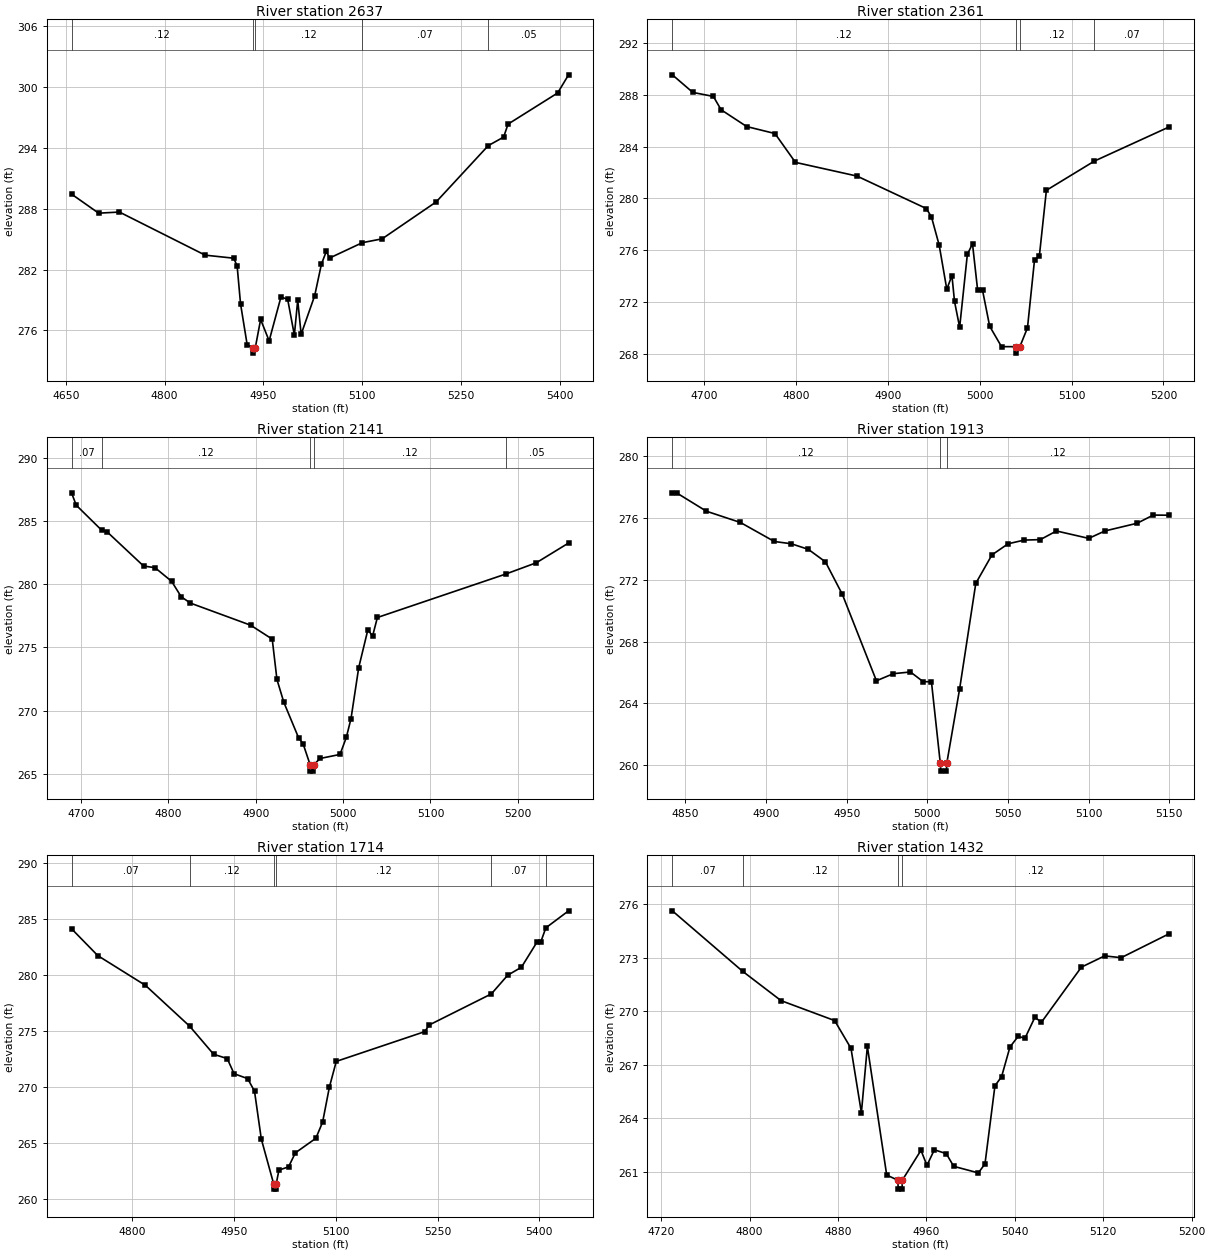
Type RM Length L Ch R = 1,2637,276,276,276
BEGIN DESCRIPTION:
XS7750
END DESCRIPTION:
XS GIS Cut Line= 2
      2450015.22     13598194.89      2449278.80     13598030.27
#Sta/Elev= 30
  4658.8  289.44  4700.0  287.56  4731.5  287.67  4861.7  283.42  4905.0  283.12
  4910.2  282.37  4915.4  278.62  4925.4  274.61  4933.7  274.26  4933.9  273.76
  4937.7  274.26  4945.9  277.08  4958.8  274.97  4976.7  279.28  4986.9  279.08
  4997.1  275.54  5002.2  278.98  5007.4  275.62  5027.9  279.41  5038.2  282.54
  5045.6  283.79  5050.7  283.14  5100.3  284.65  5130.4  285.03  5212.4  288.67
  5291.5  294.22  5314.8  295.06  5321.5  296.34  5396.8  299.41  5413.4  301.20
#Mann=5,-1,0
  4658.8    0.12       0  4933.7    0.05       0  4937.7    0.12       0
  5100.3    0.07       0  5291.5    0.05       0
Bank Sta=4933.7,4937.7
Exp/Cntr=0.3,0.1

Type RM Length L Ch R = 1,2361,220,220,220
BEGIN DESCRIPTION:
Stream0803 5.0
END DESCRIPTION:
XS GIS Cut Line= 3
      2450074.97     13598024.98      2449775.00     13597875.00
      2449575.03     13597825.01
#Sta/Elev= 30
  4665.0  289.56  4687.3  288.20  4709.7  287.89  4718.1  286.86  4746.0  285.56
  4776.8  285.02  4799.1  282.79  4866.2  281.73  4941.7  279.22  4947.3  278.57
  4955.7  276.39  4964.0  272.98  4969.6  274.04  4972.4  272.04  4978.0  270.04
  4986.4  275.68  4992.0  276.49  4997.6  272.91  5002.9  272.91  5010.7  270.12
  5023.6  268.54  5039.6  268.54  5039.9  268.04  5043.6  268.54  5051.9  270.00
  5059.6  275.27  5064.8  275.53  5072.5  280.63  5124.8  282.89  5206.5  285.54
#Mann=4,-1,0
  4665.0    0.12       0  5039.6    0.05       0  5043.6    0.12       0
  5124.8    0.07       0
Bank Sta=5039.6,5043.6
Exp/Cntr=0.3,0.1

Type RM Length L Ch R = 1,2141,228,228,228
BEGIN DESCRIPTION:
H21081
END DESCRIPTION:
XS GIS Cut Line= 2
      2450122.08     13597783.06      2449590.51     13597579.81
#Sta/Elev= 30
  4689.0  287.23  4694.4  286.25  4723.7  284.26  4729.8  284.14  4771.5  281.44
  4784.6  281.31  4803.6  280.23  4814.6  279.01  4825.1  278.51  4894.1  276.76
  4918.8  275.66  4924.2  272.47  4932.1  270.66  4948.9  267.87  4954.2  267.37
  4962.2  265.72  4962.5  265.22  4966.0  265.22  4966.2  265.72  4973.6  266.22
  4996.4  266.54  5003.6  267.88  5009.0  269.37  5017.8  273.40  5028.3  276.40
  5033.7  275.90  5039.2  277.37  5185.9  280.80  5221.2  281.70  5258.1  283.26
#Mann=5,-1,0
  4689.0    0.07       0  4723.7    0.12       0  4962.2    0.05       0
  4966.2    0.12       0  5185.9    0.05       0
Bank Sta=4962.2,4966.2
Exp/Cntr=0.3,0.1

Type RM Length L Ch R = 1,1913,199,199,199
BEGIN DESCRIPTION:
Stream0803 4.0
END DESCRIPTION:
XS GIS Cut Line= 3
      2450074.99     13597525.00      2449925.00     13597475.00
      2449775.00     13597475.00
#Sta/Elev= 30
  4841.9  277.64  4844.5  277.64  4863.0  276.45  4884.1  275.72  4905.1  274.49
  4915.7  274.34  4926.2  273.98  4936.8  273.17  4947.3  271.06  4968.4  265.47
  4978.9  265.93  4989.5  266.04  4997.4  265.41  5002.5  265.41  5008.0  260.12
  5008.3  259.62  5011.8  259.62  5012.0  260.12  5020.0  264.96  5030.0  271.78
  5040.0  273.62  5050.0  274.34  5060.0  274.58  5070.0  274.61  5080.0  275.17
  5100.0  274.69  5110.0  275.17  5130.0  275.67  5140.0  276.20  5150.0  276.19
#Mann=3,-1,0
  4841.9    0.12       0  5008.0    0.05       0  5012.0    0.12       0
Bank Sta=5008,5012
Exp/Cntr=0.3,0.1

Type RM Length L Ch R = 1,1714,282,282,282
BEGIN DESCRIPTION:
H21080
END DESCRIPTION:
XS GIS Cut Line= 3
      2450263.59     13597317.62      2449603.17     13597257.87
      2449533.97     13597264.16
#Sta/Elev= 30
  4710.4  284.17  4749.1  281.77  4819.4  279.11  4884.6  275.46  4919.8  272.96
  4939.9  272.57  4950.0  271.22  4970.0  270.78  4980.1  269.66  4990.1  265.39
  5008.2  261.41  5008.5  260.91  5012.0  260.91  5012.2  261.41  5016.1  262.61
  5030.3  262.90  5040.3  264.15  5070.5  265.45  5080.5  266.90  5090.5  270.03
  5100.6  272.32  5231.1  274.98  5237.5  275.57  5329.2  278.35  5353.3  280.02
  5373.5  280.73  5396.9  283.02  5401.9  282.97  5409.5  284.25  5443.0  285.77
#Mann=6,-1,0
  4710.4    0.07       0  4884.6    0.12       0  5008.2    0.05       0
  5012.2    0.12       0  5329.2    0.07       0  5409.5    0.05       0
Bank Sta=5008.2,5012.2
Exp/Cntr=0.3,0.1

Type RM Length L Ch R = 1,1432,220,220,220
BEGIN DESCRIPTION:
Stream0803 3.0
END DESCRIPTION:
XS GIS Cut Line= 3
      2450175.04     13597125.02      2449925.00     13597025.00
      2449774.99     13597125.01
#Sta/Elev= 30
  4730.2  275.64  4793.7  272.25  4828.5  270.60  4877.0  269.48  4891.8  267.92
  4901.2  264.31  4906.6  268.03  4924.1  260.81  4934.2  260.52  4934.5  260.02
  4938.0  260.02  4938.2  260.52  4955.1  262.20  4960.5  261.35  4967.2  262.23
  4978.0  262.01  4984.7  261.30  5007.0  260.93  5013.0  261.44  5022.0  265.82
  5028.0  266.33  5035.6  268.00  5043.1  268.60  5049.1  268.48  5058.1  269.66
  5064.1  269.39  5100.2  272.48  5121.2  273.11  5136.2  273.01  5179.8  274.36
#Mann=4,-1,0
  4730.2    0.07       0  4793.7    0.12       0  4934.2    0.05       0
  4938.2    0.12       0
Bank Sta=4934.2,4938.2
Exp/Cntr=0.3,0.1

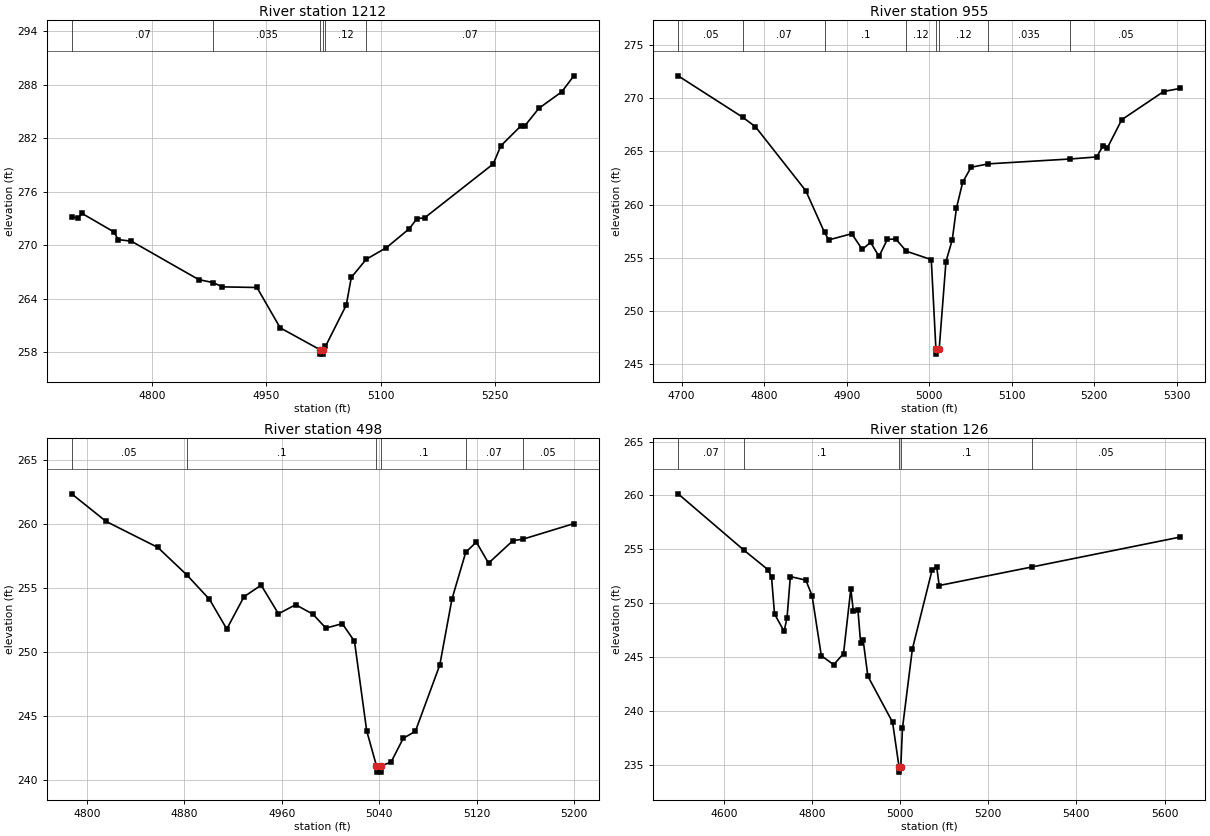
Type RM Length L Ch R = 1,1212,257,257,257
BEGIN DESCRIPTION:
H21079
END DESCRIPTION:
XS GIS Cut Line= 3
      2450257.27     13596943.39      2449892.49     13596789.30
      2449629.18     13596776.76
#Sta/Elev= 30
  4694.2  273.17  4702.5  273.08  4707.9  273.57  4749.9  271.49  4755.3  270.64
  4772.7  270.46  4861.0  266.16  4880.4  265.81  4892.1  265.34  4937.6  265.27
  4968.1  260.75  5020.3  258.30  5020.6  257.80  5024.1  257.80  5024.3  258.30
  5027.6  258.67  5054.9  263.30  5061.5  266.40  5081.1  268.43  5107.7  269.74
  5137.7  271.86  5147.7  272.99  5157.8  273.08  5247.9  279.12  5257.9  281.15
  5284.3  283.39  5289.3  283.38  5307.9  285.36  5338.0  287.21  5353.8  289.00
#Mann=6,-1,0
  4694.2    0.07       0  4880.4   0.035       0  5020.3   0.035       0
  5024.3   0.035       0  5027.6    0.12       0  5081.1    0.07       0
Bank Sta=5020.3,5024.3
Exp/Cntr=0.3,0.1

Type RM Length L Ch R = 1,955,457,457,457
BEGIN DESCRIPTION:
Stream0803 2.0
END DESCRIPTION:
XS GIS Cut Line= 3
      2450424.97     13596675.00      2450125.00     13596625.00
      2449825.05     13596575.01
#Sta/Elev= 30
  4695.9  272.12  4773.9  268.23  4789.6  267.32  4850.5  261.30  4873.2  257.37
  4878.4  256.67  4906.2  257.25  4918.9  255.77  4929.0  256.44  4939.2  255.11
  4949.3  256.72  4959.5  256.75  4972.4  255.60  5002.5  254.81  5008.1  246.41
  5008.4  245.91  5012.1  246.41  5020.3  254.63  5027.9  256.67  5033.0  259.67
  5040.6  262.11  5050.7  263.51  5071.7  263.83  5171.0  264.29  5202.8  264.48
  5210.4  265.51  5215.4  265.28  5233.2  267.99  5283.9  270.64  5304.1  270.94
#Mann=8,-1,0
  4695.9    0.05       0  4773.9    0.07       0  4873.2     0.1       0
  4972.4    0.12       0  5008.1    0.05       0  5012.1    0.12       0
  5071.7   0.035       0  5171.0    0.05       0
Bank Sta=5008.1,5012.1
Exp/Cntr=0.3,0.1

Type RM Length L Ch R = 1,498,372,372,372
BEGIN DESCRIPTION:
Stream0803 1.0
END DESCRIPTION:
XS GIS Cut Line= 3
      2450424.98     13596374.98      2450275.00     13596225.00
      2450075.01     13596225.00
#Sta/Elev= 30
  4787.5  262.35  4815.8  260.19  4858.2  258.16  4882.1  256.00  4900.6  254.10
  4914.8  251.78  4928.9  254.30  4943.0  255.21  4957.2  252.97  4971.3  253.68
  4985.5  252.94  4996.1  251.85  5009.6  252.20  5019.6  250.82  5029.6  243.83
  5037.6  241.09  5037.9  240.59  5041.4  240.59  5041.6  241.09  5049.6  241.37
  5059.6  243.23  5069.6  243.79  5089.6  248.97  5099.6  254.13  5110.9  257.78
  5119.6  258.58  5129.6  256.93  5149.6  258.69  5157.7  258.80  5199.6  260.02
#Mann=6,-1,0
  4787.5    0.05       0  4882.1     0.1       0  5037.6    0.05       0
  5041.6     0.1       0  5110.9    0.07       0  5157.7    0.05       0
Bank Sta=5037.6,5041.6
Exp/Cntr=0.3,0.1

Type RM Length L Ch R = 1,126,0,0,0
BEGIN DESCRIPTION:
XS7749
END DESCRIPTION:
XS GIS Cut Line= 4
      2450844.17     13596254.76      2450622.83     13596007.38
      2450332.03     13595859.81      2449863.28     13595968.32
#Sta/Elev= 30
  4496.6  260.15  4646.2  254.91  4701.0  253.09  4708.5  252.42  4715.3  249.00
  4737.0  247.39  4743.7  248.65  4751.2  252.47  4786.3  252.14  4800.5  250.69
  4821.4  245.13  4849.5  244.29  4871.8  245.32  4888.4  251.33  4894.0  249.28
  4904.6  249.33  4910.7  246.27  4916.3  246.58  4927.0  243.23  4983.1  238.95
  4997.7  234.82  4998.0  234.32  5001.7  234.82  5005.5  238.39  5028.0  245.75
  5072.8  253.09  5083.2  253.37  5088.8  251.64  5299.1  253.36  5635.8  256.14
#Mann=5,-1,0
  4496.6    0.07       0  4646.2     0.1       0  4997.7    0.05       0
  5001.7     0.1       0  5299.1    0.05       0
Bank Sta=4997.7,5001.7
Exp/Cntr=0.3,0.1

Chan Stop Cuts=-1