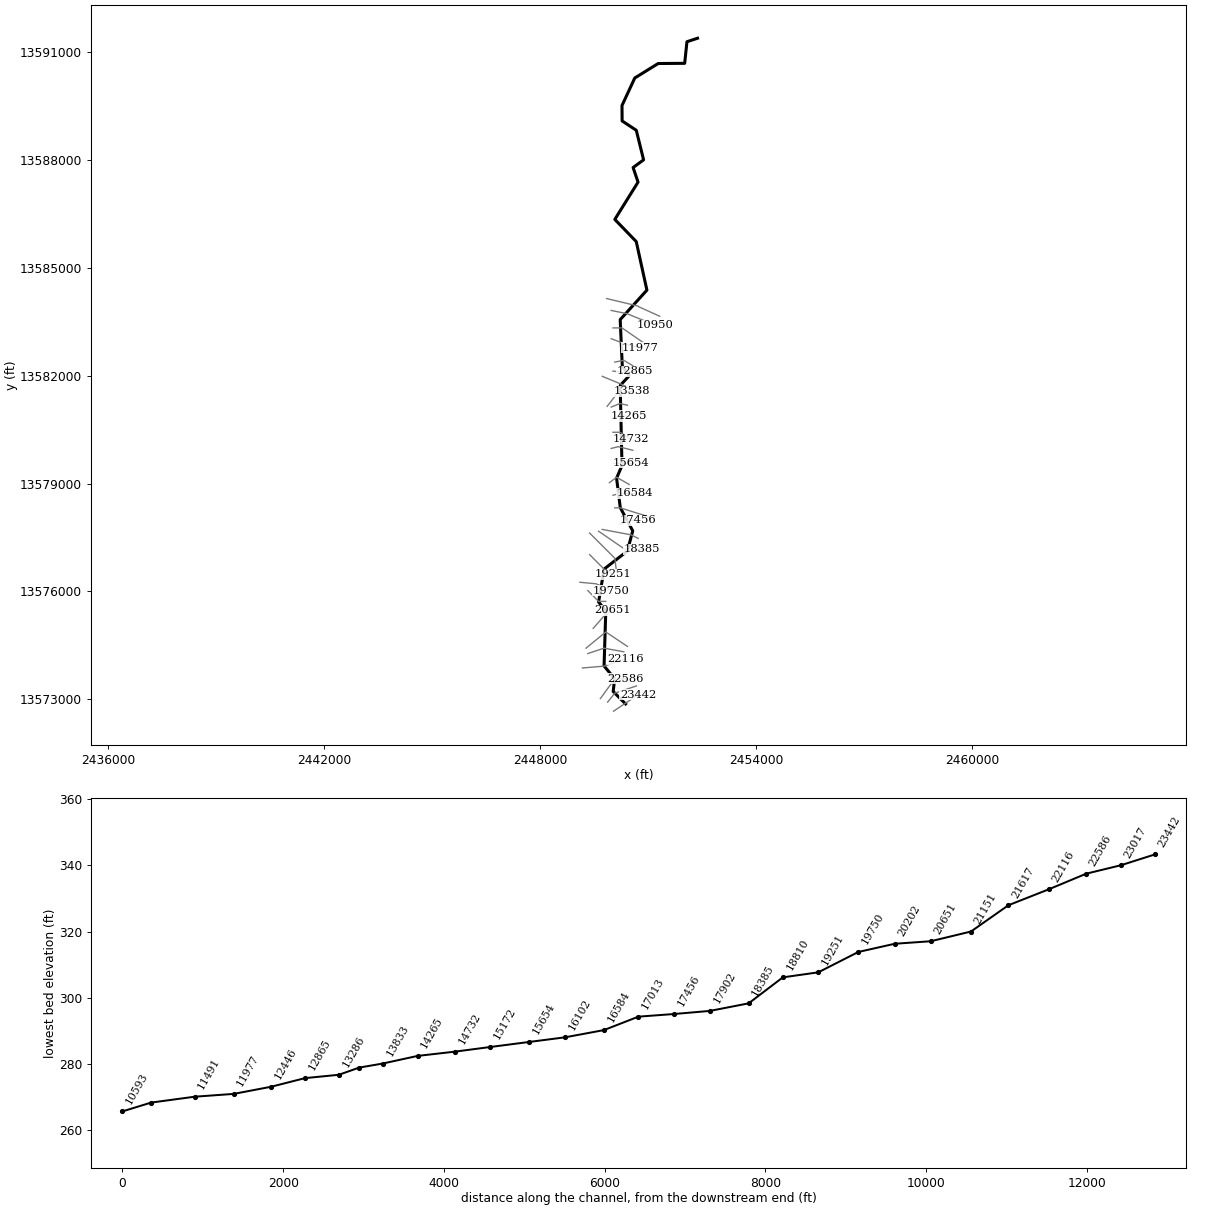
--- Stream0804.prj (project) ---

Proj Title=Stream0804 Base Level Engineering
Current Plan=p01
Default Exp/Contr=0.3,0.1
English Units
Geom File=g01
Flow File=f01
Plan File=p01
Y Axis Title=Elevation
X Axis Title(PF)=Main Channel Distance
X Axis Title(XS)=Station
BEGIN DESCRIPTION:
Stream0804
END DESCRIPTION:
DSS Export Rating Curves= 0
DSS Export Rating Curve Sorted= 0
DSS Export Volume Flow Curves= 0
DXF OffsetX= 0
DXF OffsetY= 0
DXF ScaleX= 1
DXF ScaleY= 10

--- Stream0804.p01 (plan) ---

Plan Title=Multiple Run
Short Identifier=Multiple
Geom File=g01
Flow File=f01
Subcritical Flow
K Sum by GR= 0
Std Step Tol= 0.01
Critical Tol= 0.01
Num of Std Step Trials= 20
Max Error Tol= 0.3
Flow Tol Ratio= 0.001
Split Flow NTrial= 30
Split Flow Tol= 0.02
Split Flow Ratio= 0.02
Log Output Level= 0
Friction Slope Method= 1
Unsteady Friction Slope Method= 2
Unsteady Bridges Friction Slope Method= 1
Parabolic Critical Depth
Global Vel Dist=  1 , 1 , 1
Global Log Level= 0
CheckData=True
Encroach Param= -1, 0, 0, 0
BEGIN DESCRIPTION:
Multiple Run
END DESCRIPTION:

--- Stream0804.f01 (steady flow) ---

Flow Title=Multiple
Number of Profiles=7
Profile Names=10-year,25-year,50-year,1pct_min,100-year,1pct_plu,500-year
River Rch & RM= Stream0804,Reach-1,23442
     418     663     880     567    1132    2258    1853
River Rch & RM= Stream0804,Reach-1,20202
     763    1255    1708    1126    2246    4482    3851
River Rch & RM= Stream0804,Reach-1,18385
    1136    1905    2626    1751    3494    6971    6131
River Rch & RM= Stream0804,Reach-1,16102
    1202    2018    2783    1856    3703    7388    6498
River Rch & RM= Stream0804,Reach-1,13286
    1763    3003    4181    2809    5605   11183    9994
River Rch & RM= Stream0804,Reach-1,6976
    1942    3310    4611    3097    6180   12331   11016
Boundary for River Rch & Prof#=Stream0804,Reach-1,1
Up Type=0
Dn Type=3
Dn Slope=0.005
Boundary for River Rch & Prof#=Stream0804,Reach-1,2
Up Type=0
Dn Type=3
Dn Slope=0.005
Boundary for River Rch & Prof#=Stream0804,Reach-1,3
Up Type=0
Dn Type=3
Dn Slope=0.005
Boundary for River Rch & Prof#=Stream0804,Reach-1,4
Up Type=0
Dn Type=3
Dn Slope=0.005
Boundary for River Rch & Prof#=Stream0804,Reach-1,5
Up Type=0
Dn Type=3
Dn Slope=0.005
Boundary for River Rch & Prof#=Stream0804,Reach-1,6
Up Type=0
Dn Type=3
Dn Slope=0.005
Boundary for River Rch & Prof#=Stream0804,Reach-1,7
Up Type=0
Dn Type=3
Dn Slope=0.005

--- Stream0804.g01 (geometry) ---

Geom Title=Existing Conditions

River Reach=Stream0804,Reach-1
Reach XY= 30
      2450375.00     13572875.00      2450030.46     13573222.55
      2450071.54     13573573.50      2449777.06     13573930.85
      2449824.67     13575459.97      2449624.56     13575709.82
      2449778.55     13576623.53      2450425.00     13577125.00
      2450573.81     13577685.50      2450227.06     13578330.85
      2450124.60     13579150.00      2450275.24     13579499.92
      2450225.00     13581725.00      2450475.41     13581995.13
      2450282.79     13582271.58      2450224.95     13583555.02
      2450967.67     13584374.90      2450671.24     13585723.44
      2450075.52     13586340.22      2450721.26     13587376.56
      2450583.95     13587781.69      2450875.39     13587995.37
      2450672.00     13588817.05      2450278.75     13589076.55
      2450275.26     13589504.72      2450630.18     13590269.56
      2451280.94     13590672.75      2452016.89     13590677.51
      2452080.34     13591277.74      2452375.00     13591375.00

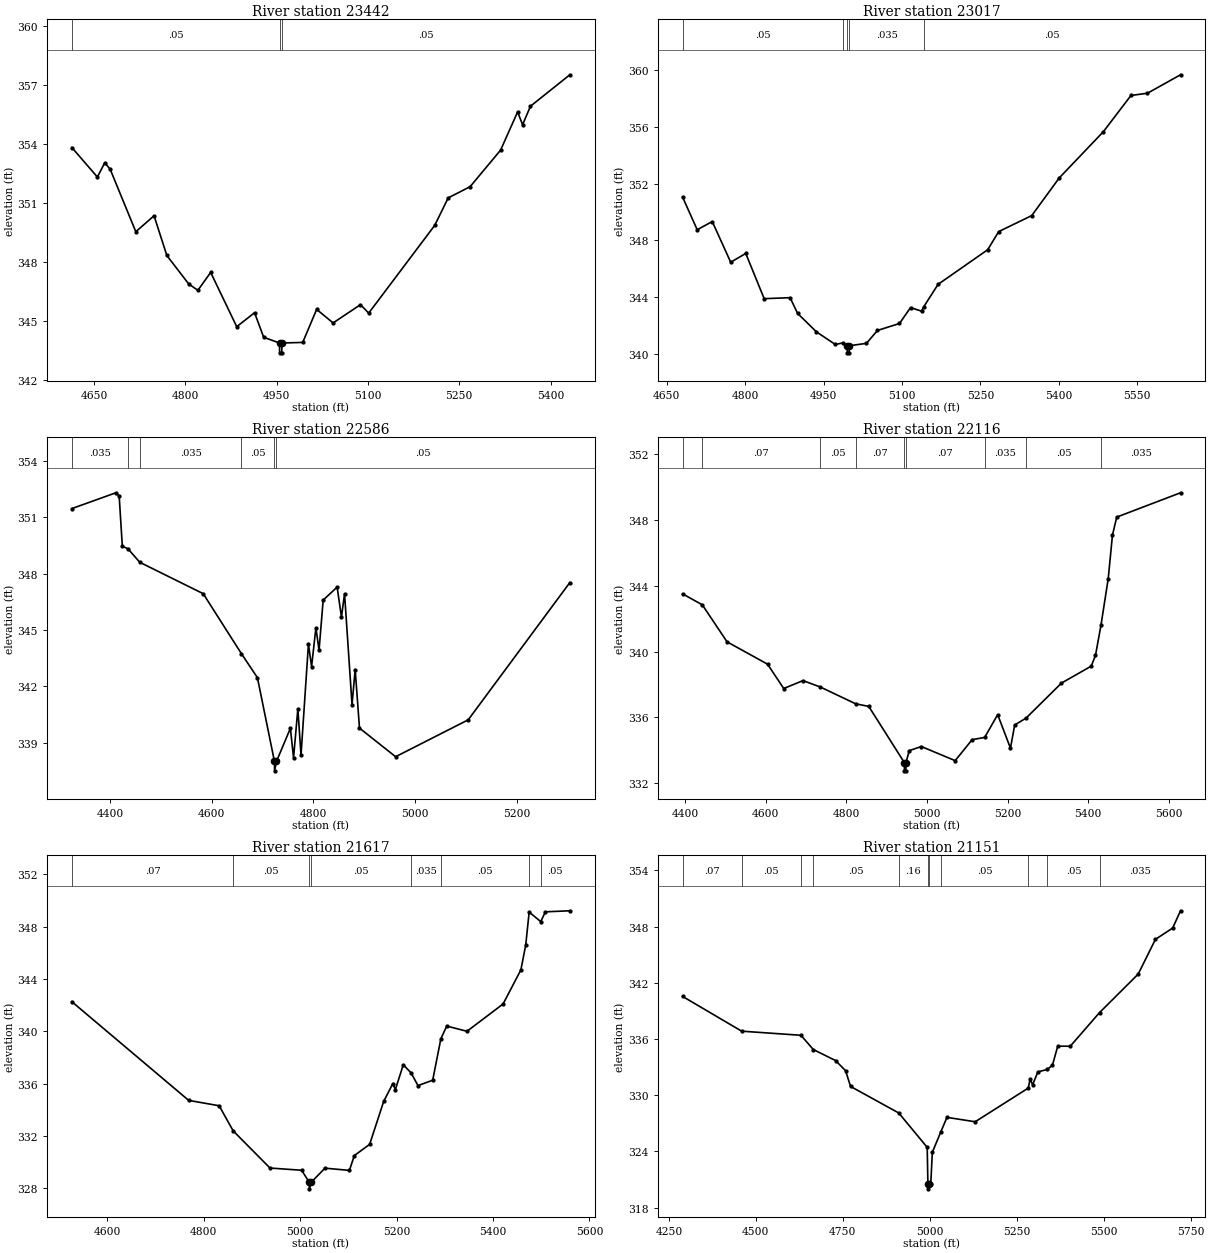
Type RM Length L Ch R = 1,23442,425,425,425
BEGIN DESCRIPTION:
XS7751
END DESCRIPTION:
XS GIS Cut Line= 2
      2450040.07     13572673.34      2450719.41     13573129.00
#Sta/Elev= 30
  4613.7  353.80  4655.6  352.30  4667.8  353.03  4676.7  352.69  4718.7  349.52
  4748.7  350.33  4769.7  348.31  4805.7  346.86  4820.7  346.54  4841.7  347.45
  4884.5  344.69  4913.8  345.40  4928.8  344.15  4954.8  343.86  4955.0  343.36
  4958.5  343.36  4958.8  343.86  4992.9  343.89  5015.8  345.57  5042.8  344.88
  5087.8  345.81  5101.3  345.38  5209.7  349.84  5231.9  351.24  5267.9  351.81
  5318.0  353.67  5345.9  355.61  5354.1  354.96  5367.0  355.90  5431.7  357.50
#Mann=3,-1,0
  4613.7    0.05       0  4954.8    0.05       0  4958.8    0.05       0
Bank Sta=4954.8,4958.8
Exp/Cntr=0.3,0.1

Type RM Length L Ch R = 1,23017,431,431,431
BEGIN DESCRIPTION:
Stream0804 50.0
END DESCRIPTION:
XS GIS Cut Line= 3
      2449874.99     13572924.99      2450075.00     13573175.00
      2450674.98     13573374.99
#Sta/Elev= 30
  4680.1  351.06  4708.1  348.75  4736.9  349.33  4772.2  346.46  4801.0  347.08
  4836.2  343.89  4885.8  343.96  4900.2  342.85  4936.2  341.55  4972.3  340.66
  4986.6  340.77  4995.1  340.57  4995.3  340.07  4998.8  340.07  4999.1  340.57
  5031.9  340.74  5053.0  341.65  5095.1  342.14  5116.2  343.26  5137.3  343.01
  5141.7  343.33  5168.9  344.90  5263.8  347.34  5284.9  348.62  5348.1  349.75
  5400.8  352.41  5485.2  355.67  5537.9  358.22  5569.5  358.38  5632.7  359.68
#Mann=5,-1,0
  4680.1    0.05       0  4986.6   0.035       0  4995.1   0.035       0
  4999.1   0.035       0  5141.7    0.05       0
Bank Sta=4995.1,4999.1
Exp/Cntr=0.3,0.1

Type RM Length L Ch R = 1,22586,470,470,470
BEGIN DESCRIPTION:
Stream0804 49.0
END DESCRIPTION:
XS GIS Cut Line= 3
      2449674.99     13573024.98      2450075.00     13573575.00
      2450375.00     13573575.00
#Sta/Elev= 30
  4324.5  351.45  4411.1  352.29  4417.6  352.12  4423.8  349.45  4434.8  349.32
  4458.0  348.60  4583.0  346.93  4658.3  343.74  4689.7  342.47  4723.2  338.02
  4723.5  337.52  4727.2  338.02  4754.6  339.78  4760.8  338.21  4769.3  340.82
  4775.5  338.35  4790.1  344.25  4796.3  343.06  4804.8  345.12  4811.0  343.93
  4819.1  346.59  4846.6  347.28  4855.1  345.69  4861.2  346.93  4875.9  341.04
  4882.1  342.90  4890.6  339.79  4961.7  338.27  5104.6  340.23  5304.6  347.52
#Mann=6,-1,0
  4324.5   0.035       0  4434.8    0.05       0  4458.0   0.035       0
  4658.3    0.05       0  4723.2    0.05       0  4727.2    0.05       0
Bank Sta=4723.2,4727.2
Exp/Cntr=0.3,0.1

Type RM Length L Ch R = 1,22116,499,499,499
BEGIN DESCRIPTION:
Stream0804 48.0
END DESCRIPTION:
XS GIS Cut Line= 3
      2449175.03     13573875.00      2449775.00     13573925.00
      2450375.00     13574125.00
#Sta/Elev= 30
  4394.1  343.52  4443.1  342.85  4504.4  340.60  4604.8  339.24  4644.9  337.76
  4692.6  338.24  4734.8  337.86  4823.2  336.83  4855.7  336.67  4944.0  333.25
  4944.2  332.75  4947.7  332.75  4948.0  333.25  4956.0  333.98  4986.1  334.23
  5069.9  333.37  5112.1  334.65  5143.0  334.78  5175.3  336.17  5207.0  334.13
  5217.5  335.54  5245.7  335.96  5333.5  338.09  5407.2  339.12  5417.8  339.77
  5431.4  341.61  5449.4  344.45  5459.9  347.10  5470.5  348.19  5628.6  349.67
#Mann=9,-1,0
  4394.1    0.05       0  4443.1    0.07       0  4734.8    0.05       0
  4823.2    0.07       0  4944.0    0.07       0  4948.0    0.07       0
  5143.0   0.035       0  5245.7    0.05       0  5431.4   0.035       0
Bank Sta=4944,4948
Exp/Cntr=0.3,0.1

Type RM Length L Ch R = 1,21617,466,466,466
BEGIN DESCRIPTION:
Stream0804 47.0
END DESCRIPTION:
XS GIS Cut Line= 3
      2449325.04     13574275.01      2449775.00     13574425.00
      2450324.98     13574325.00
#Sta/Elev= 30
  4526.1  342.26  4768.5  334.72  4831.7  334.31  4860.8  332.39  4937.2  329.55
  5002.9  329.38  5018.7  328.46  5019.0  327.96  5022.7  328.46  5051.2  329.54
  5102.0  329.37  5112.2  330.50  5144.0  331.36  5173.2  334.65  5192.2  336.01
  5197.3  335.54  5213.8  337.44  5230.0  336.82  5244.3  335.85  5274.8  336.26
  5291.8  339.43  5304.0  340.40  5346.0  340.00  5420.9  342.09  5457.8  344.69
  5467.9  346.60  5475.0  349.11  5499.1  348.38  5508.6  349.13  5559.4  349.21
#Mann=8,-1,0
  4526.1    0.07       0  4860.8    0.05       0  5018.7    0.05       0
  5022.7    0.05       0  5230.0   0.035       0  5291.8    0.05       0
  5475.0   0.035       0  5499.1    0.05       0
Bank Sta=5018.7,5022.7
Exp/Cntr=0.3,0.1

Type RM Length L Ch R = 1,21151,500,500,500
BEGIN DESCRIPTION:
Stream0804 46.0
END DESCRIPTION:
XS GIS Cut Line= 3
      2449275.04     13574425.03      2449825.00     13574875.00
      2450425.00     13574475.00
#Sta/Elev= 30
  4289.4  340.54  4459.3  336.83  4629.8  336.39  4665.3  334.87  4729.4  333.69
  4758.1  332.61  4772.4  330.93  4910.9  328.10  4992.8  324.43  4994.8  320.50
  4995.0  320.00  4998.8  320.50  5003.0  320.50  5007.5  323.90  5032.4  326.12
  5049.6  327.63  5130.7  327.16  5283.6  330.76  5288.4  331.70  5295.9  331.12
  5311.0  332.48  5338.5  332.75  5353.0  333.21  5368.1  335.23  5404.1  335.22
  5488.2  338.81  5599.4  342.92  5649.0  346.63  5698.6  347.84  5721.1  349.68
#Mann=11,-1,0
  4289.4    0.07       0  4459.3    0.05       0  4629.8   0.035       0
  4665.3    0.05       0  4910.9    0.16       0  4994.8    0.07       0
  4998.8    0.16       0  5032.4    0.05       0  5283.6   0.035       0
  5338.5    0.05       0  5488.2   0.035       0
Bank Sta=4994.8,4998.8
Exp/Cntr=0.3,0.1

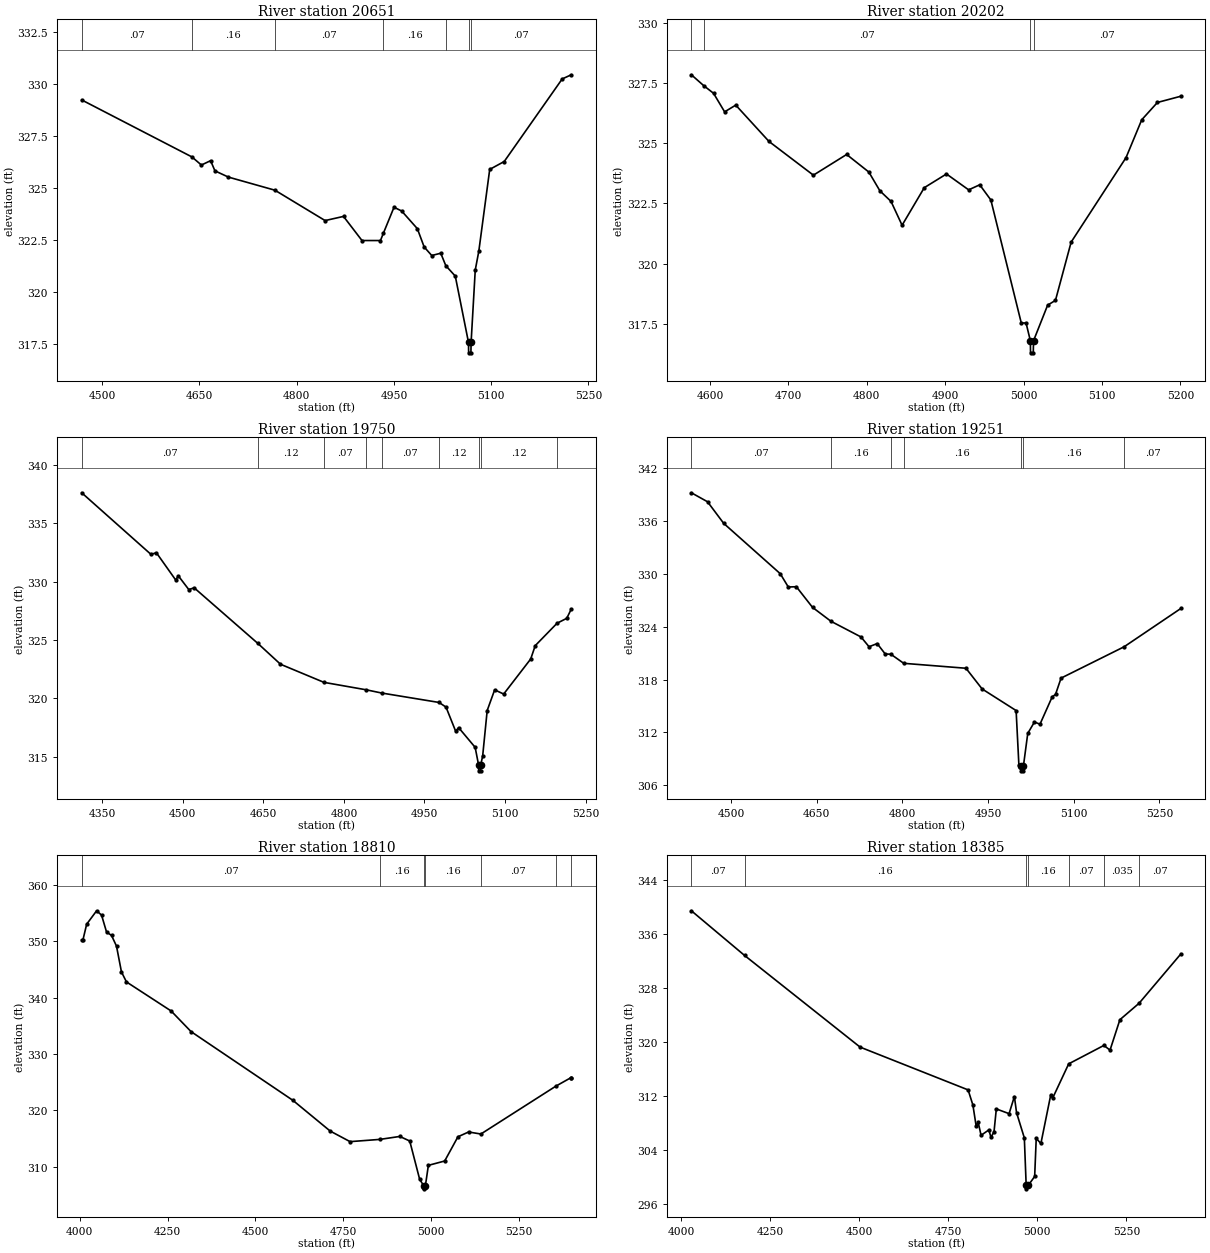
Type RM Length L Ch R = 1,20651,449,449,449
BEGIN DESCRIPTION:
Stream0804 45.0
END DESCRIPTION:
XS GIS Cut Line= 3
      2449475.01     13574975.02      2449825.00     13575375.00
      2450025.01     13575475.00
#Sta/Elev= 30
  4468.4  329.22  4638.4  326.48  4653.0  326.09  4667.2  326.30  4673.9  325.81
  4694.7  325.51  4766.4  324.88  4843.8  323.42  4872.2  323.62  4900.7  322.46
  4929.2  322.46  4933.7  322.81  4950.1  324.06  4961.9  323.88  4986.1  323.03
  4996.6  322.15  5008.3  321.74  5022.2  321.85  5030.0  321.25  5044.6  320.75
  5065.0  317.56  5065.2  317.06  5068.7  317.06  5069.0  317.56  5075.4  321.04
  5080.9  321.95  5097.7  325.88  5120.1  326.26  5209.5  330.23  5223.5  330.43
#Mann=7,-1,0
  4468.4    0.07       0  4638.4    0.16       0  4766.4    0.07       0
  4933.7    0.16       0  5030.0    0.07       0  5065.0    0.07       0
  5069.0    0.07       0
Bank Sta=5065,5069
Exp/Cntr=0.3,0.1

Type RM Length L Ch R = 1,20202,452,452,452
BEGIN DESCRIPTION:
Stream0804 44.0
END DESCRIPTION:
XS GIS Cut Line= 3
      2449324.99     13576025.01      2449625.00     13575725.00
      2449825.02     13575725.00
#Sta/Elev= 30
  4576.3  327.84  4592.0  327.39  4604.6  327.07  4618.7  326.30  4632.9  326.58
  4675.3  325.07  4731.9  323.67  4774.3  324.53  4802.6  323.80  4816.7  323.02
  4830.9  322.58  4845.0  321.59  4873.3  323.15  4901.6  323.72  4929.9  323.06
  4944.0  323.27  4958.2  322.64  4997.0  317.53  5003.1  317.53  5008.6  316.79
  5008.8  316.29  5012.3  316.29  5012.6  316.79  5030.6  318.27  5040.6  318.47
  5060.6  320.89  5130.6  324.40  5150.6  325.97  5170.6  326.69  5200.6  326.95
#Mann=4,-1,0
  4576.3   0.035       0  4592.0    0.07       0  5008.6    0.07       0
  5012.6    0.07       0
Bank Sta=5008.6,5012.6
Exp/Cntr=0.3,0.1

Type RM Length L Ch R = 1,19750,499,499,499
BEGIN DESCRIPTION:
Stream0804 43.0
END DESCRIPTION:
XS GIS Cut Line= 4
      2449106.64     13576256.64      2449551.79     13576214.28
      2449775.00     13576125.00      2449975.02     13576024.99
#Sta/Elev= 30
  4312.0  337.60  4440.9  332.33  4451.0  332.47  4486.9  330.14  4491.9  330.49
  4511.3  329.32  4521.3  329.47  4639.9  324.71  4682.0  322.93  4762.9  321.38
  4841.9  320.74  4870.0  320.47  4977.2  319.66  4990.1  319.26  5008.0  317.20
  5013.5  317.51  5044.3  315.82  5050.7  314.31  5050.9  313.81  5054.4  313.81
  5054.7  314.31  5058.3  315.09  5066.7  318.97  5080.6  320.74  5097.4  320.38
  5147.7  323.38  5156.1  324.52  5196.8  326.44  5214.8  326.86  5223.2  327.65
#Mann=9,-1,0
  4312.0    0.07       0  4639.9    0.12       0  4762.9    0.07       0
  4841.9    0.12       0  4870.0    0.07       0  4977.2    0.12       0
  5050.7    0.05       0  5054.7    0.12       0  5196.8    0.07       0
Bank Sta=5050.7,5054.7
Exp/Cntr=0.3,0.1

Type RM Length L Ch R = 1,19251,441,441,441
BEGIN DESCRIPTION:
Stream0804 42.0
END DESCRIPTION:
XS GIS Cut Line= 3
      2449375.00     13577025.00      2449775.00     13576625.00
      2450024.98     13576475.01
#Sta/Elev= 30
  4430.4  339.19  4458.7  338.17  4487.0  335.72  4586.0  330.01  4600.1  328.50
  4614.2  328.53  4642.5  326.19  4674.8  324.61  4727.4  322.83  4741.5  321.72
  4755.7  322.08  4769.8  320.90  4779.7  320.87  4802.2  319.84  4911.2  319.28
  4939.5  316.93  4999.0  314.48  5003.9  308.25  5007.6  308.14  5007.9  307.64
  5011.5  307.64  5011.7  308.14  5019.4  311.89  5031.1  313.18  5040.8  312.93
  5062.2  316.04  5068.0  316.31  5077.7  318.16  5188.2  321.72  5287.6  326.07
#Mann=7,-1,0
  4430.4    0.07       0  4674.8    0.16       0  4779.7    0.07       0
  4802.2    0.16       0  5007.6    0.07       0  5011.7    0.16       0
  5188.2    0.07       0
Bank Sta=5007.6,5011.7
Exp/Cntr=0.3,0.1

Type RM Length L Ch R = 1,18810,425,425,425
BEGIN DESCRIPTION:
Stream0804 41.0
END DESCRIPTION:
XS GIS Cut Line= 3
      2449375.02     13577624.98      2450075.00     13576925.00
      2450125.00     13576525.04
#Sta/Elev= 30
  4005.7  350.21  4009.2  350.21  4019.8  352.99  4048.1  355.37  4062.2  354.60
  4076.4  351.60  4090.5  351.01  4104.7  349.11  4118.8  344.54  4133.0  342.77
  4260.2  337.62  4316.8  333.97  4606.7  321.79  4712.8  316.35  4769.3  314.48
  4854.5  314.88  4910.8  315.40  4939.1  314.59  4967.3  307.81  4979.4  306.62
  4979.7  306.12  4983.5  306.62  4992.1  310.28  5038.5  311.05  5076.2  315.34
  5106.5  316.19  5141.5  315.83  5354.9  324.31  5398.6  325.84  5398.7  325.84
#Mann=7,-1,0
  4005.7    0.07       0  4854.5    0.16       0  4979.4    0.07       0
  4983.5    0.16       0  5141.5    0.07       0  5354.9   0.035       0
  5398.6    0.07       0
Bank Sta=4979.4,4983.5
Exp/Cntr=0.3,0.1

Type RM Length L Ch R = 1,18385,483,483,483
BEGIN DESCRIPTION:
Stream0804 40.0
END DESCRIPTION:
XS GIS Cut Line= 3
      2449625.02     13577674.99      2450425.00     13577125.00
      2450824.99     13577175.00
#Sta/Elev= 30
  4029.2  339.45  4178.3  332.84  4502.7  319.25  4805.8  312.91  4819.3  310.66
  4828.2  307.62  4834.2  308.08  4842.2  306.18  4864.0  306.98  4870.1  305.87
  4878.6  306.74  4885.0  310.09  4920.8  309.39  4935.7  311.93  4941.8  309.53
  4963.6  305.80  4968.8  298.75  4969.2  298.25  4974.4  298.75  4992.6  300.08
  4997.0  305.72  5010.1  304.97  5037.8  312.19  5042.8  311.66  5088.1  316.77
  5186.9  319.50  5204.1  318.80  5231.8  323.31  5285.7  325.75  5403.1  333.07
#Mann=7,-1,0
  4029.2    0.07       0  4178.3    0.16       0  4968.8    0.07       0
  4974.4    0.16       0  5088.1    0.07       0  5186.9   0.035       0
  5285.7    0.07       0
Bank Sta=4968.8,4974.4
Exp/Cntr=0.3,0.1

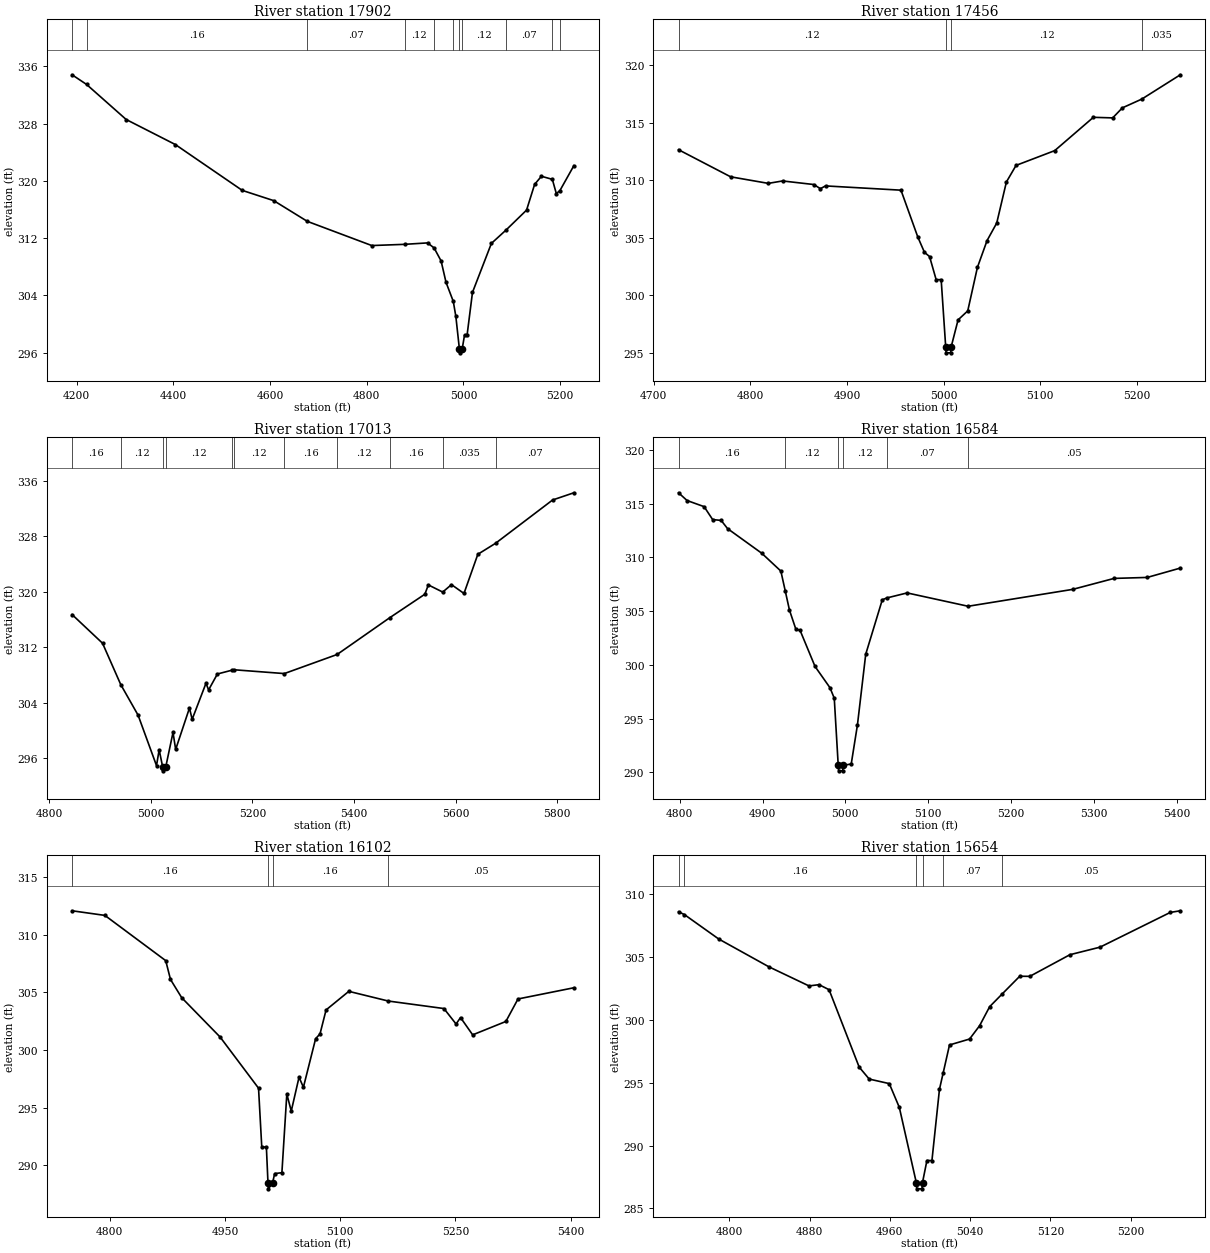
Type RM Length L Ch R = 1,17902,446,446,446
BEGIN DESCRIPTION:
Stream0804 39.0
END DESCRIPTION:
XS GIS Cut Line= 3
      2449725.05     13577724.99      2450525.00     13577575.00
      2450725.00     13577475.00
#Sta/Elev= 30
  4190.8  334.81  4220.8  333.46  4302.7  328.56  4404.4  325.06  4542.6  318.66
  4607.9  317.22  4677.2  314.33  4810.5  310.95  4878.4  311.12  4925.8  311.32
  4939.3  310.62  4953.8  308.80  4964.0  305.81  4979.0  303.15  4984.3  301.05
  4991.7  296.46  4992.2  295.96  4997.3  296.46  5002.2  298.42  5007.5  298.42
  5018.7  304.41  5057.8  311.25  5087.8  313.10  5130.5  315.90  5147.2  319.50
  5161.2  320.63  5183.8  320.20  5192.0  318.22  5199.3  318.61  5228.3  322.11
#Mann=11,-1,0
  4190.8    0.07       0  4220.8    0.16       0  4677.2    0.07       0
  4878.4    0.12       0  4939.3    0.16       0  4979.0    0.12       0
  4991.7    0.07       0  4997.3    0.12       0  5087.8    0.07       0
  5183.8   0.035       0  5199.3    0.07       0
Bank Sta=4991.7,4997.3
Exp/Cntr=0.3,0.1

Type RM Length L Ch R = 1,17456,443,443,443
BEGIN DESCRIPTION:
Stream0804 38.0
END DESCRIPTION:
XS GIS Cut Line= 3
      2450225.00     13577875.00      2450475.00     13577975.00
      2450725.04     13577975.00
#Sta/Elev= 30
  4725.7  312.64  4779.6  310.29  4818.6  309.72  4833.4  309.93  4865.7  309.62
  4872.5  309.26  4877.8  309.50  4955.9  309.13  4973.4  305.05  4980.2  303.74
  4985.5  303.37  4992.3  301.37  4997.5  301.37  5002.2  295.52  5002.6  295.02
  5007.3  295.02  5007.8  295.52  5015.0  297.88  5025.0  298.66  5035.0  302.43
  5045.0  304.76  5055.0  306.28  5065.0  309.84  5075.0  311.28  5115.0  312.56
  5155.0  315.45  5175.0  315.40  5185.0  316.27  5205.1  317.03  5245.0  319.14
#Mann=4,-1,0
  4725.7    0.12       0  5002.2    0.07       0  5007.8    0.12       0
  5205.1   0.035       0
Bank Sta=5002.2,5007.8
Exp/Cntr=0.3,0.1

Type RM Length L Ch R = 1,17013,429,429,429
BEGIN DESCRIPTION:
Stream0804 37.0
END DESCRIPTION:
XS GIS Cut Line= 3
      2450074.97     13578325.00      2450225.00     13578325.00
      2451025.01     13578075.00
#Sta/Elev= 30
  4844.7  316.73  4904.7  312.60  4940.6  306.64  4974.7  302.24  5011.0  294.97
  5016.2  297.25  5023.3  294.72  5023.8  294.22  5029.0  294.72  5043.5  299.75
  5048.7  297.30  5075.9  303.27  5081.2  301.64  5108.4  306.83  5113.6  305.88
  5130.9  308.17  5158.7  308.70  5163.3  308.78  5262.7  308.23  5366.7  310.98
  5470.6  316.29  5539.5  319.66  5546.3  321.00  5574.6  319.97  5591.9  321.04
  5616.5  319.77  5643.8  325.41  5678.6  326.99  5791.0  333.23  5832.9  334.27
#Mann=11,-1,0
  4844.7    0.16       0  4940.6    0.12       0  5023.3    0.07       0
  5029.0    0.12       0  5158.7    0.07       0  5163.3    0.12       0
  5262.7    0.16       0  5366.7    0.12       0  5470.6    0.16       0
  5574.6   0.035       0  5678.6    0.07       0
Bank Sta=5023.3,5029
Exp/Cntr=0.3,0.1

Type RM Length L Ch R = 1,16584,482,482,482
BEGIN DESCRIPTION:
Stream0804 36.0
END DESCRIPTION:
XS GIS Cut Line= 3
      2450025.05     13578675.01      2450225.00     13578725.00
      2450624.99     13578725.00
#Sta/Elev= 30
  4798.5  316.00  4808.8  315.28  4829.4  314.71  4839.7  313.51  4850.0  313.43
  4857.7  312.67  4899.0  310.38  4922.1  308.72  4927.3  306.91  4932.5  305.09
  4940.2  303.32  4945.3  303.21  4963.4  299.85  4981.4  297.88  4986.6  296.90
  4991.4  290.65  4991.9  290.15  4996.7  290.15  4997.1  290.65  5007.1  290.79
  5014.6  294.42  5024.6  300.99  5044.6  306.05  5049.9  306.22  5074.6  306.69
  5148.3  305.45  5274.6  307.02  5324.6  308.04  5364.6  308.13  5404.6  309.00
#Mann=6,-1,0
  4798.5    0.16       0  4927.3    0.12       0  4991.4    0.07       0
  4997.1    0.12       0  5049.9    0.07       0  5148.3    0.05       0
Bank Sta=4991.4,4997.1
Exp/Cntr=0.3,0.1

Type RM Length L Ch R = 1,16102,448,448,448
BEGIN DESCRIPTION:
Stream0804 35.0
END DESCRIPTION:
XS GIS Cut Line= 3
      2449924.99     13579024.99      2450125.00     13579175.00
      2450474.97     13578975.02
#Sta/Elev= 30
  4751.0  312.06  4793.7  311.66  4872.9  307.74  4879.1  306.11  4893.7  304.53
  4943.7  301.12  4993.7  296.69  4997.9  291.59  5003.9  291.59  5006.0  288.47
  5006.5  287.97  5011.9  288.47  5014.7  289.29  5024.1  289.37  5030.5  296.18
  5036.3  294.71  5046.4  297.64  5052.1  296.77  5068.0  300.98  5073.7  301.39
  5081.6  303.47  5111.2  305.08  5162.6  304.24  5235.0  303.59  5250.8  302.25
  5256.6  302.81  5272.4  301.31  5315.6  302.47  5331.4  304.42  5404.1  305.39
#Mann=4,-1,0
  4751.0    0.16       0  5006.0    0.07       0  5011.9    0.16       0
  5162.6    0.05       0
Bank Sta=5006,5011.9
Exp/Cntr=0.3,0.1

Type RM Length L Ch R = 1,15654,482,482,482
BEGIN DESCRIPTION:
Stream0804 34.0
END DESCRIPTION:
XS GIS Cut Line= 3
      2450024.97     13579575.00      2450275.00     13579575.00
      2450524.97     13579575.00
#Sta/Elev= 30
  4749.5  308.57  4755.3  308.35  4789.5  306.41  4839.5  304.20  4879.5  302.68
  4889.5  302.78  4899.5  302.38  4929.5  296.23  4939.5  295.28  4959.5  294.92
  4969.5  293.03  4986.4  287.06  4986.9  286.56  4992.1  286.56  4992.6  287.06
  4997.0  288.81  5002.0  288.81  5009.5  294.47  5013.2  295.77  5019.5  297.99
  5039.5  298.46  5049.5  299.52  5059.5  301.03  5071.6  302.01  5089.5  303.45
  5099.5  303.44  5139.5  305.16  5169.5  305.76  5239.5  308.52  5249.5  308.65
#Mann=6,-1,0
  4749.5    0.07       0  4755.3    0.16       0  4986.4    0.07       0
  4992.6    0.16       0  5013.2    0.07       0  5071.6    0.05       0
Bank Sta=4986.4,4992.6
Exp/Cntr=0.3,0.1

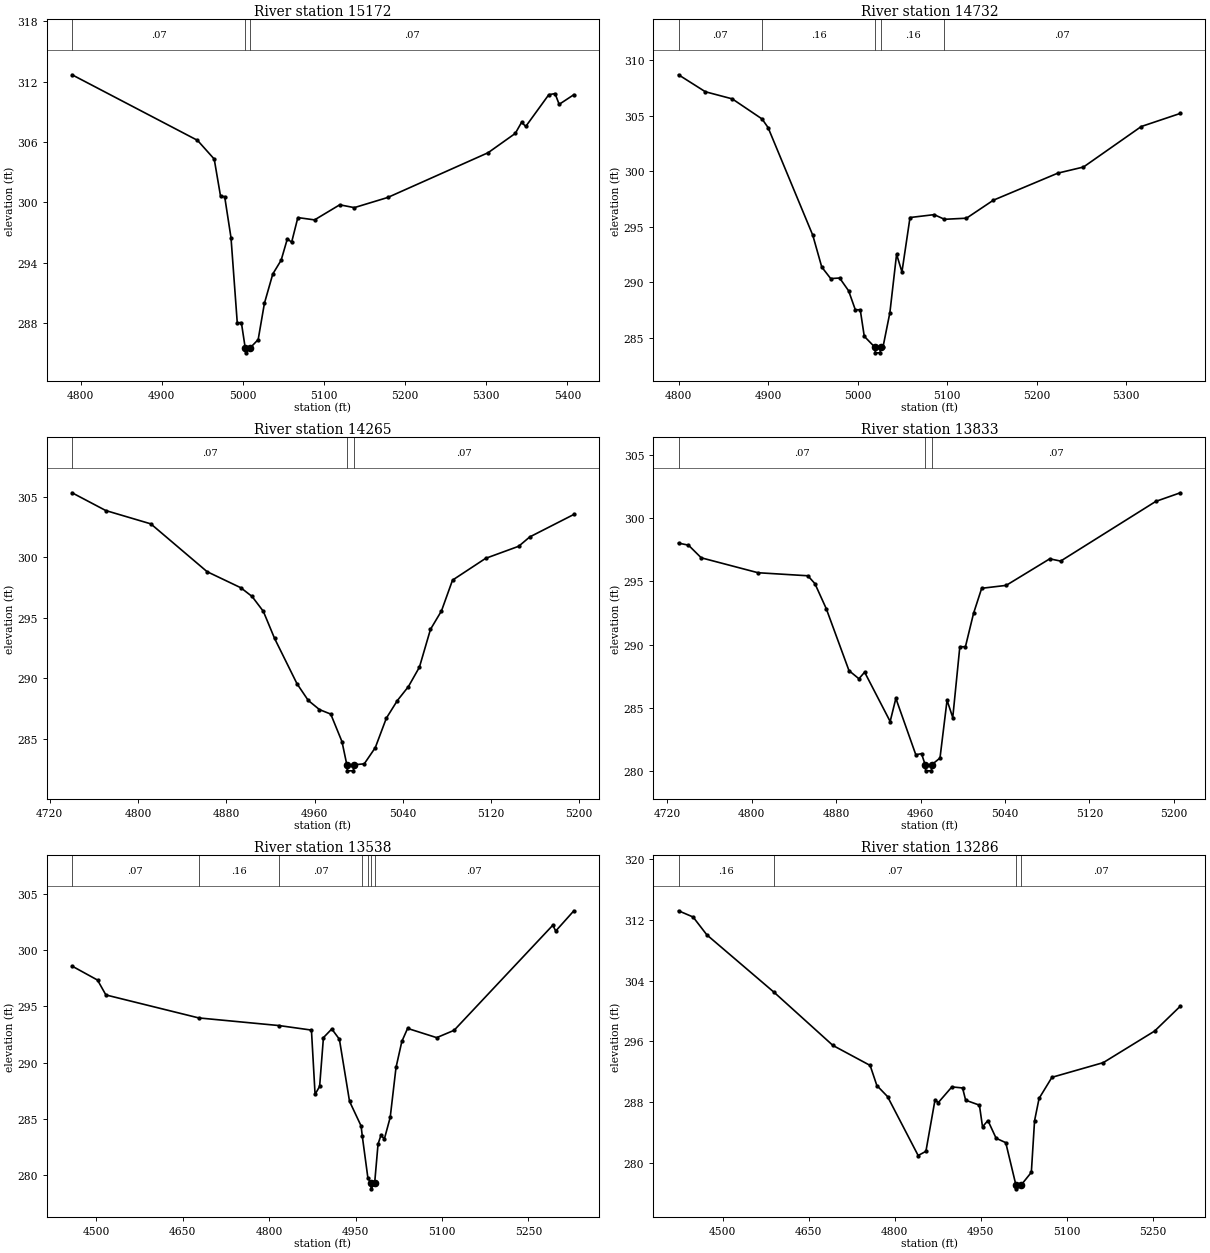
Type RM Length L Ch R = 1,15172,440,440,440
BEGIN DESCRIPTION:
Stream0804 33.0
END DESCRIPTION:
XS GIS Cut Line= 3
      2449974.99     13579975.00      2450175.00     13580025.00
      2450575.03     13579924.99
#Sta/Elev= 30
  4789.5  312.69  4944.1  306.17  4964.7  304.31  4972.5  300.62  4977.6  300.57
  4985.4  296.49  4993.1  288.04  4998.2  288.04  5002.9  285.54  5003.4  285.04
  5009.1  285.54  5018.9  286.36  5026.6  289.97  5036.9  292.88  5047.2  294.25
  5054.9  296.39  5060.1  296.03  5067.8  298.49  5088.4  298.26  5119.4  299.76
  5137.4  299.48  5178.6  300.49  5302.3  304.94  5335.8  306.86  5343.6  307.97
  5348.7  307.55  5377.1  310.71  5384.8  310.82  5389.9  309.75  5408.0  310.71
#Mann=3,-1,0
  4789.5    0.07       0  5002.9    0.07       0  5009.1    0.07       0
Bank Sta=5002.9,5009.1
Exp/Cntr=0.3,0.1

Type RM Length L Ch R = 1,14732,467,467,467
BEGIN DESCRIPTION:
Stream0804 32.0
END DESCRIPTION:
XS GIS Cut Line= 3
      2450025.00     13580425.00      2450225.00     13580425.00
      2450525.04     13580224.98
#Sta/Elev= 30
  4800.0  308.68  4830.0  307.15  4860.0  306.51  4893.3  304.70  4900.0  303.93
  4950.0  294.22  4960.0  291.36  4970.0  290.32  4980.0  290.37  4990.0  289.22
  4997.5  287.51  5003.0  287.51  5007.5  285.12  5019.4  284.13  5019.9  283.63
  5025.2  283.63  5025.7  284.13  5028.5  284.18  5036.1  287.24  5043.6  292.51
  5049.6  290.92  5058.6  295.82  5085.6  296.08  5097.1  295.66  5121.7  295.76
  5151.7  297.38  5223.8  299.82  5252.4  300.37  5317.0  304.02  5360.6  305.20
#Mann=5,-1,0
  4800.0    0.07       0  4893.3    0.16       0  5019.4    0.07       0
  5025.7    0.16       0  5097.1    0.07       0
Bank Sta=5019.4,5025.7
Exp/Cntr=0.3,0.1

Type RM Length L Ch R = 1,14265,432,432,432
BEGIN DESCRIPTION:
Stream0804 31.0
END DESCRIPTION:
XS GIS Cut Line= 3
      2450025.01     13580825.00      2450275.00     13580875.00
      2450474.96     13580875.00
#Sta/Elev= 30
  4740.2  305.31  4770.8  303.84  4811.6  302.74  4862.6  298.79  4893.2  297.46
  4903.4  296.74  4913.6  295.51  4923.8  293.27  4944.1  289.53  4954.3  288.15
  4964.5  287.39  4974.7  287.02  4984.9  284.74  4989.3  282.83  4989.8  282.33
  4995.3  282.33  4995.8  282.83  5005.1  282.91  5015.1  284.25  5025.1  286.68
  5035.1  288.14  5045.1  289.29  5055.1  290.90  5065.1  294.02  5075.1  295.55
  5085.1  298.09  5115.1  299.89  5145.1  300.89  5155.1  301.66  5195.1  303.52
#Mann=3,-1,0
  4740.2    0.07       0  4989.3    0.07       0  4995.8    0.07       0
Bank Sta=4989.3,4995.8
Exp/Cntr=0.3,0.1

Type RM Length L Ch R = 1,13833,295,295,295
BEGIN DESCRIPTION:
Stream0804 30.0
END DESCRIPTION:
XS GIS Cut Line= 3
      2449975.05     13581125.02      2450225.00     13581225.00
      2450425.03     13581174.99
#Sta/Elev= 30
  4730.7  298.03  4740.1  297.87  4752.2  296.87  4806.0  295.69  4853.2  295.45
  4859.9  294.83  4870.7  292.84  4892.2  287.95  4901.6  287.31  4907.0  287.83
  4931.2  283.93  4936.6  285.76  4955.5  281.30  4960.9  281.39  4964.3  280.53
  4964.8  280.03  4970.3  280.03  4970.8  280.53  4978.4  281.04  4985.1  285.61
  4990.5  284.24  4997.2  289.84  5002.5  289.84  5010.2  292.48  5017.9  294.46
  5041.1  294.69  5082.4  296.79  5092.7  296.61  5182.9  301.33  5206.1  302.01
#Mann=3,-1,0
  4730.7    0.07       0  4964.3    0.07       0  4970.8    0.07       0
Bank Sta=4964.3,4970.8
Exp/Cntr=0.3,0.1

Type RM Length L Ch R = 1,13538,252,252,252
BEGIN DESCRIPTION:
H21082
END DESCRIPTION:
XS GIS Cut Line= 3
      2449862.99     13581145.02      2450145.27     13581510.33
      2450551.05     13581564.16
#Sta/Elev= 30
  4457.9  298.56  4502.1  297.32  4516.6  296.00  4677.8  293.96  4817.5  293.28
  4873.4  292.88  4879.7  287.18  4887.6  287.88  4894.2  292.21  4908.7  292.98
  4921.9  292.07  4939.5  286.56  4959.6  284.37  4961.7  283.45  4971.3  279.79
  4976.5  279.29  4977.0  278.79  4983.1  279.29  4989.0  282.76  4994.0  283.54
  5000.0  283.22  5010.1  285.13  5020.2  289.56  5030.3  291.87  5040.3  293.03
  5090.8  292.21  5121.0  292.86  5292.4  302.19  5297.4  301.67  5328.9  303.47
#Mann=7,-1,0
  4457.9    0.07       0  4677.8    0.16       0  4817.5    0.07       0
  4961.7    0.16       0  4971.3    0.07       0  4976.5    0.07       0
  4983.1    0.07       0
Bank Sta=4976.5,4983.1
Exp/Cntr=0.3,0.1

Type RM Length L Ch R = 1,13286,421,421,421
BEGIN DESCRIPTION:
Stream0804 29.0
END DESCRIPTION:
XS GIS Cut Line= 3
      2449725.98     13581979.40      2450232.44     13581771.84
      2450525.02     13581624.99
#Sta/Elev= 30
  4423.3  313.17  4448.7  312.35  4472.7  310.00  4590.1  302.44  4692.4  295.47
  4757.3  292.84  4769.0  290.20  4787.6  288.75  4841.0  281.00  4854.5  281.55
  4870.4  288.32  4876.1  287.96  4899.8  290.02  4918.4  289.88  4923.8  288.27
  4947.8  287.62  4953.2  284.77  4962.6  285.60  4976.9  283.27  4993.7  282.69
  5011.4  277.12  5011.9  276.62  5020.5  277.12  5038.3  278.79  5043.9  285.57
  5051.8  288.51  5074.2  291.28  5163.7  293.21  5253.2  297.36  5298.0  300.63
#Mann=4,-1,0
  4423.3    0.16       0  4590.1    0.07       0  5011.4    0.07       0
  5020.5    0.07       0
Bank Sta=5011.4,5020.5
Exp/Cntr=0.3,0.1

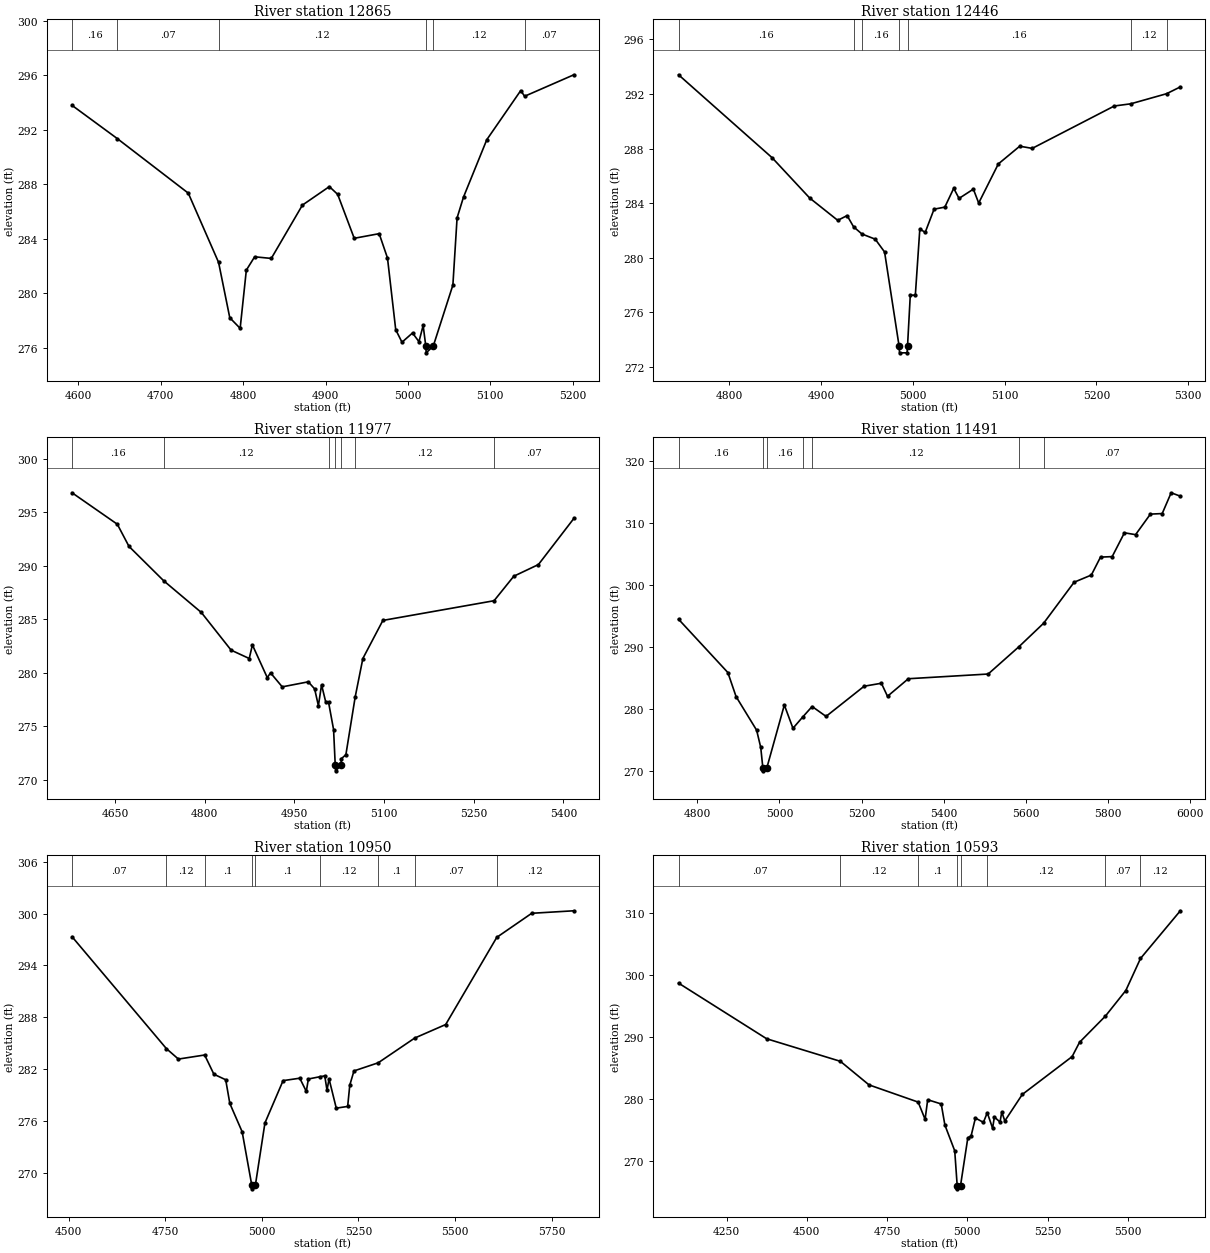
Type RM Length L Ch R = 1,12865,419,419,419
BEGIN DESCRIPTION:
Stream0804 28.0
END DESCRIPTION:
XS GIS Cut Line= 3
      2450025.00     13582125.00      2450425.00     13582075.00
      2450625.03     13582125.01
#Sta/Elev= 30
  4592.2  293.80  4647.1  291.36  4733.3  287.35  4770.1  282.26  4783.7  278.19
  4796.3  277.41  4803.8  281.69  4813.9  282.67  4834.1  282.55  4871.9  286.47
  4904.6  287.83  4914.7  287.26  4934.8  284.03  4965.1  284.37  4975.2  282.58
  4985.2  277.31  4992.8  276.39  5005.6  277.07  5013.4  276.43  5018.5  277.62
  5021.7  276.11  5022.2  275.61  5030.8  276.11  5054.6  280.59  5059.7  285.53
  5067.5  287.06  5095.8  291.28  5137.0  294.89  5141.7  294.47  5201.5  296.05
#Mann=6,-1,0
  4592.2    0.16       0  4647.1    0.07       0  4770.1    0.12       0
  5021.7    0.07       0  5030.8    0.12       0  5141.7    0.07       0
Bank Sta=5021.7,5030.8
Exp/Cntr=0.3,0.1

Type RM Length L Ch R = 1,12446,469,469,469
BEGIN DESCRIPTION:
Stream0804 27.0
END DESCRIPTION:
XS GIS Cut Line= 3
      2450074.96     13582374.99      2450325.00     13582425.00
      2450574.96     13582275.02
#Sta/Elev= 30
  4744.9  293.41  4846.9  287.32  4887.7  284.37  4918.3  282.73  4928.5  283.08
  4935.5  282.26  4944.6  281.73  4959.1  281.35  4969.3  280.41  4985.1  273.51
  4985.6  273.01  4993.8  273.01  4994.3  273.51  4997.3  277.24  5002.8  277.24
  5007.7  282.11  5013.5  281.84  5023.2  283.55  5034.9  283.70  5044.6  285.08
  5050.4  284.34  5066.0  285.02  5071.8  284.00  5093.2  286.87  5116.5  288.17
  5130.1  288.01  5219.5  291.12  5237.4  291.28  5276.4  292.02  5291.4  292.52
#Mann=7,-1,0
  4744.9    0.16       0  4935.5    0.12       0  4944.6    0.16       0
  4985.1    0.07       0  4994.3    0.16       0  5237.4    0.12       0
  5276.4    0.05       0
Bank Sta=4985.1,4994.3
Exp/Cntr=0.3,0.1

Type RM Length L Ch R = 1,11977,486,486,486
BEGIN DESCRIPTION:
Stream0804 26.0
END DESCRIPTION:
XS GIS Cut Line= 3
      2449975.00     13583025.00      2450375.00     13582875.00
      2450774.99     13582775.00
#Sta/Elev= 30
  4578.0  296.82  4653.7  293.88  4673.2  291.81  4731.2  288.60  4794.3  285.63
  4844.1  282.11  4874.4  281.33  4879.7  282.60  4904.6  279.54  4910.0  279.99
  4929.6  278.68  4973.2  279.15  4983.8  278.49  4990.1  276.92  4995.4  278.87
  5002.5  277.24  5007.1  277.24  5015.5  274.69  5018.3  271.33  5018.8  270.83
  5028.1  271.33  5028.4  271.96  5036.1  272.34  5051.7  277.75  5064.5  281.33
  5098.0  284.89  5284.0  286.73  5317.0  289.02  5358.2  290.11  5417.5  294.42
#Mann=7,-1,0
  4578.0    0.16       0  4731.2    0.12       0  5007.1    0.16       0
  5018.3    0.07       0  5028.1    0.16       0  5051.7    0.12       0
  5284.0    0.07       0
Bank Sta=5018.3,5028.1
Exp/Cntr=0.3,0.1

Type RM Length L Ch R = 1,11491,541,541,541
BEGIN DESCRIPTION:
Stream0804 25.0
END DESCRIPTION:
XS GIS Cut Line= 3
      2450025.03     13583325.00      2450275.00     13583325.00
      2451075.00     13582775.00
#Sta/Elev= 30
  4754.6  294.49  4874.6  285.87  4894.6  281.98  4944.6  276.55  4954.6  273.76
  4959.7  270.48  4960.2  269.98  4969.5  270.48  5012.0  280.62  5033.0  276.86
  5057.2  278.72  5079.6  280.38  5113.5  278.78  5206.2  283.66  5248.1  284.14
  5263.0  282.03  5313.7  284.87  5507.9  285.63  5583.0  290.06  5642.8  293.84
  5717.0  300.47  5758.9  301.63  5781.2  304.53  5809.6  304.61  5839.4  308.46
  5866.5  308.16  5902.6  311.48  5931.3  311.57  5953.1  314.93  5975.4  314.38
#Mann=7,-1,0
  4754.6    0.16       0  4959.7    0.07       0  4969.5    0.16       0
  5057.2    0.07       0  5079.6    0.12       0  5583.0    0.16       0
  5642.8    0.07       0
Bank Sta=4959.7,4969.5
Exp/Cntr=0.3,0.1

Type RM Length L Ch R = 1,10950,357,357,357
BEGIN DESCRIPTION:
Stream0804 24.0
END DESCRIPTION:
XS GIS Cut Line= 3
      2449975.11     13583809.96      2450406.78     13583722.80
      2451202.53     13583399.52
#Sta/Elev= 30
  4508.5  297.32  4752.7  284.40  4783.8  283.19  4851.8  283.66  4875.7  281.44
  4906.3  280.80  4917.0  278.06  4948.9  274.79  4973.5  268.70  4974.0  268.20
  4983.4  268.70  5007.9  275.81  5054.9  280.70  5098.1  280.98  5115.0  279.46
  5120.4  280.89  5150.3  281.15  5162.8  281.25  5168.6  279.59  5173.9  280.90
  5192.6  277.52  5222.1  277.72  5227.6  280.18  5238.4  281.82  5301.2  282.76
  5395.8  285.62  5475.9  287.18  5608.2  297.25  5698.7  300.03  5807.8  300.32
#Mann=9,-1,0
  4508.5    0.07       0  4752.7    0.12       0  4851.8     0.1       0
  4973.5    0.05       0  4983.4     0.1       0  5150.3    0.12       0
  5301.2     0.1       0  5395.8    0.07       0  5608.2    0.12       0
Bank Sta=4973.5,4983.4
Exp/Cntr=0.3,0.1

Type RM Length L Ch R = 1,10593,470,470,470
BEGIN DESCRIPTION:
Stream0804 23.0
END DESCRIPTION:
XS GIS Cut Line= 5
      2449847.88     13584141.03      2450700.12     13583937.44
      2450725.00     13583925.00      2450743.26     13583911.30
      2451323.21     13583649.41
#Sta/Elev= 30
  4100.3  298.64  4374.9  289.68  4604.6  286.05  4693.7  282.26  4846.8  279.49
  4868.4  276.72  4876.5  279.87  4918.6  279.19  4930.1  275.79  4960.7  271.65
  4968.4  266.03  4968.9  265.53  4978.7  266.03  5001.5  273.74  5011.6  274.02
  5025.1  276.92  5050.1  276.23  5062.1  277.78  5078.7  275.28  5084.2  277.09
  5101.8  276.28  5107.3  277.89  5116.8  276.46  5171.2  280.72  5326.4  286.81
  5349.5  289.11  5430.1  293.33  5493.7  297.45  5539.4  302.60  5663.5  310.28
#Mann=8,-1,0
  4100.3    0.07       0  4604.6    0.12       0  4846.8     0.1       0
  4968.4    0.05       0  4978.7     0.1       0  5062.1    0.12       0
  5430.1    0.07       0  5539.4    0.12       0
Bank Sta=4968.4,4978.7
Exp/Cntr=0.3,0.1