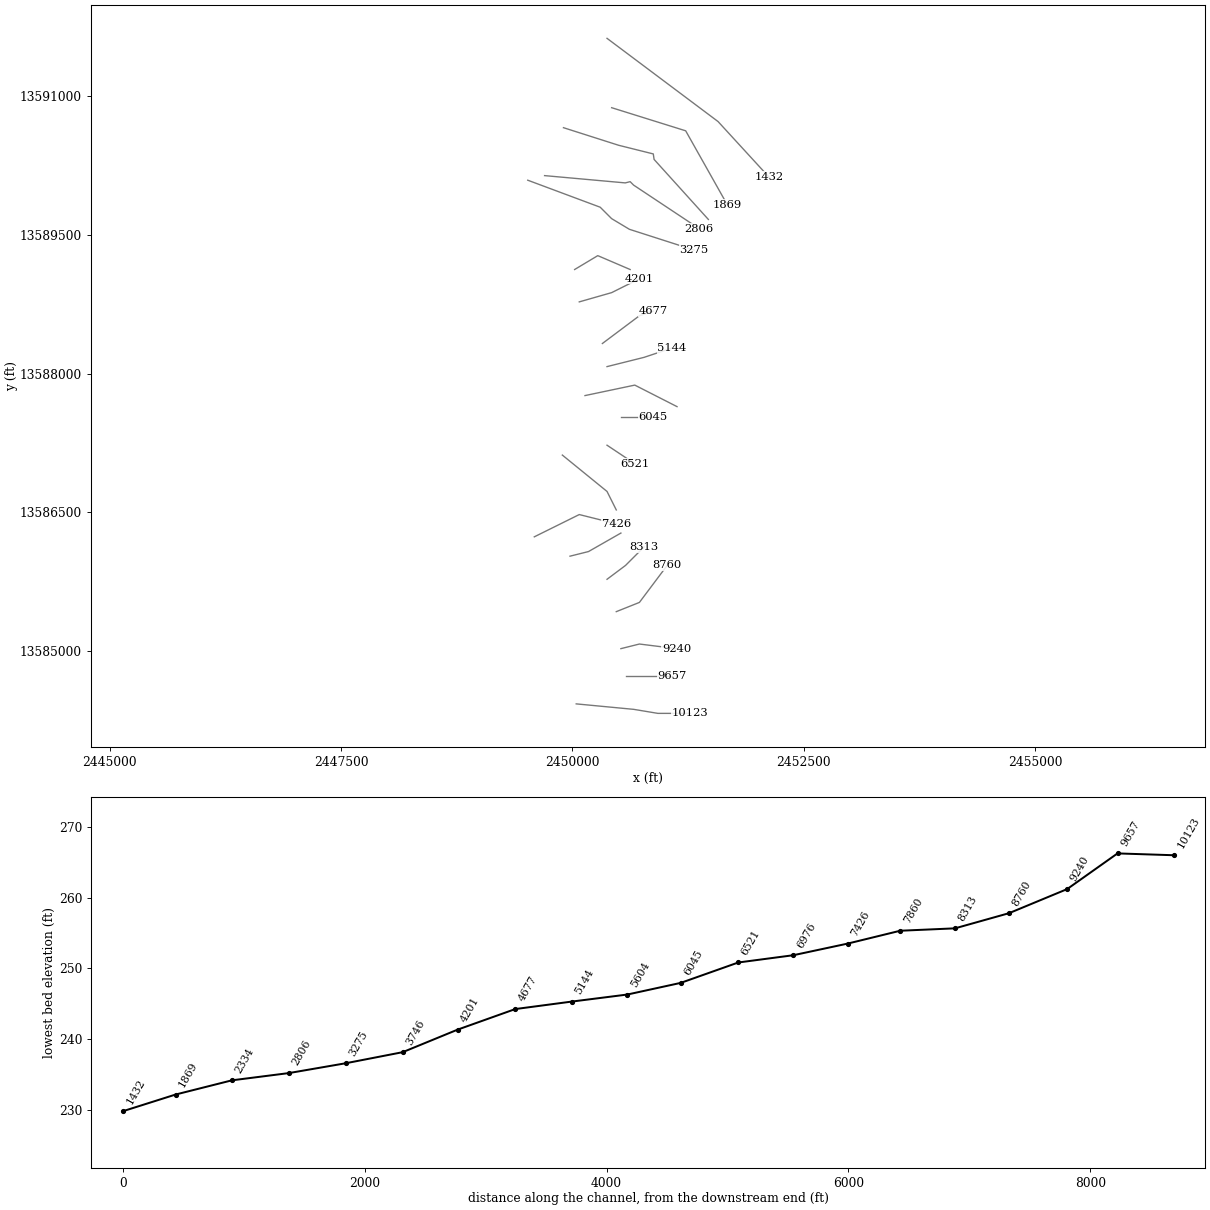
HEC-RAS study Stream0804.prj: Stream0804 Base Level Engineering

--- Stream0804.g01 (geometry) --- (continued)

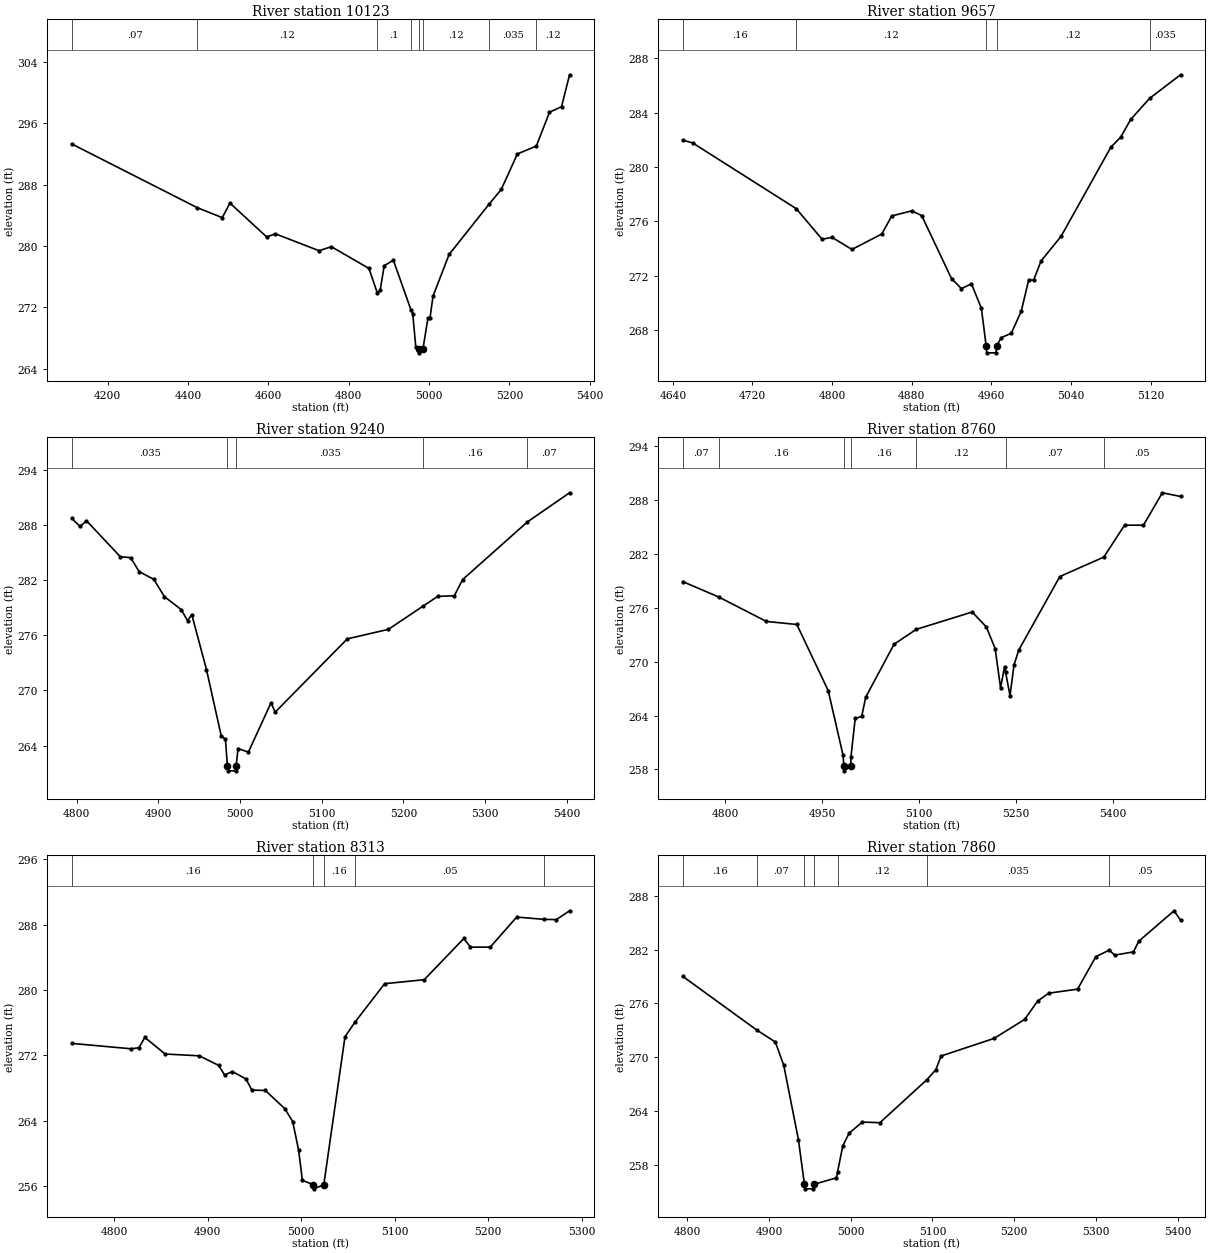
Type RM Length L Ch R = 1,10123,466,466,466
BEGIN DESCRIPTION:
Stream0804 22.0
END DESCRIPTION:
XS GIS Cut Line= 4
      2450041.89     13584427.69      2450664.16     13584368.47
      2450925.00     13584325.00      2451274.98     13584325.00
#Sta/Elev= 30
  4110.3  293.32  4422.8  285.00  4485.1  283.70  4504.2  285.60  4595.6  281.18
  4617.2  281.59  4726.2  279.38  4756.5  279.91  4850.3  277.07  4871.3  273.83
  4878.2  274.22  4888.3  277.43  4911.1  278.14  4954.9  271.65  4959.3  271.14
  4966.9  266.82  4974.4  266.55  4974.9  266.05  4984.7  266.55  4997.3  270.62
  5002.3  270.62  5009.8  273.45  5049.8  278.89  5149.1  285.44  5179.8  287.39
  5219.8  292.01  5267.1  293.05  5299.8  297.46  5329.8  298.19  5349.8  302.35
#Mann=8,-1,0
  4110.3    0.07       0  4422.8    0.12       0  4871.3     0.1       0
  4954.9    0.12       0  4974.4    0.05       0  4984.7    0.12       0
  5149.1   0.035       0  5267.1    0.12       0
Bank Sta=4974.4,4984.7
Exp/Cntr=0.3,0.1

Type RM Length L Ch R = 1,9657,417,417,417
BEGIN DESCRIPTION:
Stream0804 21.0
END DESCRIPTION:
XS GIS Cut Line= 3
      2450575.00     13584725.00      2450925.00     13584725.00
      2451075.00     13584725.00
#Sta/Elev= 30
  4649.9  281.98  4659.9  281.78  4764.0  276.93  4789.9  274.68  4799.9  274.82
  4819.9  273.93  4849.9  275.07  4859.9  276.40  4879.9  276.77  4889.9  276.43
  4919.9  271.78  4929.9  271.04  4939.9  271.40  4949.9  269.59  4954.7  266.81
  4955.2  266.31  4964.6  266.31  4965.1  266.81  4969.9  267.43  4979.9  267.75
  4989.9  269.37  4997.4  271.68  5002.4  271.68  5009.9  273.09  5029.9  274.89
  5079.9  281.46  5089.9  282.21  5099.9  283.51  5118.8  285.06  5149.9  286.80
#Mann=5,-1,0
  4649.9    0.16       0  4764.0    0.12       0  4954.7    0.07       0
  4965.1    0.12       0  5118.8   0.035       0
Bank Sta=4954.7,4965.1
Exp/Cntr=0.3,0.1

Type RM Length L Ch R = 1,9240,480,480,480
BEGIN DESCRIPTION:
Stream0804 20.0
END DESCRIPTION:
XS GIS Cut Line= 3
      2450525.01     13585025.00      2450725.00     13585075.00
      2451125.04     13585025.00
#Sta/Elev= 30
  4794.0  288.74  4804.3  287.86  4812.0  288.49  4853.3  284.58  4866.1  284.46
  4876.5  282.95  4894.5  282.10  4907.4  280.22  4928.0  278.81  4935.7  277.60
  4940.9  278.27  4958.9  272.28  4977.0  265.04  4982.1  264.70  4984.5  261.75
  4985.0  261.25  4994.6  261.25  4995.1  261.75  4997.6  263.67  5010.2  263.29
  5037.9  268.66  5043.0  267.64  5131.2  275.62  5181.6  276.66  5224.2  279.20
  5242.0  280.25  5262.2  280.31  5272.3  282.07  5351.6  288.35  5403.3  291.53
#Mann=5,-1,0
  4794.0   0.035       0  4984.5   0.035       0  4995.1   0.035       0
  5224.2    0.16       0  5351.6    0.07       0
Bank Sta=4984.5,4995.1
Exp/Cntr=0.3,0.1

Type RM Length L Ch R = 1,8760,447,447,447
BEGIN DESCRIPTION:
Stream0804 19.0
END DESCRIPTION:
XS GIS Cut Line= 3
      2450474.96     13585424.99      2450725.00     13585525.00
      2451025.00     13585925.00
#Sta/Elev= 30
  4734.8  278.92  4790.3  277.21  4864.1  274.48  4911.2  274.14  4959.7  266.77
  4982.6  259.58  4983.9  258.34  4984.4  257.84  4994.6  258.34  4994.7  259.33
  5001.4  263.67  5011.4  263.90  5017.6  266.04  5061.4  271.94  5095.8  273.60
  5182.2  275.53  5204.1  273.86  5217.6  271.46  5226.0  267.10  5232.2  269.43
  5233.7  268.86  5240.6  266.21  5246.8  269.64  5254.1  271.29  5317.6  279.48
  5385.6  281.65  5417.6  285.20  5446.8  285.20  5476.0  288.81  5504.1  288.40
#Mann=7,-1,0
  4734.8    0.07       0  4790.3    0.16       0  4983.9    0.07       0
  4994.6    0.16       0  5095.8    0.12       0  5233.7    0.07       0
  5385.6    0.05       0
Bank Sta=4983.9,4994.6
Exp/Cntr=0.3,0.1

Type RM Length L Ch R = 1,8313,453,453,453
BEGIN DESCRIPTION:
Stream0804 18.0
END DESCRIPTION:
XS GIS Cut Line= 3
      2450374.97     13585774.97      2450575.00     13585925.00
      2450775.01     13586125.01
#Sta/Elev= 30
  4754.3  273.48  4817.9  272.82  4826.2  272.95  4832.5  274.21  4854.3  272.18
  4890.8  271.96  4911.6  270.79  4917.9  269.61  4926.2  270.04  4940.8  269.13
  4947.1  267.77  4961.6  267.72  4982.5  265.48  4990.8  263.92  4997.1  260.46
  5001.2  256.73  5012.9  256.19  5013.4  255.69  5024.1  256.19  5046.8  274.29
  5057.3  276.05  5089.2  280.78  5131.6  281.27  5174.0  286.31  5181.1  285.25
  5202.3  285.26  5230.6  288.93  5260.0  288.65  5273.0  288.62  5287.2  289.70
#Mann=5,-1,0
  4754.3    0.16       0  5012.9    0.07       0  5024.1    0.16       0
  5057.3    0.05       0  5260.0   0.035       0
Bank Sta=5012.9,5024.1
Exp/Cntr=0.3,0.1

Type RM Length L Ch R = 1,7860,434,434,434
BEGIN DESCRIPTION:
Stream0804 17.0
END DESCRIPTION:
XS GIS Cut Line= 3
      2449974.98     13586025.00      2450175.00     13586075.00
      2450525.01     13586275.01
#Sta/Elev= 30
  4794.4  279.03  4885.1  273.04  4907.8  271.71  4918.1  269.11  4936.1  260.80
  4943.4  255.85  4943.9  255.35  4954.2  255.35  4954.7  255.85  4982.5  256.57
  4983.9  257.21  4990.3  260.13  4998.0  261.54  5014.2  262.79  5035.8  262.72
  5093.5  267.53  5104.2  268.62  5110.7  270.15  5175.5  272.11  5212.9  274.22
  5228.8  276.27  5242.4  277.15  5277.7  277.60  5300.0  281.21  5316.5  281.95
  5323.1  281.39  5346.1  281.75  5352.6  282.94  5395.8  286.33  5403.7  285.28
#Mann=7,-1,0
  4794.4    0.16       0  4885.1    0.07       0  4943.4    0.07       0
  4954.7    0.07       0  4983.9    0.12       0  5093.5   0.035       0
  5316.5    0.05       0
Bank Sta=4943.4,4954.7
Exp/Cntr=0.3,0.1

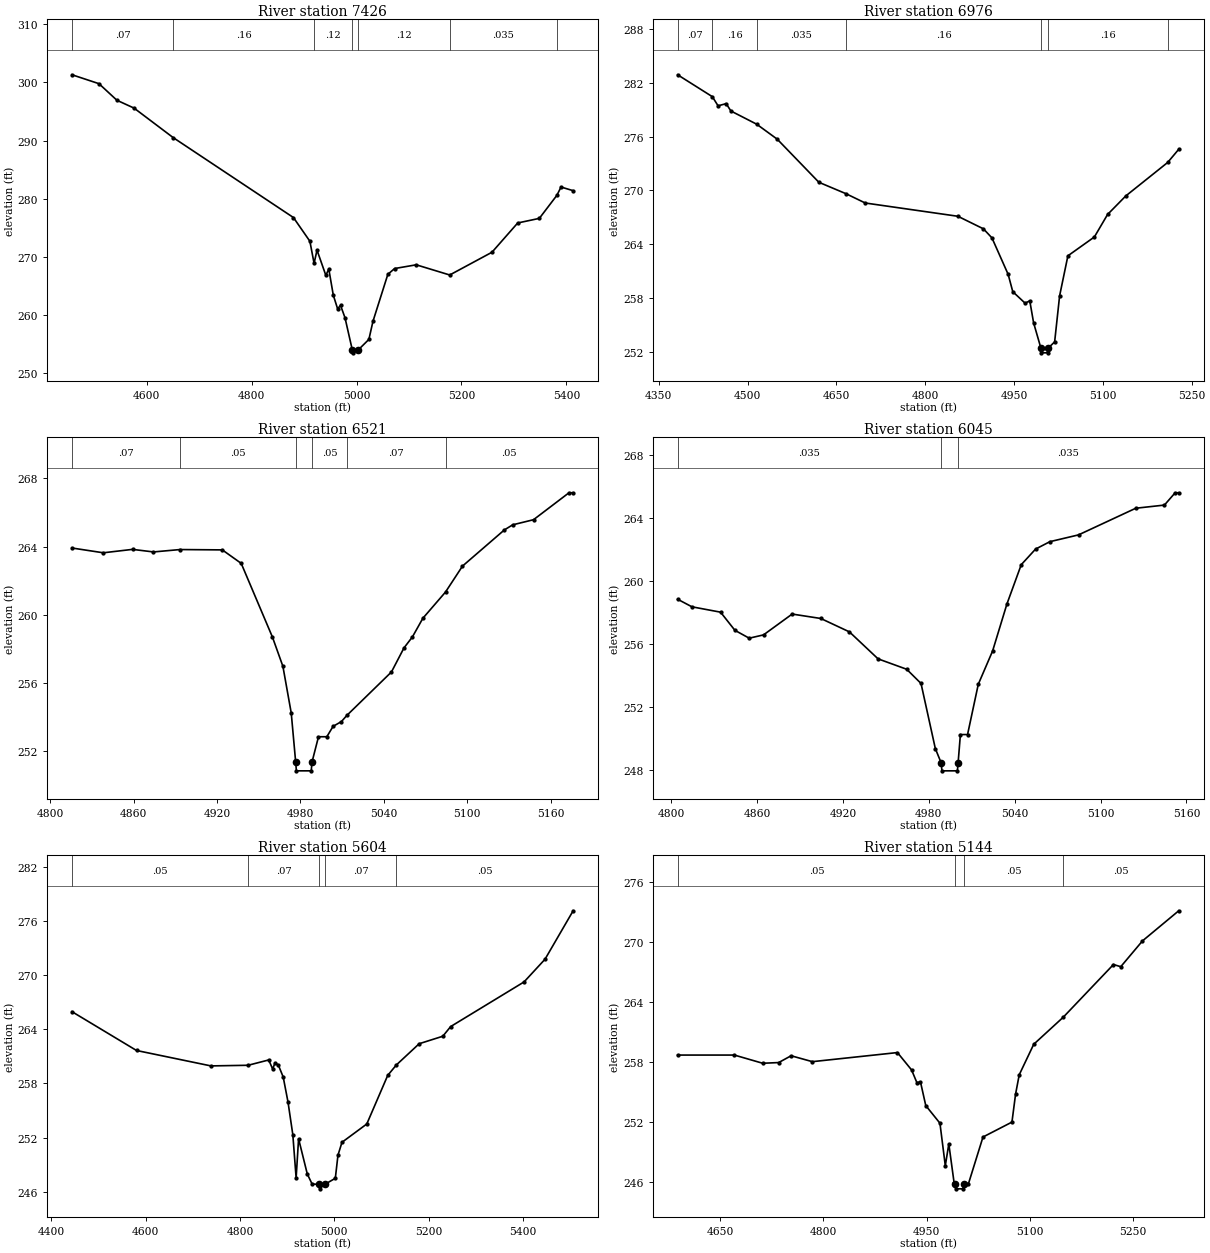
Type RM Length L Ch R = 1,7426,450,450,450
BEGIN DESCRIPTION:
Stream0804 16.0
END DESCRIPTION:
XS GIS Cut Line= 3
      2449589.07     13586234.15      2450075.00     13586475.00
      2450474.95     13586375.01
#Sta/Elev= 30
  4458.1  301.32  4509.4  299.79  4543.6  296.94  4576.3  295.59  4650.5  290.54
  4879.9  276.78  4911.2  272.71  4919.2  268.91  4924.8  271.18  4941.6  266.84
  4947.2  267.94  4955.8  263.44  4964.0  261.10  4969.6  261.69  4978.1  259.56
  4992.0  254.03  4992.5  253.53  5003.3  254.03  5023.6  255.84  5031.4  258.96
  5059.7  267.02  5072.6  268.02  5113.8  268.66  5177.6  266.91  5258.1  270.82
  5307.1  275.85  5348.3  276.64  5381.8  280.61  5389.6  282.03  5412.7  281.40
#Mann=7,-1,0
  4458.1    0.07       0  4650.5    0.16       0  4919.2    0.12       0
  4992.0    0.07       0  5003.3    0.12       0  5177.6   0.035       0
  5381.8    0.05       0
Bank Sta=4992,5003.3
Exp/Cntr=0.3,0.1

Type RM Length L Ch R = 1,6976,455,455,455
BEGIN DESCRIPTION:
Stream0804 15.0
END DESCRIPTION:
XS GIS Cut Line= 3
      2449892.07     13587118.28      2450375.00     13586725.00
      2450474.99     13586525.02
#Sta/Elev= 30
  4381.7  282.89  4440.3  280.45  4450.0  279.43  4463.7  279.67  4471.7  278.85
  4515.2  277.38  4549.9  275.71  4620.3  270.90  4666.0  269.63  4698.6  268.59
  4855.1  267.11  4898.2  265.71  4912.6  264.70  4940.0  260.63  4947.8  258.70
  4968.6  257.42  4976.5  257.68  4983.0  255.22  4995.4  252.38  4995.9  251.88
  5006.6  251.88  5007.1  252.38  5018.5  253.10  5026.9  258.24  5040.9  262.70
  5085.6  264.80  5107.9  267.31  5138.7  269.38  5209.4  273.11  5228.1  274.58
#Mann=7,-1,0
  4381.7    0.07       0  4440.3    0.16       0  4515.2   0.035       0
  4666.0    0.16       0  4995.4    0.07       0  5007.1    0.16       0
  5209.4    0.05       0
Bank Sta=4995.4,5007.1
Exp/Cntr=0.3,0.1

Type RM Length L Ch R = 1,6521,476,476,476
BEGIN DESCRIPTION:
Stream0804 14.0
END DESCRIPTION:
XS GIS Cut Line= 3
      2450375.02     13587224.99      2450525.00     13587125.00
      2450674.97     13587025.02
#Sta/Elev= 30
  4815.7  263.92  4838.2  263.64  4859.2  263.84  4874.3  263.69  4893.4  263.83
  4923.8  263.81  4937.4  263.02  4959.9  258.69  4967.4  256.98  4973.4  254.24
  4976.6  251.35  4977.1  250.85  4987.8  250.85  4988.3  251.35  4993.0  252.85
  4999.0  252.85  5003.5  253.46  5009.5  253.74  5013.4  254.10  5045.5  256.65
  5054.5  258.06  5060.6  258.71  5068.1  259.80  5084.4  261.34  5096.6  262.86
  5126.7  264.98  5132.7  265.28  5147.7  265.58  5173.2  267.16  5176.2  267.16
#Mann=6,-1,0
  4815.7    0.07       0  4893.4    0.05       0  4976.6    0.05       0
  4988.3    0.05       0  5013.4    0.07       0  5084.4    0.05       0
Bank Sta=4976.6,4988.3
Exp/Cntr=0.3,0.1

Type RM Length L Ch R = 1,6045,441,441,441
BEGIN DESCRIPTION:
Stream0804 13.0
END DESCRIPTION:
XS GIS Cut Line= 3
      2450525.04     13587525.00      2450725.00     13587525.00
      2450875.04     13587525.00
#Sta/Elev= 30
  4804.6  258.84  4814.6  258.36  4834.6  258.02  4844.6  256.87  4854.6  256.37
  4864.6  256.58  4884.6  257.90  4904.6  257.62  4924.6  256.77  4944.6  255.06
  4964.6  254.40  4974.6  253.50  4984.6  249.37  4988.7  248.46  4989.2  247.96
  5000.0  247.96  5000.5  248.46  5002.1  250.26  5007.1  250.26  5014.6  253.45
  5024.6  255.56  5034.6  258.54  5044.6  261.03  5054.6  262.02  5064.6  262.49
  5084.6  262.92  5124.6  264.61  5144.6  264.81  5152.1  265.59  5154.6  265.59
#Mann=3,-1,0
  4804.6   0.035       0  4988.7   0.035       0  5000.5   0.035       0
Bank Sta=4988.7,5000.5
Exp/Cntr=0.3,0.1

Type RM Length L Ch R = 1,5604,460,460,460
BEGIN DESCRIPTION:
Stream0804 12.0
END DESCRIPTION:
XS GIS Cut Line= 3
      2450136.95     13587761.69      2450675.00     13587875.00
      2451131.59     13587642.13
#Sta/Elev= 30
  4444.1  265.95  4580.8  261.65  4738.5  259.94  4817.4  260.01  4861.1  260.60
  4869.4  259.60  4874.5  260.27  4881.5  260.03  4891.8  258.71  4902.0  255.93
  4912.2  252.31  4919.2  247.52  4924.4  251.86  4942.9  247.95  4953.1  246.84
  4968.3  246.81  4968.8  246.31  4980.1  246.81  5002.3  247.48  5007.9  250.04
  5016.4  251.47  5069.0  253.50  5113.4  258.89  5131.6  260.04  5180.1  262.40
  5230.2  263.23  5246.8  264.30  5402.4  269.25  5446.9  271.77  5506.5  277.14
#Mann=5,-1,0
  4444.1    0.05       0  4817.4    0.07       0  4968.3    0.07       0
  4980.1    0.07       0  5131.6    0.05       0
Bank Sta=4968.3,4980.1
Exp/Cntr=0.3,0.1

Type RM Length L Ch R = 1,5144,467,467,467
BEGIN DESCRIPTION:
Stream0804 11.0
END DESCRIPTION:
XS GIS Cut Line= 3
      2450374.96     13588074.99      2450775.00     13588175.00
      2451075.02     13588275.01
#Sta/Elev= 30
  4588.1  258.68  4670.6  258.68  4711.8  257.86  4735.0  257.93  4753.1  258.61
  4784.0  258.02  4907.7  258.93  4928.3  257.19  4936.0  255.92  4941.2  256.00
  4948.9  253.63  4969.5  251.87  4977.3  247.62  4982.4  249.80  4990.1  245.91
  4991.9  245.81  4992.4  245.31  5003.4  245.31  5003.9  245.81  5011.0  245.83
  5032.1  250.49  5074.2  251.98  5079.5  254.79  5084.8  256.71  5105.9  259.76
  5148.9  262.47  5221.8  267.73  5232.4  267.51  5264.0  270.09  5316.7  273.10
#Mann=4,-1,0
  4588.1    0.05       0  4991.9    0.07       0  5003.9    0.05       0
  5148.9    0.05       0
Bank Sta=4991.9,5003.9
Exp/Cntr=0.3,0.1

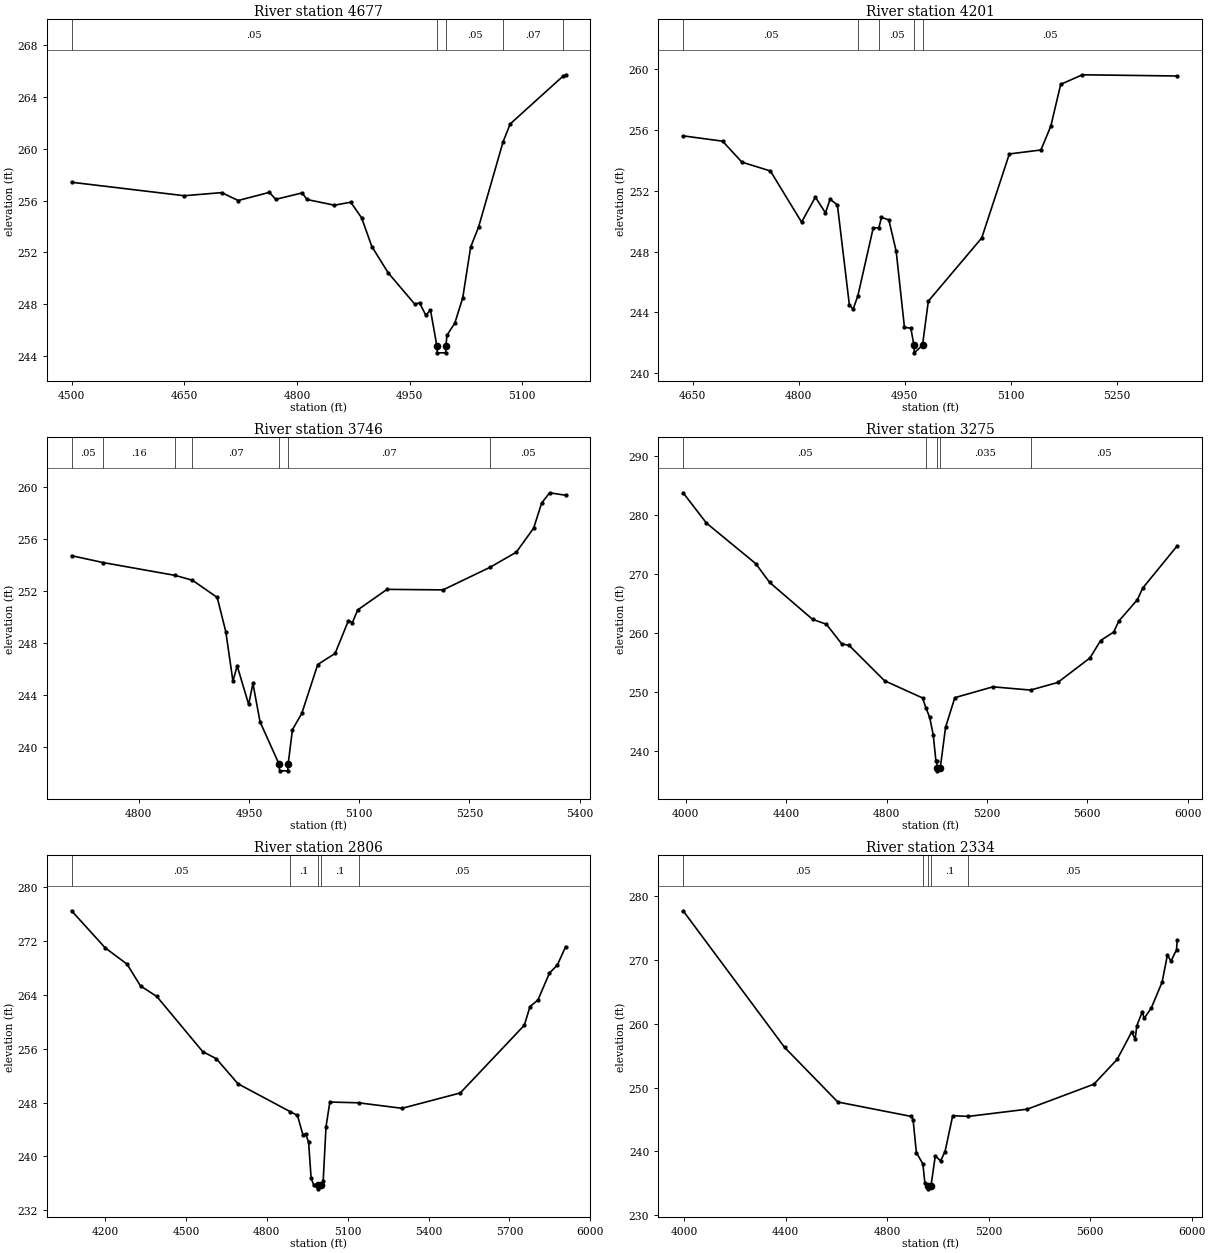
Type RM Length L Ch R = 1,4677,476,476,476
BEGIN DESCRIPTION:
Stream0804 10.0
END DESCRIPTION:
XS GIS Cut Line= 3
      2450325.02     13588325.01      2450725.00     13588625.00
      2450875.01     13588675.00
#Sta/Elev= 30
  4499.6  257.41  4649.6  256.37  4699.6  256.61  4721.5  256.00  4763.1  256.63
  4771.5  256.09  4806.9  256.59  4813.1  256.08  4849.6  255.64  4871.5  255.87
  4886.0  254.66  4899.6  252.45  4921.5  250.41  4956.9  248.00  4963.1  248.11
  4971.5  247.15  4977.7  247.55  4986.3  244.75  4986.8  244.25  4997.8  244.25
  4998.3  244.75  4999.6  245.60  5010.1  246.54  5020.7  248.50  5031.2  252.41
  5041.7  253.94  5074.3  260.51  5083.9  261.91  5153.8  265.57  5157.7  265.70
#Mann=5,-1,0
  4499.6    0.05       0  4986.3    0.05       0  4998.3    0.05       0
  5074.3    0.07       0  5153.8   0.035       0
Bank Sta=4986.3,4998.3
Exp/Cntr=0.3,0.1

Type RM Length L Ch R = 1,4201,455,455,455
BEGIN DESCRIPTION:
Stream0804 9.0
END DESCRIPTION:
XS GIS Cut Line= 3
      2450075.01     13588775.00      2450425.00     13588875.00
      2450724.99     13589025.00
#Sta/Elev= 30
  4636.3  255.62  4692.2  255.27  4719.5  253.89  4759.8  253.31  4804.0  249.94
  4823.5  251.59  4837.8  250.55  4844.3  251.45  4854.7  251.07  4871.6  244.51
  4876.8  244.20  4883.6  245.08  4905.4  249.56  4913.4  249.57  4917.1  250.26
  4927.5  250.09  4937.9  248.03  4949.6  243.02  4958.7  242.96  4963.0  241.84
  4963.5  241.34  4975.2  241.84  4983.4  244.74  5059.0  248.90  5098.1  254.43
  5142.8  254.69  5156.8  256.26  5170.8  259.01  5201.5  259.64  5335.7  259.56
#Mann=5,-1,0
  4636.3    0.05       0  4883.6    0.16       0  4913.4    0.05       0
  4963.0    0.05       0  4975.2    0.05       0
Bank Sta=4963,4975.2
Exp/Cntr=0.3,0.1

Type RM Length L Ch R = 1,3746,471,471,471
BEGIN DESCRIPTION:
Stream0804 8.0
END DESCRIPTION:
XS GIS Cut Line= 3
      2450025.02     13589125.01      2450275.00     13589275.00
      2450624.99     13589125.01
#Sta/Elev= 30
  4708.5  254.69  4751.6  254.16  4849.9  253.17  4873.0  252.80  4906.7  251.48
  4918.4  248.84  4928.1  245.04  4933.9  246.21  4949.5  243.25  4955.3  244.86
  4965.0  241.91  4991.0  238.64  4991.5  238.14  5002.7  238.14  5003.2  238.64
  5009.1  241.31  5021.8  242.56  5043.5  246.32  5067.1  247.17  5085.3  249.70
  5090.7  249.55  5097.9  250.52  5137.8  252.10  5214.0  252.06  5278.4  253.81
  5313.7  254.96  5337.3  256.81  5348.2  258.74  5359.1  259.53  5380.8  259.34
#Mann=7,-1,0
  4708.5    0.05       0  4751.6    0.16       0  4849.9    0.05       0
  4873.0    0.07       0  4991.0    0.07       0  5003.2    0.07       0
  5278.4    0.05       0
Bank Sta=4991,5003.2
Exp/Cntr=0.3,0.1

Type RM Length L Ch R = 1,3275,469,469,469
BEGIN DESCRIPTION:
Stream0804 7.0
END DESCRIPTION:
XS GIS Cut Line= 5
      2449518.24     13590090.81      2450301.39     13589798.61
      2450425.00     13589675.00      2450616.92     13589559.85
      2451315.94     13589335.33
#Sta/Elev= 30
  3989.3  283.77  4082.3  278.62  4278.5  271.75  4333.8  268.56  4505.0  262.29
  4560.3  261.45  4620.9  258.14  4651.2  257.85  4792.1  251.86  4943.4  248.94
  4956.2  247.32  4971.7  245.65  4985.8  242.71  4996.5  238.30  5000.0  238.30
  5001.6  237.07  5002.1  236.57  5014.0  237.07  5035.0  243.96  5071.9  248.99
  5223.7  250.83  5373.7  250.28  5482.0  251.57  5610.4  255.73  5653.0  258.69
  5704.9  260.13  5725.9  262.02  5799.5  265.62  5820.5  267.58  5958.0  274.76
#Mann=5,-1,0
  3989.3    0.05       0  4956.2   0.035       0  5001.6   0.035       0
  5014.0   0.035       0  5373.7    0.05       0
Bank Sta=5001.6,5014
Exp/Cntr=0.3,0.1

Type RM Length L Ch R = 1,2806,472,472,472
BEGIN DESCRIPTION:
Stream0804 6.0
END DESCRIPTION:
XS GIS Cut Line= 5
      2449700.19     13590140.44      2450571.91     13590061.73
      2450625.00     13590075.00      2450662.05     13590037.95
      2451370.58     13589567.29
#Sta/Elev= 30
  4075.4  276.51  4200.7  270.98  4281.0  268.59  4331.2  265.34  4391.5  263.78
  4562.2  255.57  4612.4  254.53  4692.7  250.80  4886.6  246.65  4913.6  246.09
  4933.7  243.22  4943.7  243.36  4954.8  242.15  4964.2  236.77  4974.5  235.69
  4988.9  235.68  4989.4  235.18  5001.3  235.68  5008.9  236.31  5019.5  244.43
  5033.7  248.08  5140.0  247.97  5301.3  247.15  5517.5  249.43  5755.3  259.50
  5776.3  262.28  5805.7  263.24  5848.5  267.26  5877.7  268.44  5908.4  271.17
#Mann=5,-1,0
  4075.4    0.05       0  4886.6     0.1       0  4988.9    0.05       0
  5001.3     0.1       0  5140.0    0.05       0
Bank Sta=4988.9,5001.3
Exp/Cntr=0.3,0.1

Type RM Length L Ch R = 1,2334,465,465,465
BEGIN DESCRIPTION:
Stream0804 5.0
END DESCRIPTION:
XS GIS Cut Line= 5
      2449904.26     13590658.80      2450499.25     13590468.94
      2450875.00     13590375.00      2450883.46     13590315.77
      2451470.22     13589666.38
#Sta/Elev= 30
  3996.1  277.71  4395.8  256.32  4605.7  247.75  4894.6  245.50  4902.3  244.97
  4915.2  239.84  4941.0  238.04  4948.7  235.08  4960.5  234.65  4961.0  234.15
  4973.0  234.65  4989.9  239.34  5010.5  238.52  5028.2  239.99  5058.5  245.61
  5120.4  245.50  5352.3  246.63  5614.6  250.54  5706.5  254.43  5763.3  258.70
  5777.5  257.63  5784.2  259.73  5805.9  261.93  5812.6  260.84  5841.0  262.48
  5883.6  266.54  5904.5  270.77  5918.7  269.82  5940.4  271.61  5943.0  273.09
#Mann=5,-1,0
  3996.1    0.05       0  4941.0     0.1       0  4960.5    0.05       0
  4973.0     0.1       0  5120.4    0.05       0
Bank Sta=4960.5,4973
Exp/Cntr=0.3,0.1

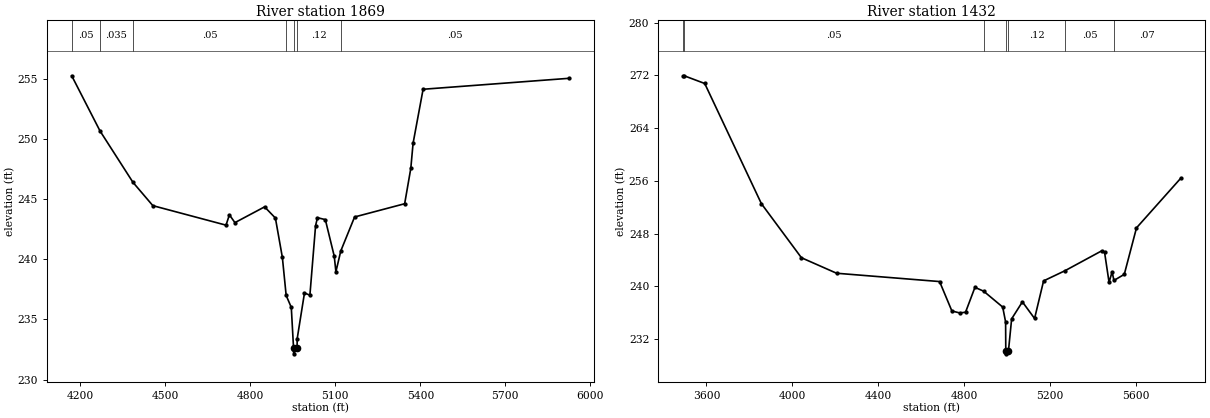
Type RM Length L Ch R = 1,1869,437,437,437
BEGIN DESCRIPTION:
Stream0804 4.0
END DESCRIPTION:
XS GIS Cut Line= 3
      2450425.03     13590874.99      2451225.00     13590625.00
      2451675.00     13589825.00
#Sta/Elev= 30
  4169.1  255.24  4268.9  250.66  4385.3  246.39  4455.6  244.45  4713.9  242.83
  4725.9  243.69  4745.3  243.04  4850.1  244.35  4888.3  243.42  4912.9  240.15
  4926.3  236.99  4944.4  236.00  4952.3  232.64  4952.8  232.14  4964.8  232.64
  4965.3  233.41  4991.0  237.20  5010.1  237.01  5030.2  242.80  5036.9  243.45
  5064.6  243.29  5096.1  240.25  5101.9  238.96  5119.2  240.69  5167.9  243.51
  5344.7  244.61  5366.4  247.55  5374.4  249.63  5409.8  254.12  5925.1  255.03
#Mann=7,-1,0
  4169.1    0.05       0  4268.9   0.035       0  4385.3    0.05       0
  4926.3    0.12       0  4952.3    0.07       0  4964.8    0.12       0
  5119.2    0.05       0
Bank Sta=4952.3,4964.8
Exp/Cntr=0.3,0.1

Type RM Length L Ch R = 1,1432,425,425,425
BEGIN DESCRIPTION:
Stream0804 3.0
END DESCRIPTION:
XS GIS Cut Line= 3
      2450374.96     13591625.03      2451575.00     13590725.00
      2452125.01     13590124.99
#Sta/Elev= 30
  3492.0  271.88  3496.5  271.93  3592.0  270.76  3855.6  252.54  4042.0  244.34
  4205.6  241.99  4684.8  240.73  4742.0  236.27  4778.5  235.97  4805.6  236.08
  4849.3  239.85  4889.8  239.27  4978.5  236.86  4992.0  234.60  4992.8  230.27
  4993.3  229.77  5005.4  230.27  5020.1  235.08  5070.1  237.65  5126.8  235.13
  5168.7  240.83  5268.7  242.38  5438.2  245.37  5452.4  245.18  5473.3  240.62
  5487.5  242.19  5496.1  240.90  5544.2  241.82  5601.0  248.87  5806.0  256.36
#Mann=7,-1,0
  3492.0    0.07       0  3496.5    0.05       0  4889.8    0.12       0
  4992.8    0.07       0  5005.4    0.12       0  5268.7    0.05       0
  5496.1    0.07       0
Bank Sta=4992.8,5005.4
Exp/Cntr=0.3,0.1