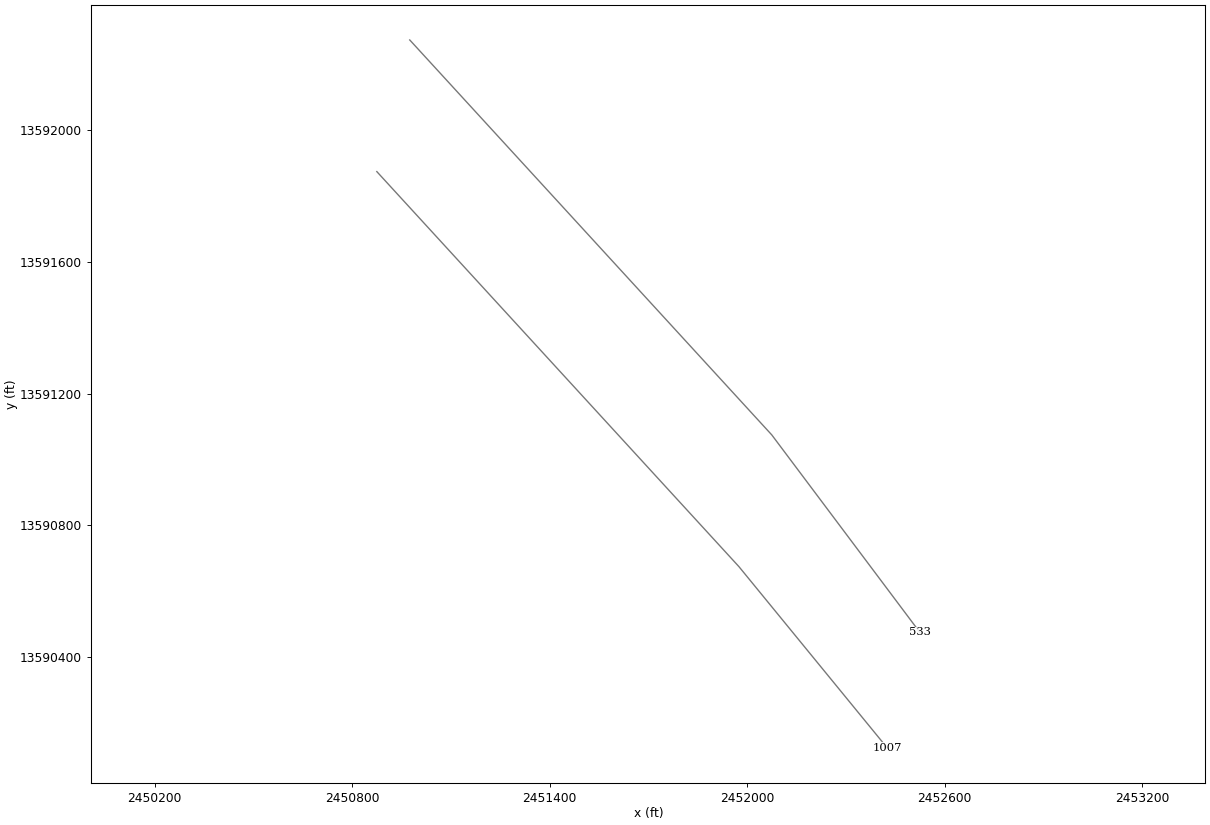
HEC-RAS study Stream0804.prj: Stream0804 Base Level Engineering

--- Stream0804.g01 (geometry) --- (continued)

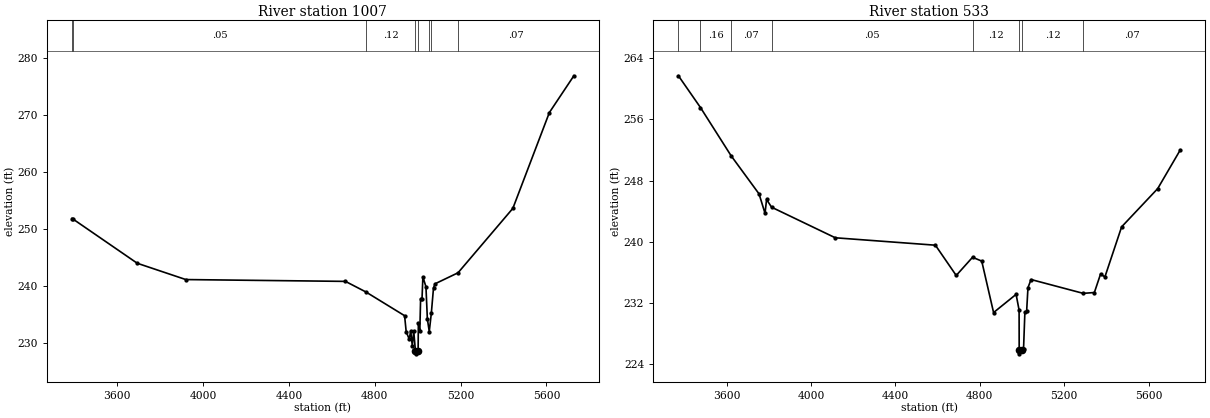
Type RM Length L Ch R = 1,1007,474,474,474
BEGIN DESCRIPTION:
Stream0804 2.0
END DESCRIPTION:
XS GIS Cut Line= 3
      2450874.98     13591875.02      2451975.00     13590675.00
      2452424.97     13590125.03
#Sta/Elev= 30
  3389.4  251.79  3394.8  251.68  3693.7  243.94  3920.0  241.08  4663.7  240.76
  4758.8  238.91  4939.3  234.74  4946.7  231.93  4960.9  230.63  4967.7  232.08
  4975.1  229.49  4981.9  232.04  4989.7  228.55  4990.2  228.05  5002.3  228.55
  5003.4  233.45  5010.2  231.99  5013.9  237.74  5020.5  237.74  5024.5  241.56
  5038.8  239.81  5045.3  234.21  5054.2  231.95  5063.9  235.20  5074.0  239.63
  5081.9  240.35  5188.3  242.27  5443.7  253.57  5613.8  270.38  5727.9  276.83
#Mann=8,-1,0
  3389.4    0.07       0  3394.8    0.05       0  4758.8    0.12       0
  4989.7    0.07       0  5002.3    0.12       0  5054.2    0.07       0
  5063.9    0.12       0  5188.3    0.07       0
Bank Sta=4989.7,5002.3
Exp/Cntr=0.3,0.1

Type RM Length L Ch R = 1,533,0,0,0
BEGIN DESCRIPTION:
Stream0804 1.0
END DESCRIPTION:
XS GIS Cut Line= 3
      2450975.02     13592274.98      2452075.00     13591075.00
      2452524.97     13590475.04
#Sta/Elev= 30
  3372.1  261.70  3476.5  257.55  3621.7  251.24  3754.1  246.25  3782.4  243.71
  3789.8  245.52  3813.4  244.51  4115.4  240.51  4589.6  239.54  4688.2  235.58
  4765.6  237.96  4809.1  237.46  4865.2  230.73  4971.9  233.11  4986.1  231.05
  4986.5  225.83  4987.0  225.33  4999.3  225.83  5007.2  225.98  5013.5  230.76
  5021.8  230.89  5028.1  233.98  5042.7  235.05  5289.9  233.24  5342.7  233.35
  5371.8  235.75  5392.7  235.40  5471.8  241.94  5642.7  246.94  5749.9  252.01
#Mann=8,-1,0
  3372.1    0.07       0  3476.5    0.16       0  3621.7    0.07       0
  3813.4    0.05       0  4765.6    0.12       0  4986.5    0.07       0
  4999.3    0.12       0  5289.9    0.07       0
Bank Sta=4986.5,4999.3
Exp/Cntr=0.3,0.1

Chan Stop Cuts=-1