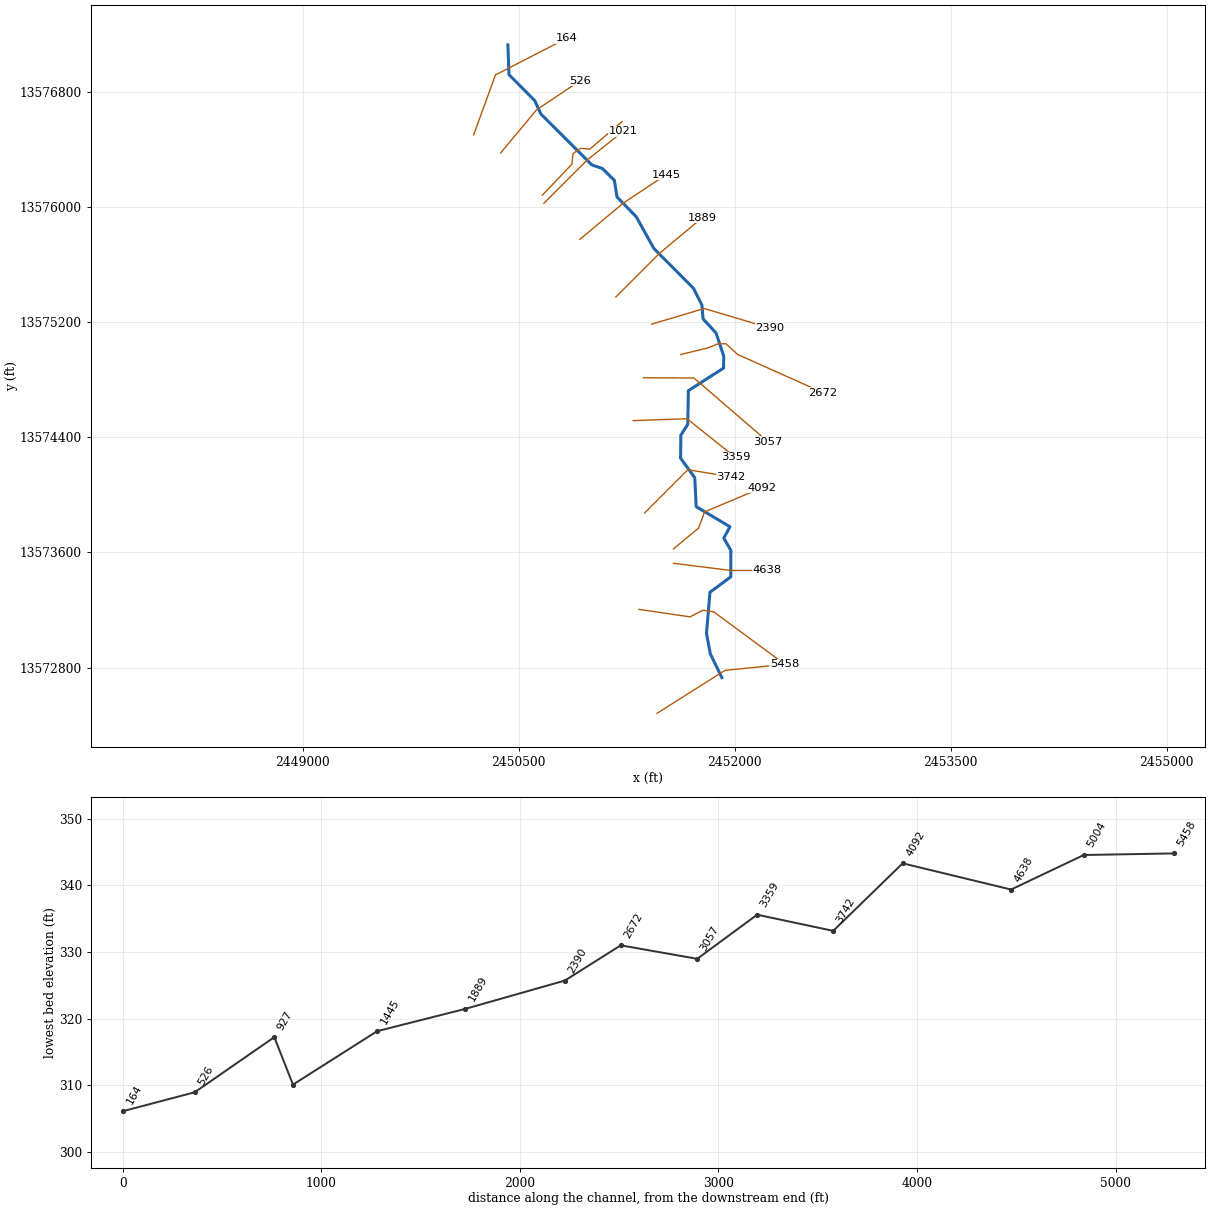
--- Stream0805.prj (project) ---

Proj Title=Stream0805 Base Level Engineering
Current Plan=p01
Default Exp/Contr=0.3,0.1
English Units
Geom File=g01
Flow File=f01
Plan File=p01
BEGIN DESCRIPTION:
Stream0805
END DESCRIPTION:

--- Stream0805.p01 (plan) ---

Plan Title=Multiple Run
Short Identifier=Multiple
Geom File=g01
Flow File=f01
Subcritical Flow
K Sum by GR= 0
Std Step Tol= 0.01
Critical Tol= 0.01
Num of Std Step Trials= 20
Max Error Tol= 0.3
Flow Tol Ratio= 0.001
Split Flow NTrial= 30
Split Flow Tol= 0.02
Split Flow Ratio= 0.02
Log Output Level= 0
Friction Slope Method= 1
Unsteady Friction Slope Method= 2
Unsteady Bridges Friction Slope Method= 1
Parabolic Critical Depth
Global Vel Dist=  1 , 1 , 1
Global Log Level= 0
CheckData=True
Encroach Param= -1, 0, 0, 0
BEGIN DESCRIPTION:
Multiple Run
END DESCRIPTION:

--- Stream0805.f01 (steady flow) ---

Flow Title=Multiple
Number of Profiles=7
Profile Names=10-year,25-year,50-year,1pct_min,100-year,1pct_plu,500-year
River Rch & RM= Stream0805,Reach-1,5458
     475     755    1004     647    1292    2577    2116
Boundary for River Rch & Prof#=Stream0805,Reach-1,1
Up Type=0
Dn Type=3
Dn Slope=0.005
Boundary for River Rch & Prof#=Stream0805,Reach-1,2
Up Type=0
Dn Type=3
Dn Slope=0.005
Boundary for River Rch & Prof#=Stream0805,Reach-1,3
Up Type=0
Dn Type=3
Dn Slope=0.005
Boundary for River Rch & Prof#=Stream0805,Reach-1,4
Up Type=0
Dn Type=3
Dn Slope=0.005
Boundary for River Rch & Prof#=Stream0805,Reach-1,5
Up Type=0
Dn Type=3
Dn Slope=0.005
Boundary for River Rch & Prof#=Stream0805,Reach-1,6
Up Type=0
Dn Type=3
Dn Slope=0.005
Boundary for River Rch & Prof#=Stream0805,Reach-1,7
Up Type=0
Dn Type=3
Dn Slope=0.005

--- Stream0805.g01 (geometry) ---

Geom Title=Existing Conditions

River Reach=Stream0805,Reach-1
Reach XY= 30
      2451911.19     13572730.80      2451830.46     13572897.47
      2451804.42     13573038.09      2451828.44     13573323.75
      2451973.02     13573430.67      2451973.76     13573614.50
      2451924.69     13573700.04      2451967.28     13573778.66
      2451732.69     13573918.52      2451722.93     13574119.14
      2451624.57     13574254.82      2451626.22     13574414.49
      2451674.48     13574490.22      2451678.45     13574723.75
      2451923.11     13574880.71      2451923.90     13574964.44
      2451871.38     13575123.50      2451780.54     13575222.58
      2451772.67     13575319.03      2451714.24     13575434.68
      2451438.63     13575711.79      2451316.84     13575931.05
      2451182.86     13576068.83      2451164.49     13576184.81
      2451081.07     13576266.85      2451008.33     13576291.65
      2450654.62     13576644.84      2450611.37     13576738.21
      2450432.81     13576918.81      2450425.00     13577125.00

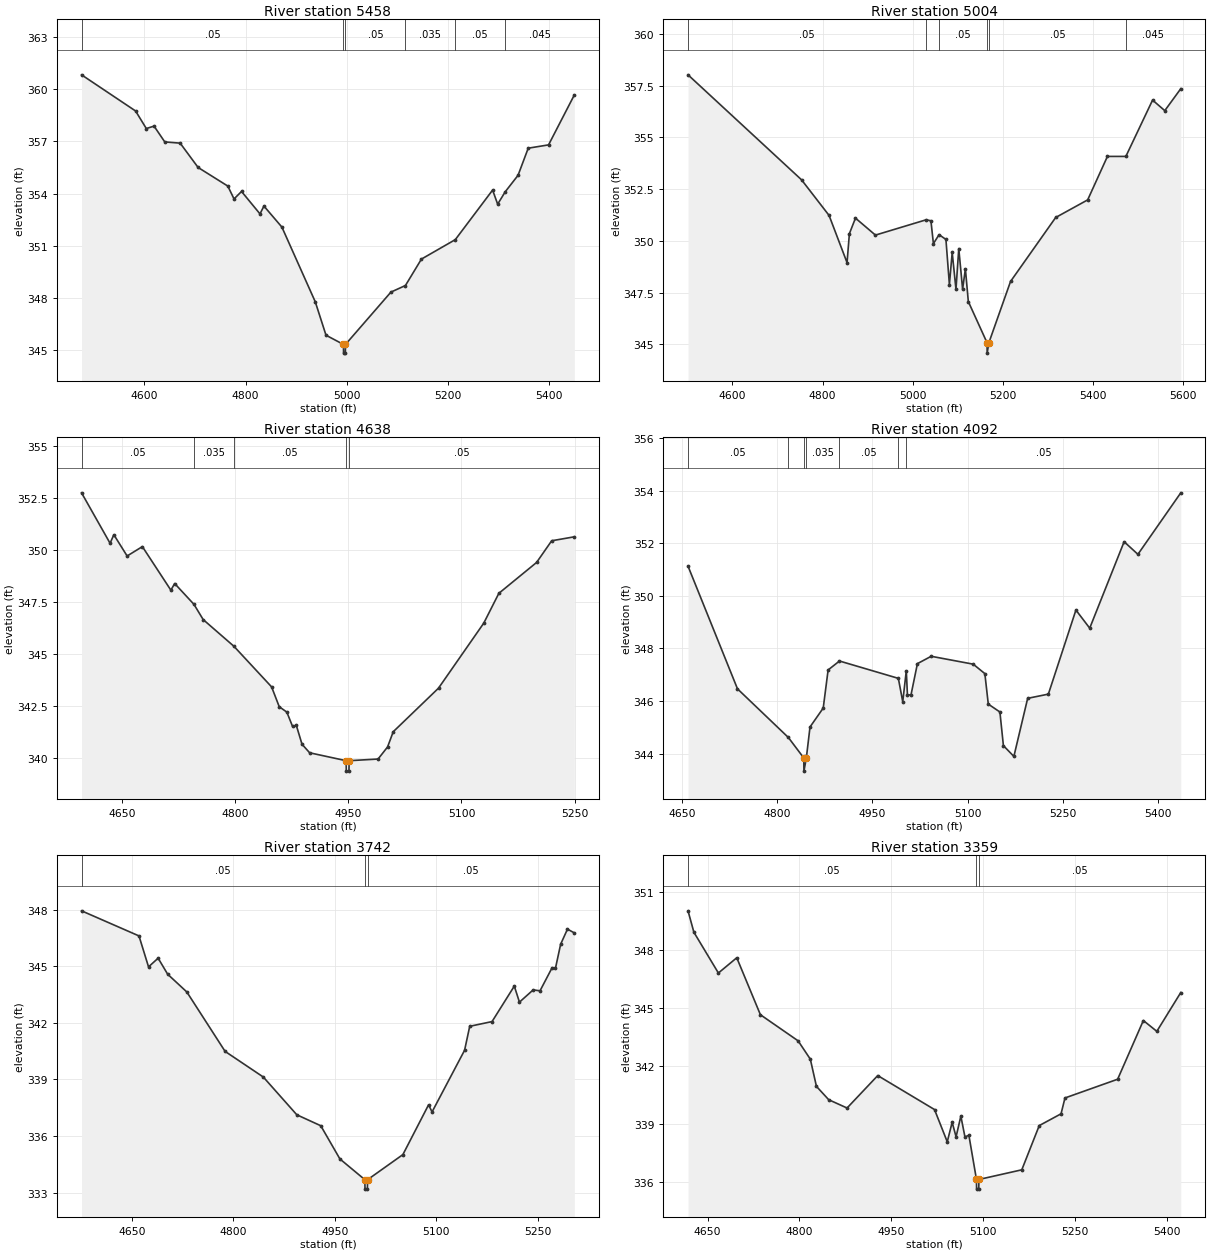
Type RM Length L Ch R = 1,5458,454,454,454
BEGIN DESCRIPTION:
XS7752a
END DESCRIPTION:
XS GIS Cut Line= 3
      2451460.27     13572482.56      2451932.46     13572781.15
      2452345.69     13572822.82
#Sta/Elev= 30
  4475.6  360.83  4582.4  358.75  4603.6  357.74  4618.9  357.88  4640.1  356.97
  4670.5  356.90  4706.0  355.50  4764.7  354.43  4777.0  353.69  4791.8  354.12
  4828.3  352.83  4836.1  353.28  4871.6  352.07  4937.6  347.77  4958.8  345.85
  4993.3  345.32  4993.5  344.82  4997.0  344.82  4997.3  345.32  5087.1  348.33
  5115.8  348.71  5147.4  350.23  5214.4  351.35  5288.1  354.20  5298.1  353.39
  5313.0  354.10  5338.4  355.05  5358.5  356.61  5398.7  356.80  5449.6  359.67
#Mann=6,-1,0
  4475.6    0.05       0  4993.3    0.05       0  4997.3    0.05       0
  5115.8   0.035       0  5214.4    0.05       0  5313.0   0.045       0
Bank Sta=4993.3,4997.3
Exp/Cntr=0.3,0.1

Type RM Length L Ch R = 1,5004,366,366,366
BEGIN DESCRIPTION:
XS7752
END DESCRIPTION:
XS GIS Cut Line= 5
      2451335.70     13573204.76      2451690.24     13573152.79
      2451780.98     13573199.55      2451856.50     13573186.53
      2452304.39     13572855.82
#Sta/Elev= 30
  4501.4  358.02  4753.4  352.95  4814.5  351.23  4854.4  348.95  4859.6  350.35
  4873.1  351.10  4917.4  350.28  5030.1  351.02  5040.6  350.97  5046.1  349.87
  5058.7  350.30  5073.9  350.07  5081.6  347.89  5087.8  349.44  5096.2  347.66
  5102.4  349.63  5110.9  347.67  5117.1  348.65  5123.6  347.07  5165.2  345.08
  5165.4  344.58  5169.2  345.08  5217.3  348.04  5317.5  351.13  5388.5  351.98
  5432.4  354.08  5473.3  354.08  5532.6  356.80  5559.7  356.29  5595.2  357.35
#Mann=6,-1,0
  4501.4    0.05       0  5030.1   0.035       0  5058.7    0.05       0
  5165.2    0.05       0  5169.2    0.05       0  5473.3   0.045       0
Bank Sta=5165.2,5169.2
Exp/Cntr=0.3,0.1

Type RM Length L Ch R = 1,4638,546,546,546
BEGIN DESCRIPTION:
Stream0805 10.0
END DESCRIPTION:
XS GIS Cut Line= 3
      2451575.03     13573525.00      2451975.00     13573475.00
      2452225.01     13573475.00
#Sta/Elev= 30
  4596.5  352.74  4634.3  350.32  4639.3  350.73  4656.9  349.71  4677.1  350.16
  4714.9  348.07  4719.9  348.39  4745.5  347.39  4757.7  346.66  4798.4  345.38
  4848.4  343.43  4858.5  342.48  4868.6  342.22  4876.1  341.54  4881.2  341.58
  4888.7  340.68  4898.8  340.27  4947.2  339.89  4947.4  339.39  4950.9  339.39
  4951.2  339.89  4989.5  339.97  5002.1  340.55  5009.6  341.28  5069.6  343.37
  5129.6  346.49  5149.6  347.92  5199.6  349.40  5219.6  350.44  5249.6  350.63
#Mann=5,-1,0
  4596.5    0.05       0  4745.5   0.035       0  4798.4    0.05       0
  4947.2    0.05       0  4951.2    0.05       0
Bank Sta=4947.2,4951.2
Exp/Cntr=0.3,0.1

Type RM Length L Ch R = 1,4092,350,350,350
BEGIN DESCRIPTION:
Stream0805 9.0
END DESCRIPTION:
XS GIS Cut Line= 4
      2451575.01     13573625.01      2451749.73     13573769.87
      2451791.40     13573881.84      2452187.20     13574048.50
#Sta/Elev= 30
  4659.9  351.13  4737.8  346.46  4817.9  344.61  4842.2  343.83  4842.4  343.33
  4846.2  343.83  4852.0  345.01  4872.8  345.73  4880.5  347.18  4898.4  347.52
  4991.1  346.86  4998.0  345.97  5003.6  347.15  5005.4  346.23  5011.0  346.23
  5021.1  347.42  5042.8  347.70  5109.0  347.40  5127.3  347.04  5132.7  345.88
  5151.0  345.58  5156.5  344.30  5173.0  343.89  5194.7  346.10  5227.3  346.26
  5270.7  349.46  5292.4  348.77  5346.6  352.06  5368.3  351.58  5435.8  353.92
#Mann=7,-1,0
  4659.9    0.05       0  4817.9   0.035       0  4842.2    0.05       0
  4846.2   0.035       0  4898.4    0.05       0  4991.1    0.12       0
  5003.6    0.05       0
Bank Sta=4842.2,4846.2
Exp/Cntr=0.3,0.1

Type RM Length L Ch R = 1,3742,383,383,383
BEGIN DESCRIPTION:
Stream0805 8.0
END DESCRIPTION:
XS GIS Cut Line= 3
      2451374.98     13573874.98      2451675.00     13574175.00
      2451974.97     13574125.00
#Sta/Elev= 30
  4575.7  347.93  4660.6  346.60  4674.7  344.96  4688.9  345.42  4703.0  344.57
  4731.3  343.63  4787.9  340.48  4844.4  339.12  4893.9  337.12  4929.3  336.54
  4957.6  334.78  4994.5  333.68  4994.7  333.18  4998.2  333.18  4998.5  333.68
  5050.7  335.01  5088.7  337.65  5093.8  337.27  5141.9  340.54  5149.5  341.81
  5182.5  342.06  5215.4  343.94  5223.0  343.09  5243.3  343.74  5253.4  343.69
  5271.2  344.91  5276.2  344.88  5283.9  346.16  5294.0  346.96  5304.1  346.76
#Mann=3,-1,0
  4575.7    0.05       0  4994.5    0.05       0  4998.5    0.05       0
Bank Sta=4994.5,4998.5
Exp/Cntr=0.3,0.1

Type RM Length L Ch R = 1,3359,302,302,302
BEGIN DESCRIPTION:
Stream0805 7.0
END DESCRIPTION:
XS GIS Cut Line= 3
      2451295.45     13574515.59      2451668.90     13574529.13
      2452005.57     13574260.19
#Sta/Elev= 30
  4618.0  350.02  4627.6  348.91  4667.6  346.80  4697.6  347.59  4736.2  344.64
  4797.7  343.29  4817.7  342.34  4827.7  340.93  4847.7  340.24  4877.7  339.81
  4927.8  341.49  5020.5  339.73  5041.3  338.06  5049.3  339.07  5055.7  338.32
  5063.5  339.39  5070.2  338.31  5076.6  338.40  5089.0  336.11  5089.2  335.61
  5092.7  335.61  5093.0  336.11  5163.0  336.61  5191.5  338.90  5227.1  339.51
  5233.5  340.33  5319.5  341.30  5361.5  344.34  5383.5  343.78  5422.6  345.79
#Mann=3,-1,0
  4618.0    0.05       0  5089.0    0.05       0  5093.0    0.05       0
Bank Sta=5089,5093
Exp/Cntr=0.3,0.1

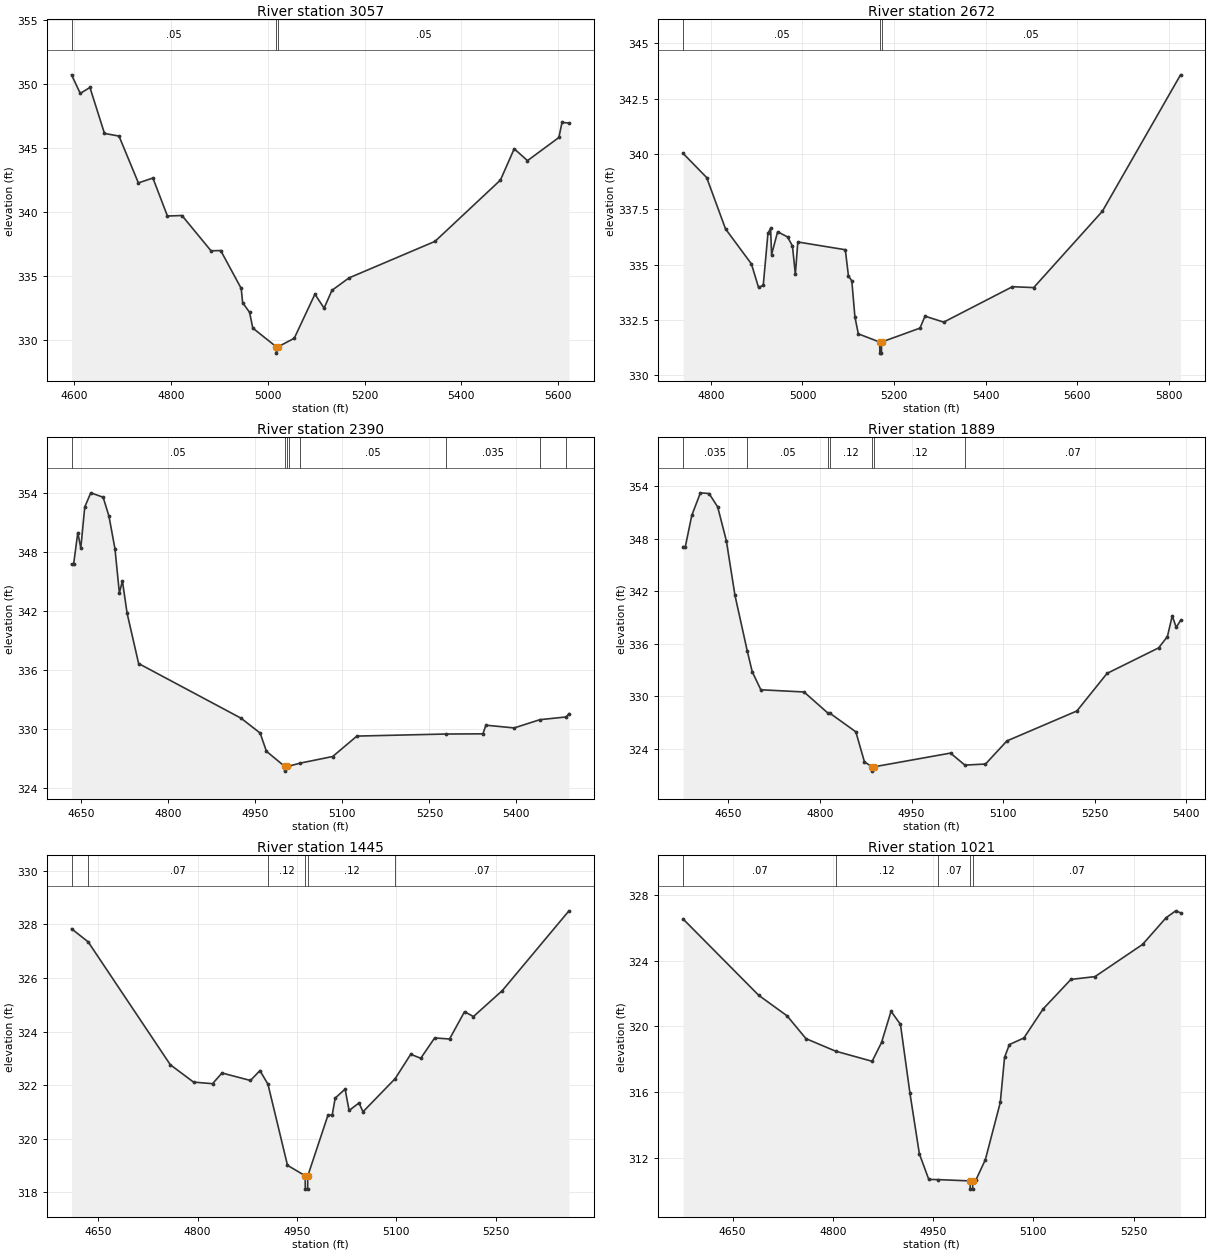
Type RM Length L Ch R = 1,3057,385,385,385
BEGIN DESCRIPTION:
Stream0805 7.0a
END DESCRIPTION:
XS GIS Cut Line= 3
      2451367.01     13574813.59      2451717.28     13574811.65
      2452230.14     13574370.13
#Sta/Elev= 30
  4595.0  350.74  4613.0  349.29  4633.0  349.75  4663.0  346.16  4693.0  345.95
  4733.0  342.29  4763.0  342.67  4793.0  339.70  4823.0  339.74  4883.0  336.98
  4903.0  337.00  4945.3  334.04  4948.3  332.92  4962.6  332.17  4969.2  330.94
  5017.6  329.48  5017.9  328.98  5021.6  329.48  5054.8  330.14  5097.5  333.59
  5116.4  332.50  5132.7  333.89  5167.8  334.86  5345.5  337.72  5480.5  342.51
  5509.0  344.96  5536.4  344.03  5601.2  345.84  5607.7  347.02  5622.0  346.97
#Mann=3,-1,0
  4595.0    0.05       0  5017.6    0.05       0  5021.6    0.05       0
Bank Sta=5017.6,5021.6
Exp/Cntr=0.3,0.1

Type RM Length L Ch R = 1,2672,282,282,282
BEGIN DESCRIPTION:
Stream0805 6.0
END DESCRIPTION:
XS GIS Cut Line= 6
      2451625.00     13574975.00      2451814.03     13575020.64
      2451885.63     13575049.66      2451939.81     13575049.66
      2452019.15     13574976.13      2452614.09     13574709.57
#Sta/Elev= 30
  4739.5  340.03  4790.9  338.94  4832.1  336.62  4888.6  335.04  4904.1  333.98
  4914.4  334.07  4924.7  336.42  4930.5  336.65  4932.6  335.46  4945.8  336.49
  4967.4  336.26  4978.2  335.85  4984.5  334.57  4989.9  336.03  5093.6  335.68
  5100.4  334.50  5107.8  334.27  5114.6  332.64  5122.0  331.88  5168.7  331.51
  5169.0  331.01  5172.5  331.01  5172.7  331.51  5256.6  332.14  5267.6  332.68
  5308.4  332.41  5458.5  334.01  5504.9  333.97  5654.9  337.42  5825.5  343.58
#Mann=3,-1,0
  4739.5    0.05       0  5168.7    0.05       0  5172.7    0.05       0
Bank Sta=5168.7,5172.7
Exp/Cntr=0.3,0.1

Type RM Length L Ch R = 1,2390,501,501,501
BEGIN DESCRIPTION:
Stream0805 5.0
END DESCRIPTION:
XS GIS Cut Line= 3
      2451423.16     13575185.90      2451788.87     13575294.25
      2452245.58     13575158.79
#Sta/Elev= 30
  4632.9  346.79  4636.5  346.79  4643.7  350.01  4648.9  348.43  4655.7  352.62
  4666.1  354.06  4687.4  353.61  4697.4  351.69  4707.8  348.36  4715.4  343.85
  4720.6  345.10  4728.7  341.80  4748.6  336.67  4925.3  331.10  4958.1  329.59
  4969.0  327.73  5000.2  326.21  5000.5  325.71  5004.2  326.21  5007.6  326.22
  5027.7  326.53  5083.3  327.20  5125.0  329.28  5278.9  329.49  5342.3  329.51
  5347.5  330.39  5396.2  330.11  5440.5  330.95  5485.9  331.23  5490.7  331.56
#Mann=8,-1,0
  4632.9    0.05       0  5000.2    0.05       0  5004.2    0.05       0
  5007.6   0.035       0  5027.7    0.05       0  5278.9   0.035       0
  5440.5    0.05       0  5485.9   0.035       0
Bank Sta=5000.2,5004.2
Exp/Cntr=0.3,0.1

Type RM Length L Ch R = 1,1889,444,444,444
BEGIN DESCRIPTION:
Stream0805 4.0
END DESCRIPTION:
XS GIS Cut Line= 3
      2451174.96     13575374.96      2451475.00     13575675.00
      2451774.98     13575924.98
#Sta/Elev= 30
  4575.9  347.09  4579.5  347.09  4590.1  350.67  4604.2  353.24  4618.4  353.16
  4632.5  351.63  4646.7  347.77  4660.8  341.54  4680.9  335.20  4689.1  332.81
  4703.2  330.75  4773.9  330.50  4813.2  328.08  4816.0  328.09  4858.8  325.95
  4872.9  322.52  4885.1  321.96  4885.3  321.46  4889.1  321.96  5013.9  323.52
  5037.4  322.15  5071.2  322.27  5106.3  324.91  5220.9  328.33  5270.3  332.62
  5354.9  335.54  5369.2  336.83  5377.1  339.19  5383.6  337.88  5390.7  338.67
#Mann=7,-1,0
  4575.9   0.035       0  4680.9    0.05       0  4813.2   0.035       0
  4816.0    0.12       0  4885.1    0.05       0  4889.1    0.12       0
  5037.4    0.07       0
Bank Sta=4885.1,4889.1
Exp/Cntr=0.3,0.1

Type RM Length L Ch R = 1,1445,424,424,424
BEGIN DESCRIPTION:
Stream0805 3.0
END DESCRIPTION:
XS GIS Cut Line= 3
      2450924.96     13575774.97      2451225.00     13576025.00
      2451524.99     13576224.99
#Sta/Elev= 30
  4609.7  327.84  4634.8  327.35  4758.8  322.76  4793.9  322.11  4822.6  322.05
  4836.9  322.45  4879.9  322.17  4894.2  322.54  4906.3  322.03  4935.8  319.00
  4962.5  318.61  4962.7  318.11  4966.2  318.11  4966.5  318.61  4997.0  320.88
  5003.3  320.88  5007.8  321.51  5022.8  321.85  5028.8  321.05  5043.8  321.33
  5049.8  321.00  5098.4  322.24  5121.9  323.15  5137.0  323.00  5158.0  323.76
  5180.5  323.72  5203.1  324.74  5216.6  324.56  5260.2  325.53  5360.8  328.51
#Mann=6,-1,0
  4609.7   0.035       0  4634.8    0.07       0  4906.3    0.12       0
  4962.5    0.05       0  4966.5    0.12       0  5098.4    0.07       0
Bank Sta=4962.5,4966.5
Exp/Cntr=0.3,0.1

Type RM Length L Ch R = 1,1021,94,94,94
BEGIN DESCRIPTION:
Stream0805 2.0
END DESCRIPTION:
XS GIS Cut Line= 3
      2450674.96     13576024.96      2450975.00     13576325.00
      2451225.02     13576525.02
#Sta/Elev= 30
  4575.9  326.54  4689.1  321.89  4731.5  320.64  4759.8  319.25  4804.0  318.49
  4858.8  317.87  4872.9  319.02  4887.1  320.92  4901.2  320.12  4915.4  315.92
  4929.5  312.23  4943.6  310.67  4957.6  310.66  5005.4  310.58  5005.7  310.08
  5009.2  310.08  5009.4  310.58  5013.8  310.61  5028.2  311.87  5050.6  315.36
  5057.0  318.11  5064.2  318.89  5085.9  319.29  5114.7  321.06  5156.3  322.86
  5192.3  323.03  5263.5  324.99  5298.8  326.62  5313.2  327.04  5320.4  326.92
#Mann=5,-1,0
  4575.9    0.07       0  4804.0    0.12       0  4957.6    0.07       0
  5005.4    0.05       0  5009.4    0.07       0
Bank Sta=5005.4,5009.4
Exp/Cntr=0.3,0.1

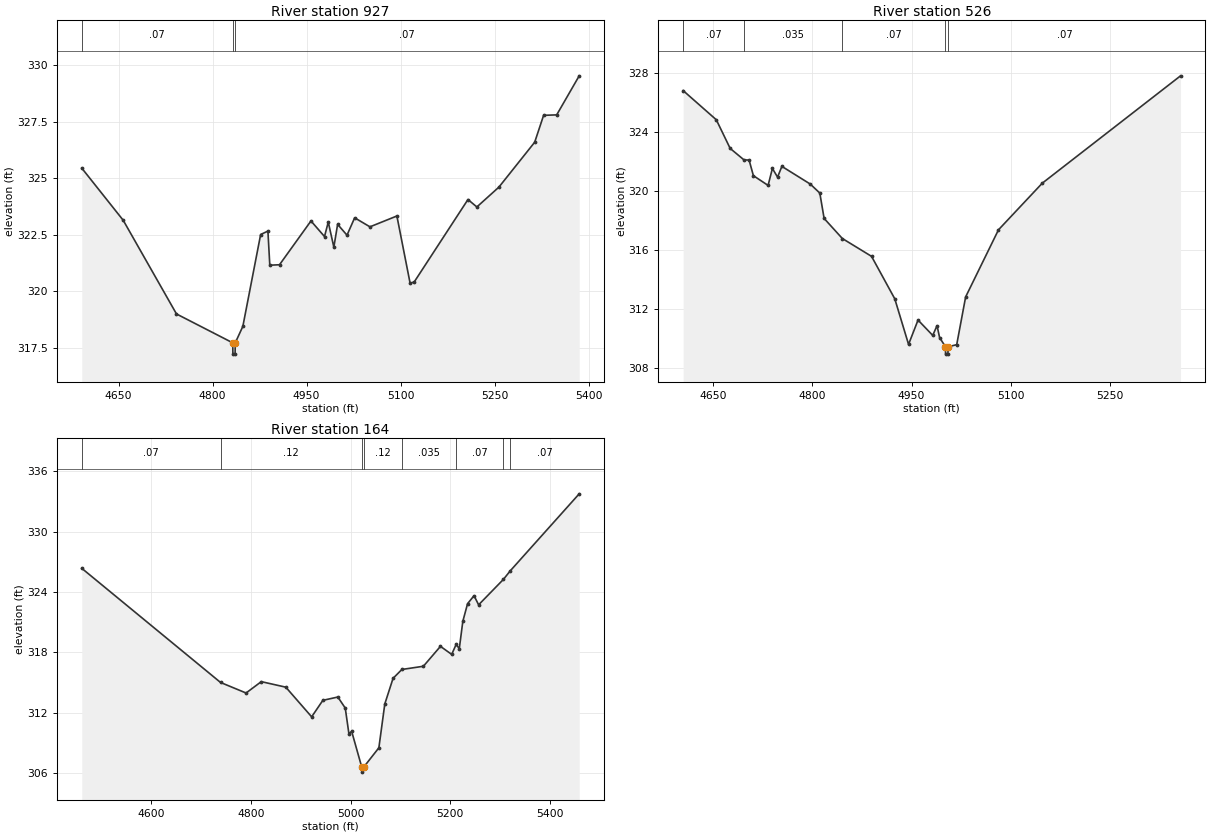
Type RM Length L Ch R = 1,927,401,401,401
BEGIN DESCRIPTION:
Stream0805 2.0a
END DESCRIPTION:
XS GIS Cut Line= 6
      2450664.63     13576081.84      2450869.72     13576296.61
      2450877.46     13576370.15      2450931.64     13576406.91
      2450993.57     13576401.11      2451218.05     13576592.69
#Sta/Elev= 30
  4591.4  325.45  4657.5  323.14  4742.5  318.99  4832.3  317.71  4832.5  317.21
  4836.0  317.21  4836.3  317.71  4848.4  318.44  4876.8  322.51  4888.4  322.66
  4891.4  321.15  4906.9  321.17  4957.1  323.11  4978.7  322.42  4984.7  323.06
  4993.6  321.95  4999.6  322.96  5014.6  322.48  5026.8  323.25  5051.2  322.85
  5094.2  323.33  5115.3  320.35  5121.9  320.41  5207.6  324.06  5221.8  323.73
  5257.0  324.61  5314.1  326.60  5328.3  327.79  5349.2  327.81  5385.1  329.54
#Mann=3,-1,0
  4591.4    0.07       0  4832.3    0.05       0  4836.3    0.07       0
Bank Sta=4832.3,4836.3
Exp/Cntr=0.3,0.1

Type RM Length L Ch R = 1,526,362,362,362
BEGIN DESCRIPTION:
Stream0805 1.0
END DESCRIPTION:
XS GIS Cut Line= 3
      2450374.98     13576374.97      2450625.00     13576675.00
      2450925.00     13576875.00
#Sta/Elev= 30
  4605.0  326.80  4655.1  324.82  4676.0  322.88  4696.9  322.10  4704.6  322.09
  4711.1  321.03  4733.3  320.37  4739.8  321.52  4747.6  320.93  4754.1  321.66
  4797.0  320.46  4811.4  319.85  4817.9  318.13  4845.4  316.77  4889.5  315.56
  4924.6  312.68  4945.4  309.59  4959.7  311.24  4981.9  310.20  4988.4  310.86
  4992.3  310.05  5001.1  309.43  5001.3  308.93  5004.8  308.93  5005.1  309.43
  5018.1  309.57  5031.6  312.81  5081.2  317.36  5147.3  320.52  5356.1  327.80
#Mann=5,-1,0
  4605.0    0.07       0  4696.9   0.035       0  4845.4    0.07       0
  5001.1    0.05       0  5005.1    0.07       0
Bank Sta=5001.1,5005.1
Exp/Cntr=0.3,0.1

Type RM Length L Ch R = 1,164,0,0,0
BEGIN DESCRIPTION:
XS7753
END DESCRIPTION:
XS GIS Cut Line= 3
      2450187.13     13576500.06      2450338.84     13576916.77
      2450832.78     13577170.79
#Sta/Elev= 30
  4460.2  326.35  4738.8  315.00  4790.1  313.95  4820.7  315.08  4869.9  314.53
  4921.8  311.58  4944.3  313.22  4974.4  313.55  4989.3  312.45  4996.6  309.91
  5002.2  310.13  5022.4  306.58  5022.6  306.08  5026.4  306.58  5056.8  308.50
  5068.7  312.86  5085.3  315.41  5103.0  316.29  5146.2  316.61  5180.5  318.59
  5203.0  317.79  5212.0  318.78  5218.3  318.36  5225.4  321.08  5234.9  322.83
  5247.9  323.63  5257.1  322.72  5306.7  325.24  5321.0  326.12  5459.1  333.76
#Mann=8,-1,0
  4460.2    0.07       0  4738.8    0.12       0  5022.4    0.05       0
  5026.4    0.12       0  5103.0   0.035       0  5212.0    0.07       0
  5306.7   0.035       0  5321.0    0.07       0
Bank Sta=5022.4,5026.4
Exp/Cntr=0.3,0.1

Chan Stop Cuts=-1