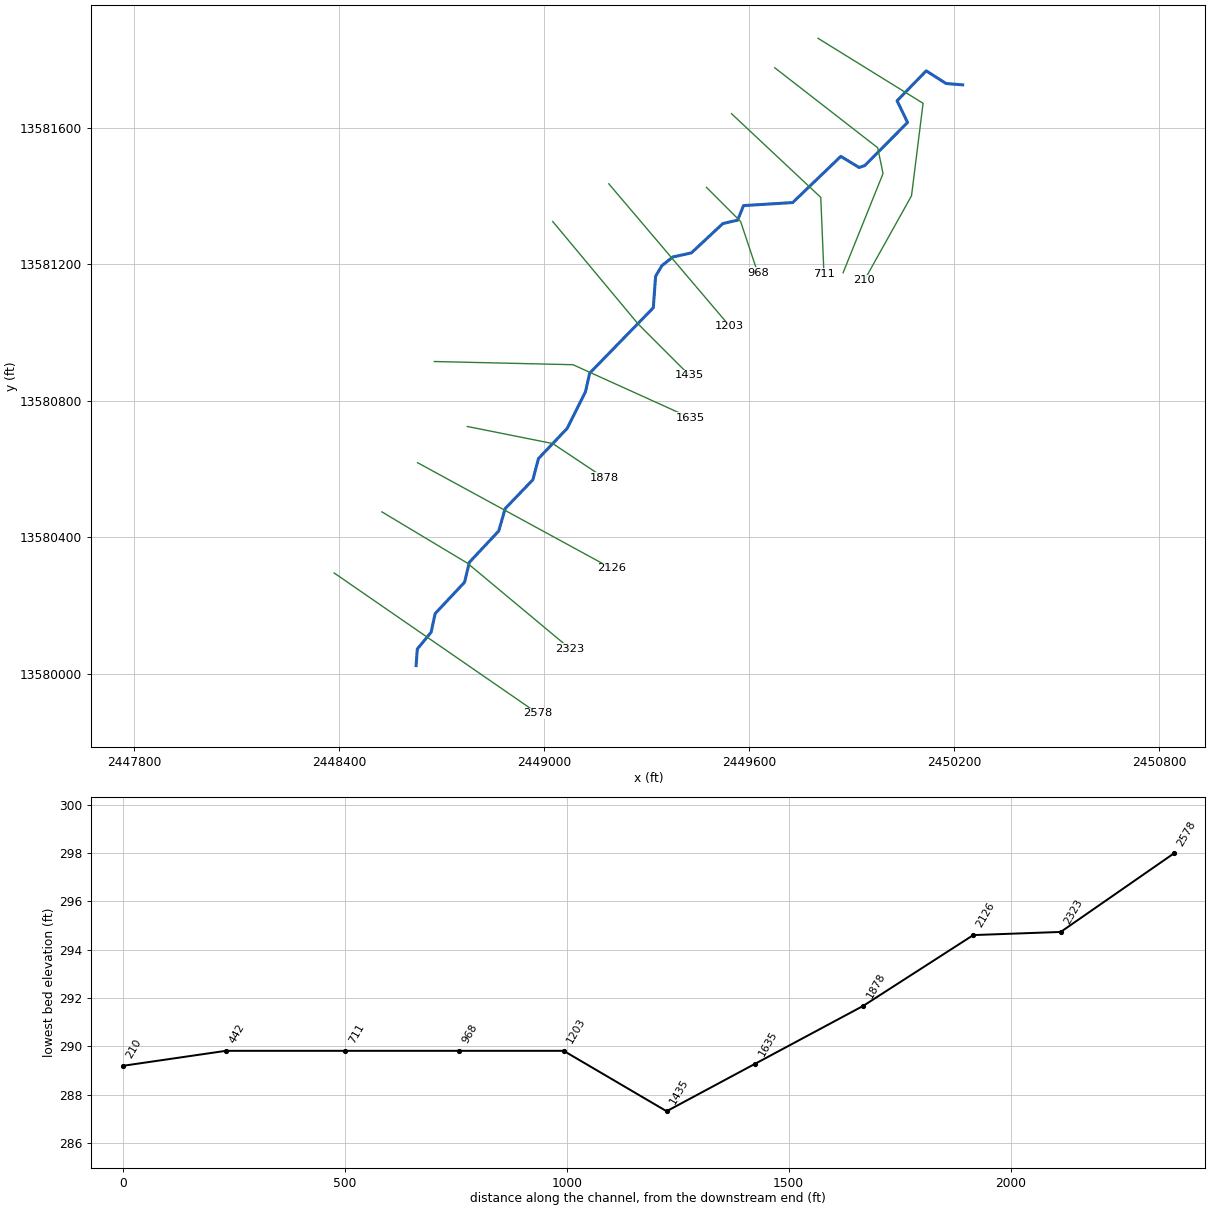
--- Stream0806.prj (project) ---

Proj Title=Stream0806 Base Level Engineering
Current Plan=p01
Default Exp/Contr=0.3,0.1
English Units
Geom File=g01
Flow File=f01
Plan File=p01
BEGIN DESCRIPTION:
Stream0806
END DESCRIPTION:

--- Stream0806.p01 (plan) ---

Plan Title=Multiple Run
Short Identifier=Multiple
Geom File=g01
Flow File=f01
Subcritical Flow
K Sum by GR= 0
Std Step Tol= 0.01
Critical Tol= 0.01
Num of Std Step Trials= 20
Max Error Tol= 0.3
Flow Tol Ratio= 0.001
Split Flow NTrial= 30
Split Flow Tol= 0.02
Split Flow Ratio= 0.02
Log Output Level= 0
Friction Slope Method= 1
Unsteady Friction Slope Method= 2
Unsteady Bridges Friction Slope Method= 1
Parabolic Critical Depth
Global Vel Dist=  1 , 1 , 1
Global Log Level= 0
CheckData=True
Encroach Param= -1, 0, 0, 0
BEGIN DESCRIPTION:
Multiple Run
END DESCRIPTION:

--- Stream0806.f01 (steady flow) ---

Flow Title=Multiple
Number of Profiles=7
Profile Names=10-year,25-year,50-year,1pct_min,100-year,1pct_plu,500-year
River Rch & RM= Stream0806,Reach-1,2578
     759    1251    1706    1127    2249    4487    3873
River Rch & RM= Stream0806,Reach-1,711
     774    1279    1746    1155    2304    4598    3977
Boundary for River Rch & Prof#=Stream0806,Reach-1,1
Up Type=0
Dn Type=3
Dn Slope=0.005
Boundary for River Rch & Prof#=Stream0806,Reach-1,2
Up Type=0
Dn Type=3
Dn Slope=0.005
Boundary for River Rch & Prof#=Stream0806,Reach-1,3
Up Type=0
Dn Type=3
Dn Slope=0.005
Boundary for River Rch & Prof#=Stream0806,Reach-1,4
Up Type=0
Dn Type=3
Dn Slope=0.005
Boundary for River Rch & Prof#=Stream0806,Reach-1,5
Up Type=0
Dn Type=3
Dn Slope=0.005
Boundary for River Rch & Prof#=Stream0806,Reach-1,6
Up Type=0
Dn Type=3
Dn Slope=0.005
Boundary for River Rch & Prof#=Stream0806,Reach-1,7
Up Type=0
Dn Type=3
Dn Slope=0.005

--- Stream0806.g01 (geometry) ---

Geom Title=Existing Conditions

River Reach=Stream0806,Reach-1
Reach XY= 30
      2448625.00     13580025.00      2448628.60     13580073.51
      2448669.03     13580122.76      2448680.83     13580177.30
      2448766.82     13580268.96      2448780.87     13580327.28
      2448866.82     13580418.96      2448885.80     13580484.67
      2448966.82     13580568.96      2448983.18     13580631.04
      2449066.84     13580718.95      2449120.81     13580826.74
      2449133.14     13580881.06      2449319.47     13581072.58
      2449326.10     13581164.67      2449344.47     13581195.54
      2449376.40     13581221.13      2449431.02     13581233.19
      2449523.02     13581319.06      2449566.34     13581328.94
      2449583.44     13581371.59      2449727.44     13581380.47
      2449868.33     13581515.70      2449921.67     13581483.16
      2449938.34     13581488.65      2450063.76     13581615.00
      2450033.00     13581678.36      2450118.25     13581766.02
      2450176.35     13581729.02      2450225.00     13581725.00

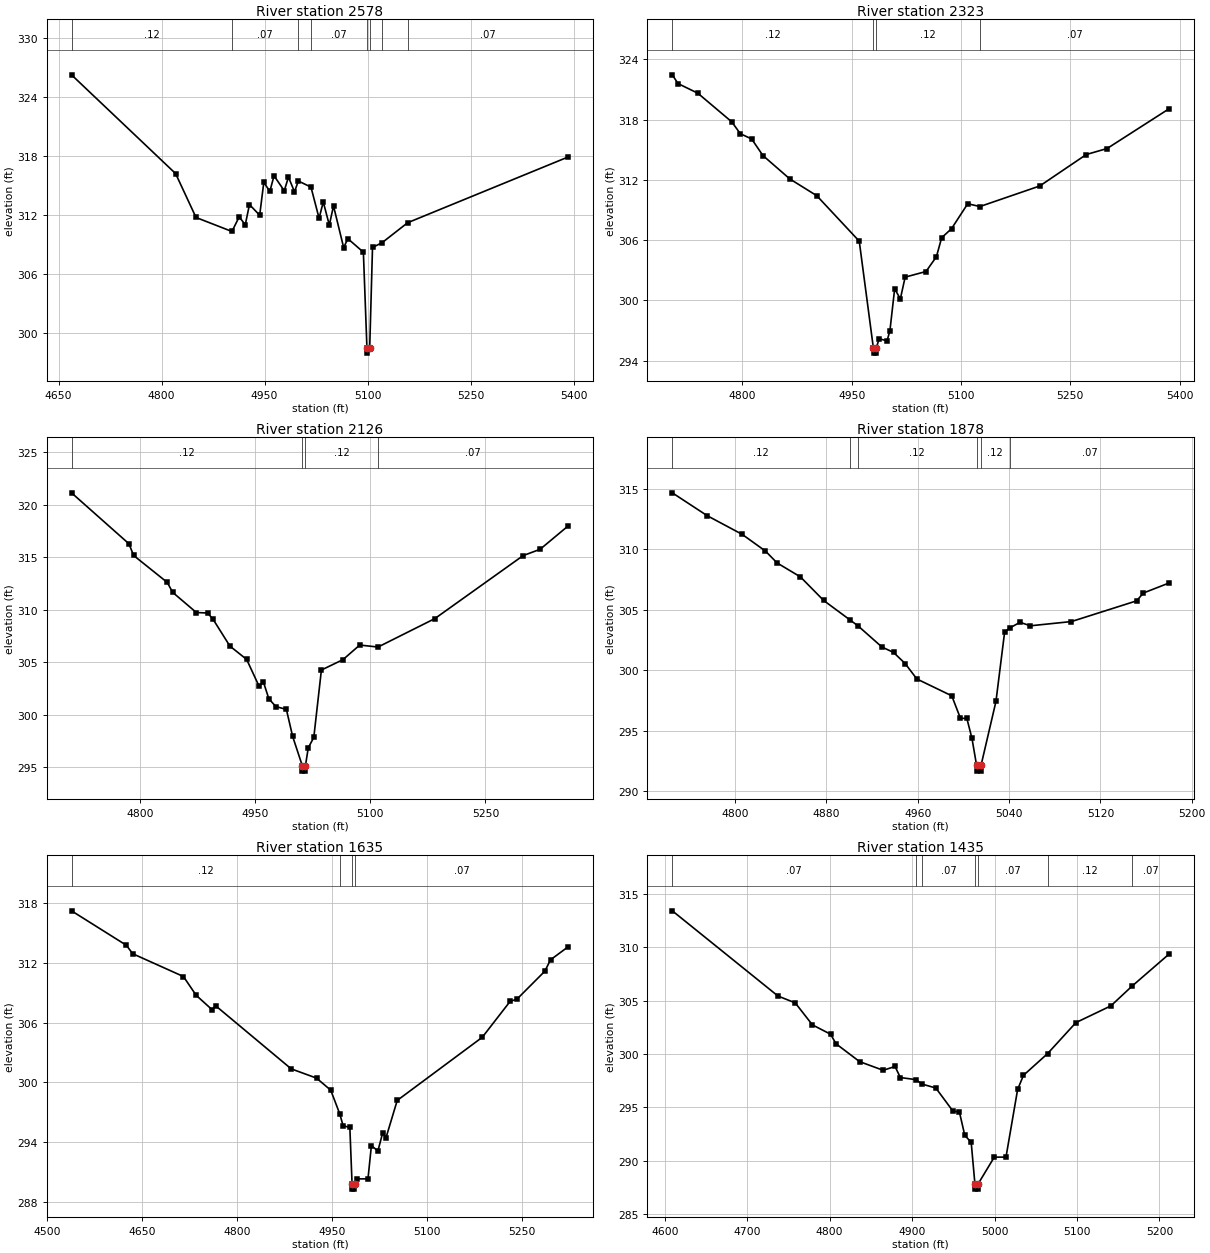
Type RM Length L Ch R = 1,2578,255,255,255
BEGIN DESCRIPTION:
XS7754
END DESCRIPTION:
XS GIS Cut Line= 2
      2448385.20     13580296.07      2448980.79     13579885.13
#Sta/Elev= 30
  4668.8  326.22  4820.4  316.20  4850.1  311.75  4902.4  310.33  4913.0  311.82
  4921.8  311.00  4927.9  313.06  4942.8  311.98  4948.8  315.31  4957.6  314.40
  4963.7  315.98  4978.6  314.46  4984.7  315.85  4993.5  314.35  4999.1  315.45
  5017.5  314.83  5029.3  311.67  5035.4  313.33  5044.2  310.98  5050.3  312.92
  5065.1  308.69  5071.2  309.60  5093.8  308.23  5099.0  298.49  5099.2  297.99
  5103.0  298.49  5107.1  308.71  5121.0  309.19  5158.3  311.22  5392.4  317.90
#Mann=8,-1,0
  4668.8    0.12       0  4902.4    0.07       0  4999.1    0.12       0
  5017.5    0.07       0  5099.0    0.05       0  5103.0    0.07       0
  5121.0    0.12       0  5158.3    0.07       0
Bank Sta=5099,5103
Exp/Cntr=0.3,0.1

Type RM Length L Ch R = 1,2323,197,197,197
BEGIN DESCRIPTION:
Stream0806 5.0
END DESCRIPTION:
XS GIS Cut Line= 3
      2448524.98     13580475.01      2448775.00     13580325.00
      2449075.01     13580074.99
#Sta/Elev= 30
  4703.8  322.46  4711.6  321.59  4738.8  320.63  4785.5  317.77  4797.1  316.60
  4812.7  316.07  4828.2  314.42  4865.1  312.09  4902.1  310.42  4960.4  305.89
  4979.8  295.24  4980.0  294.74  4983.5  294.74  4983.8  295.24  4987.6  296.17
  4998.6  295.97  5002.5  296.98  5009.0  301.15  5016.8  300.14  5023.4  302.31
  5052.0  302.87  5066.3  304.34  5073.5  306.23  5087.1  307.14  5109.3  309.62
  5126.0  309.34  5208.2  311.39  5272.0  314.52  5300.6  315.12  5385.9  319.09
#Mann=4,-1,0
  4703.8    0.12       0  4979.8    0.05       0  4983.8    0.12       0
  5126.0    0.07       0
Bank Sta=4979.8,4983.8
Exp/Cntr=0.3,0.1

Type RM Length L Ch R = 1,2126,248,248,248
BEGIN DESCRIPTION:
H21086
END DESCRIPTION:
XS GIS Cut Line= 2
      2448629.40     13580618.94      2449197.40     13580309.33
#Sta/Elev= 30
  4711.2  321.12  4785.9  316.27  4792.1  315.15  4835.8  312.59  4842.9  311.64
  4873.7  309.72  4888.4  309.67  4895.6  309.06  4917.4  306.52  4939.2  305.25
  4955.4  302.69  4961.1  303.08  4968.1  301.50  4977.2  300.76  4990.9  300.49
  4999.1  297.91  5011.7  295.11  5011.9  294.61  5015.4  294.61  5015.7  295.11
  5019.4  296.83  5026.6  297.82  5036.5  304.24  5064.6  305.23  5086.4  306.62
  5110.2  306.43  5184.2  309.14  5299.1  315.14  5321.2  315.74  5358.1  317.99
#Mann=4,-1,0
  4711.2    0.12       0  5011.7    0.05       0  5015.7    0.12       0
  5110.2    0.07       0
Bank Sta=5011.7,5015.7
Exp/Cntr=0.3,0.1

Type RM Length L Ch R = 1,1878,243,243,243
BEGIN DESCRIPTION:
Stream0806 4.0
END DESCRIPTION:
XS GIS Cut Line= 3
      2448774.95     13580725.01      2449025.00     13580675.00
      2449175.02     13580574.99
#Sta/Elev= 30
  4745.0  314.66  4775.6  312.77  4806.2  311.23  4826.6  309.85  4836.8  308.87
  4857.2  307.72  4877.6  305.77  4900.7  304.16  4907.6  303.68  4928.6  301.93
  4938.8  301.48  4949.0  300.56  4959.2  299.29  4989.8  297.90  4997.4  296.04
  5003.0  296.04  5007.5  294.38  5011.5  292.18  5011.8  291.68  5015.3  291.68
  5015.5  292.18  5028.5  297.43  5036.1  303.16  5040.4  303.49  5049.6  303.97
  5058.6  303.68  5094.6  304.03  5151.7  305.74  5157.7  306.39  5180.3  307.22
#Mann=6,-1,0
  4745.0    0.12       0  4900.7    0.07       0  4907.6    0.12       0
  5011.5    0.05       0  5015.5    0.12       0  5040.4    0.07       0
Bank Sta=5011.5,5015.5
Exp/Cntr=0.3,0.1

Type RM Length L Ch R = 1,1635,200,200,200
BEGIN DESCRIPTION:
H21085
END DESCRIPTION:
XS GIS Cut Line= 3
      2448678.39     13580915.14      2449084.26     13580905.81
      2449428.91     13580749.78
#Sta/Elev= 30
  4538.8  317.24  4625.4  313.78  4635.4  312.93  4715.5  310.64  4735.5  308.76
  4760.5  307.32  4766.4  307.70  4885.5  301.37  4925.5  300.44  4947.9  299.23
  4962.1  296.86  4967.5  295.65  4978.1  295.49  4981.6  289.79  4981.8  289.29
  4985.3  289.29  4985.6  289.79  4989.5  290.32  5006.7  290.32  5012.1  293.65
  5022.4  293.13  5029.8  294.91  5035.2  294.46  5052.9  298.20  5187.1  304.54
  5231.0  308.14  5242.0  308.38  5285.9  311.18  5294.8  312.32  5323.1  313.65
#Mann=4,-1,0
  4538.8    0.12       0  4962.1    0.07       0  4981.6    0.05       0
  4985.6    0.07       0
Bank Sta=4981.6,4985.6
Exp/Cntr=0.3,0.1

Type RM Length L Ch R = 1,1435,232,232,232
BEGIN DESCRIPTION:
Stream0806 3.0
END DESCRIPTION:
XS GIS Cut Line= 3
      2449024.99     13581325.01      2449275.00     13581025.00
      2449425.03     13580874.97
#Sta/Elev= 30
  4609.2  313.41  4737.4  305.42  4758.3  304.78  4779.1  302.72  4801.2  301.84
  4807.7  300.95  4836.4  299.27  4865.0  298.46  4879.3  298.82  4885.8  297.78
  4904.2  297.59  4912.4  297.16  4928.8  296.80  4949.6  294.63  4957.4  294.55
  4963.9  292.37  4971.7  291.70  4976.2  287.82  4976.5  287.32  4980.0  287.32
  4980.2  287.82  4999.7  290.32  5013.9  290.32  5028.0  296.66  5035.1  297.99
  5064.3  300.02  5098.7  302.93  5141.1  304.50  5166.5  306.33  5211.9  309.37
#Mann=7,-1,0
  4609.2    0.07       0  4904.2    0.12       0  4912.4    0.07       0
  4976.2    0.05       0  4980.2    0.07       0  5064.3    0.12       0
  5166.5    0.07       0
Bank Sta=4976.2,4980.2
Exp/Cntr=0.3,0.1

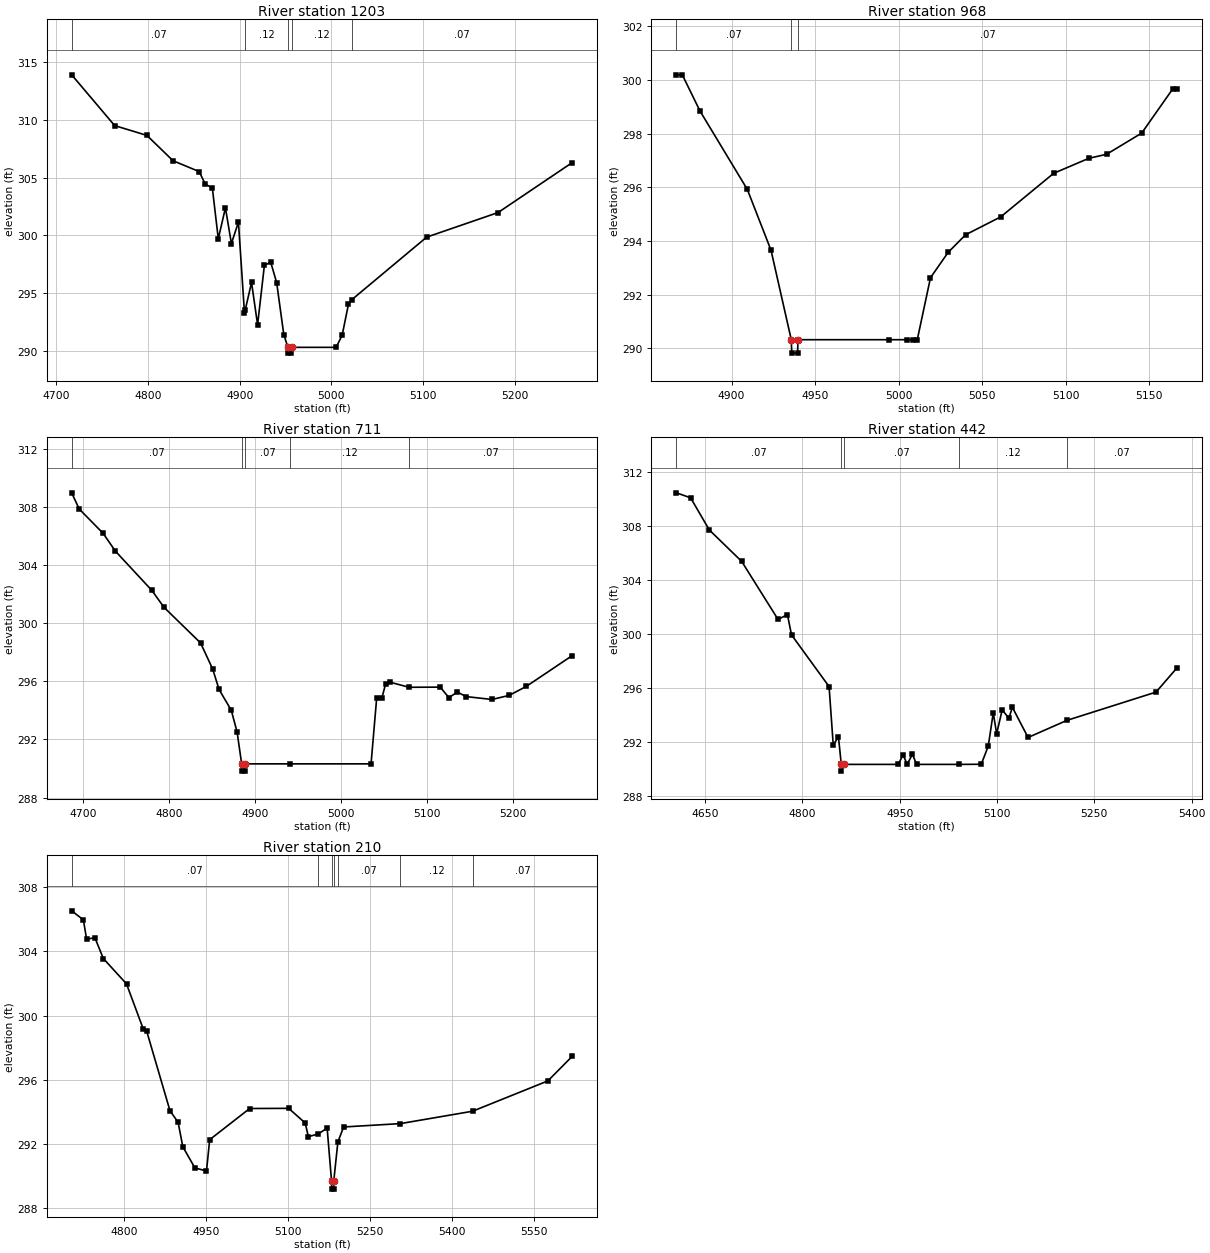
Type RM Length L Ch R = 1,1203,235,235,235
BEGIN DESCRIPTION:
H21084
END DESCRIPTION:
XS GIS Cut Line= 2
      2449189.21     13581435.28      2449542.81     13581018.86
#Sta/Elev= 30
  4716.7  313.89  4763.6  309.50  4798.8  308.65  4827.3  306.46  4855.9  305.52
  4862.5  304.43  4870.2  304.11  4876.7  299.71  4884.5  302.39  4891.0  299.30
  4898.7  301.15  4905.3  293.28  4906.0  293.52  4913.0  295.93  4919.6  292.27
  4927.0  297.40  4933.9  297.69  4940.4  295.92  4948.2  291.42  4952.7  290.32
  4953.0  289.82  4956.5  289.82  4956.7  290.32  5005.3  290.32  5011.9  291.37
  5018.8  294.06  5022.1  294.42  5104.1  299.85  5182.1  301.98  5263.0  306.30
#Mann=5,-1,0
  4716.7    0.07       0  4906.0    0.12       0  4952.7    0.05       0
  4956.7    0.12       0  5022.1    0.07       0
Bank Sta=4952.7,4956.7
Exp/Cntr=0.3,0.1

Type RM Length L Ch R = 1,968,257,257,257
BEGIN DESCRIPTION:
Stream0806 2.0
END DESCRIPTION:
XS GIS Cut Line= 3
      2449475.00     13581425.00      2449575.00     13581325.00
      2449624.99     13581175.03
#Sta/Elev= 23
  4867.0  300.19  4870.5  300.19  4881.1  298.84  4909.4  295.92  4923.6  293.65
  4935.7  290.32  4936.0  289.82  4939.5  289.82  4939.7  290.32  4994.3  290.32
  5004.9  290.32  5008.4  290.32  5011.1  290.32  5019.0  292.63  5029.5  293.57
  5040.0  294.23  5061.1  294.90  5092.7  296.52  5113.8  297.08  5124.4  297.23
  5145.4  298.02  5163.9  299.66  5166.5  299.66
#Mann=3,-1,0
  4867.0    0.07       0  4935.7    0.05       0  4939.7    0.07       0
Bank Sta=4935.7,4939.7
Exp/Cntr=0.3,0.1

Type RM Length L Ch R = 1,711,269,269,269
BEGIN DESCRIPTION:
H21083
END DESCRIPTION:
XS GIS Cut Line= 3
      2449548.43     13581640.50      2449809.64     13581395.61
      2449818.97     13581171.65
#Sta/Elev= 30
  4687.0  308.97  4695.7  307.86  4723.6  306.18  4737.8  304.96  4780.3  302.25
  4794.4  301.09  4836.9  298.64  4851.1  296.83  4858.4  295.44  4872.6  294.01
  4879.4  292.51  4884.7  290.32  4885.0  289.82  4888.5  289.82  4888.7  290.32
  4940.8  290.32  5035.2  290.32  5041.8  294.88  5047.9  294.88  5052.2  295.83
  5057.2  295.94  5079.4  295.59  5115.7  295.60  5125.7  294.88  5135.7  295.26
  5145.7  294.95  5175.8  294.75  5195.8  295.03  5215.8  295.65  5269.2  297.77
#Mann=5,-1,0
  4687.0    0.07       0  4884.7    0.05       0  4888.7    0.07       0
  4940.8    0.12       0  5079.4    0.07       0
Bank Sta=4884.7,4888.7
Exp/Cntr=0.3,0.1

Type RM Length L Ch R = 1,442,232,232,232
BEGIN DESCRIPTION:
Stream0806 1.0
END DESCRIPTION:
XS GIS Cut Line= 4
      2449674.98     13581775.02      2449976.30     13581540.89
      2449991.93     13581465.36      2449875.01     13581175.04
#Sta/Elev= 30
  4605.7  310.49  4627.5  310.12  4656.4  307.73  4706.2  305.40  4762.3  301.09
  4776.8  301.44  4783.1  299.94  4841.0  296.10  4847.4  291.78  4855.5  292.35
  4859.8  290.32  4860.1  289.82  4863.8  290.32  4947.7  290.32  4955.1  291.04
  4961.4  290.32  4969.5  291.08  4975.9  290.32  5041.2  290.32  5075.6  290.33
  5086.4  291.67  5094.1  294.14  5099.4  292.60  5107.9  294.37  5118.2  293.75
  5123.6  294.56  5147.8  292.32  5207.7  293.59  5345.1  295.69  5377.4  297.49
#Mann=5,-1,0
  4605.7    0.07       0  4859.8    0.05       0  4863.8    0.07       0
  5041.2    0.12       0  5207.7    0.07       0
Bank Sta=4859.8,4863.8
Exp/Cntr=0.3,0.1

Type RM Length L Ch R = 1,210,0,0,0
BEGIN DESCRIPTION:
XS7755
END DESCRIPTION:
XS GIS Cut Line= 4
      2449801.79     13581861.22      2450109.11     13581671.09
      2450075.26     13581400.26      2449937.25     13581152.88
#Sta/Elev= 30
  4703.3  306.53  4724.7  305.97  4730.6  304.77  4745.9  304.85  4761.3  303.56
  4803.8  301.98  4834.6  299.16  4840.5  299.07  4883.5  294.08  4898.4  293.36
  4907.0  291.84  4929.2  290.52  4950.4  290.33  4956.3  292.28  5029.6  294.22
  5101.1  294.23  5131.3  293.32  5137.2  292.47  5155.1  292.63  5171.6  293.00
  5179.7  289.70  5179.9  289.20  5183.4  289.20  5183.7  289.70  5191.3  292.14
  5201.8  293.07  5305.9  293.28  5438.1  294.05  5576.3  295.94  5620.9  297.47
#Mann=7,-1,0
  4703.3    0.07       0  5155.1    0.12       0  5179.7    0.05       0
  5183.7    0.12       0  5191.3    0.07       0  5305.9    0.12       0
  5438.1    0.07       0
Bank Sta=5179.7,5183.7
Exp/Cntr=0.3,0.1

Chan Stop Cuts=-1