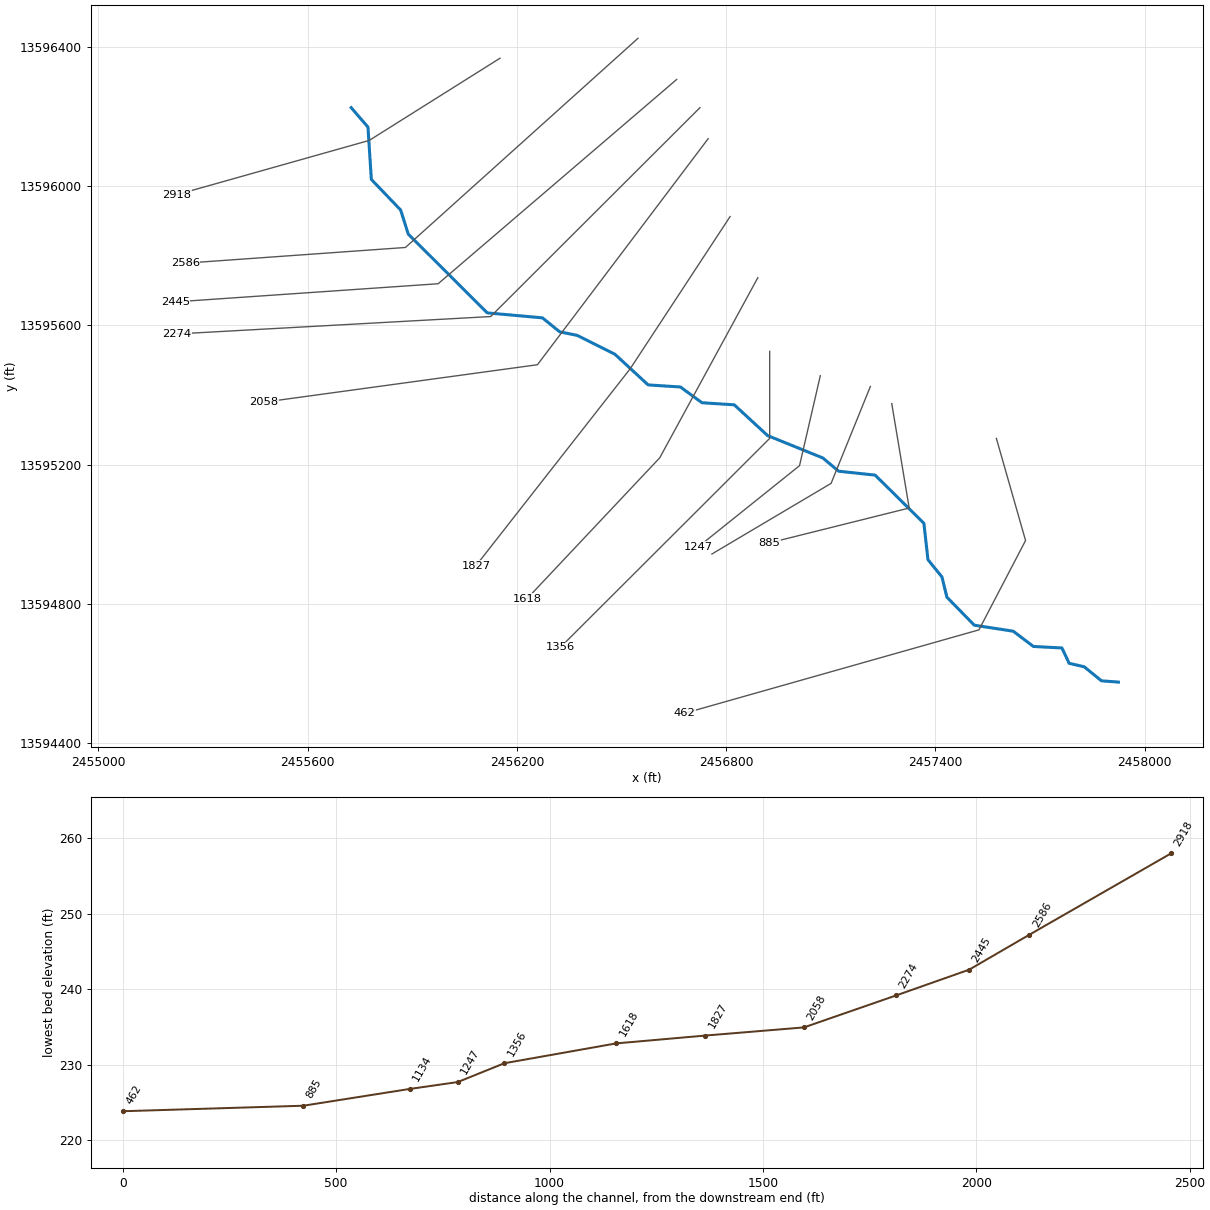
--- Stream0807.prj (project) ---

Proj Title=Stream0807 Base Level Engineering
Current Plan=p01
Default Exp/Contr=0.3,0.1
English Units
Geom File=g01
Flow File=f01
Plan File=p01
Y Axis Title=Elevation
X Axis Title(PF)=Main Channel Distance
X Axis Title(XS)=Station
BEGIN DESCRIPTION:
Stream0807
END DESCRIPTION:
DSS Export Rating Curves= 0
DSS Export Rating Curve Sorted= 0
DSS Export Volume Flow Curves= 0
DXF OffsetX= 0
DXF OffsetY= 0
DXF ScaleX= 1
DXF ScaleY= 10

--- Stream0807.p01 (plan) ---

Plan Title=Multiple Run
Short Identifier=Multiple
Geom File=g01
Flow File=f01
Subcritical Flow
K Sum by GR= 0
Std Step Tol= 0.01
Critical Tol= 0.01
Num of Std Step Trials= 20
Max Error Tol= 0.3
Flow Tol Ratio= 0.001
Split Flow NTrial= 30
Split Flow Tol= 0.02
Split Flow Ratio= 0.02
Log Output Level= 0
Friction Slope Method= 1
Unsteady Friction Slope Method= 2
Unsteady Bridges Friction Slope Method= 1
Parabolic Critical Depth
Global Vel Dist=  1 , 1 , 1
Global Log Level= 0
CheckData=True
Encroach Param= -1, 0, 0, 0
BEGIN DESCRIPTION:
Multiple Run
END DESCRIPTION:

--- Stream0807.f01 (steady flow) ---

Flow Title=Multiple
Number of Profiles=7
Profile Names=10-year,25-year,50-year,1pct_min,100-year,1pct_plu,500-year
River Rch & RM= Stream0807,Reach-1,2918
     509     819    1098     716    1428    2849    2387
Boundary for River Rch & Prof#=Stream0807,Reach-1,1
Up Type=0
Dn Type=3
Dn Slope=0.005
Boundary for River Rch & Prof#=Stream0807,Reach-1,2
Up Type=0
Dn Type=3
Dn Slope=0.005
Boundary for River Rch & Prof#=Stream0807,Reach-1,3
Up Type=0
Dn Type=3
Dn Slope=0.005
Boundary for River Rch & Prof#=Stream0807,Reach-1,4
Up Type=0
Dn Type=3
Dn Slope=0.005
Boundary for River Rch & Prof#=Stream0807,Reach-1,5
Up Type=0
Dn Type=3
Dn Slope=0.005
Boundary for River Rch & Prof#=Stream0807,Reach-1,6
Up Type=0
Dn Type=3
Dn Slope=0.005
Boundary for River Rch & Prof#=Stream0807,Reach-1,7
Up Type=0
Dn Type=3
Dn Slope=0.005

--- Stream0807.g01 (geometry) ---

Geom Title=Existing Conditions
Program Version=4.10

River Reach=Stream0807      ,Reach-1
Reach XY= 30
        2455725.       13596225.      2455773.09     13596169.21
      2455782.83     13596018.82      2455866.82     13595931.04
      2455888.63     13595861.79       2456115.2     13595635.48
      2456273.44     13595621.24      2456322.82     13595581.12
      2456373.28     13595570.84      2456481.05     13595516.84
       2456576.5     13595428.62      2456669.02     13595422.64
      2456730.98     13595377.36       2456823.5     13595371.38
      2456918.95     13595283.16      2457077.18     13595218.88
      2457122.68     13595180.77      2457227.43     13595169.48
      2457367.14     13595031.17      2457378.83     13594926.59
      2457418.86     13594877.17      2457433.13     13594818.92
      2457511.67     13594738.39      2457623.41     13594721.14
      2457681.06     13594677.38      2457763.01     13594672.97
      2457783.62     13594628.88       2457826.9     13594618.94
      2457876.45     13594578.59        2457925.       13594575.

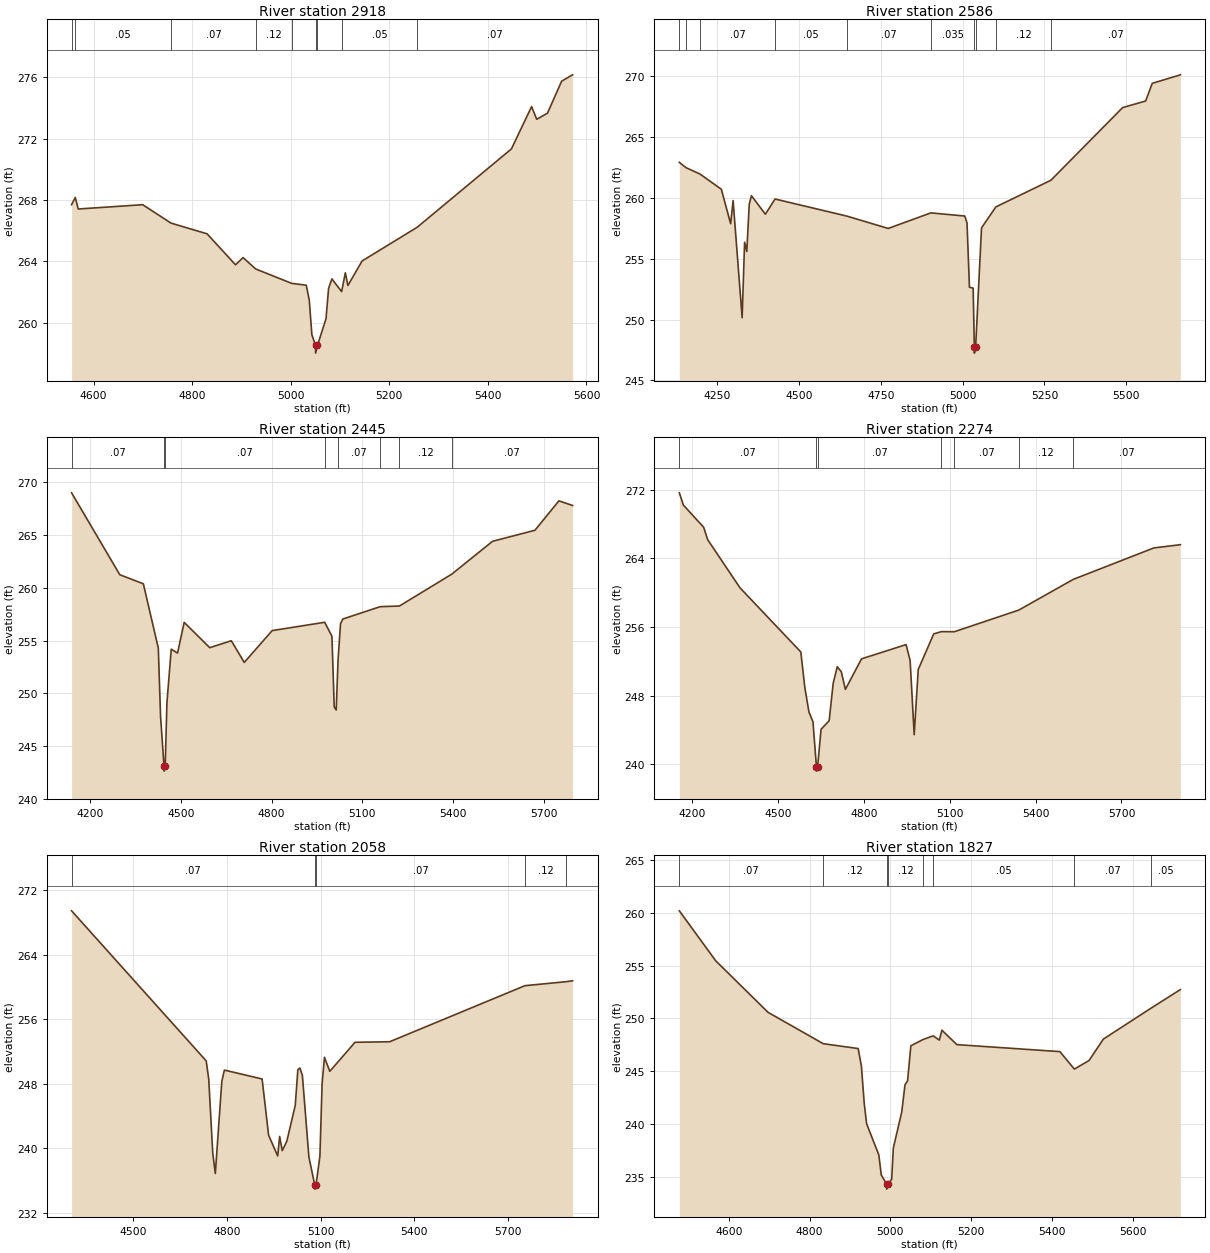
Type RM Length L Ch R = 1 ,2918    ,332,332,332
BEGIN DESCRIPTION:
Stream0807 6.0
END DESCRIPTION:
XS GIS Cut Line= 3
      2456151.73     13596367.01      2455776.74      13596130.9
      2455224.97     13595974.99
#Sta/Elev= 30
  4555.4   267.7  4562.9  268.17  4568.9  267.42  4699.6   267.7  4757.1   266.5
  4830.3   265.8    4888  263.78  4903.3  264.25  4928.8  263.51  5001.9  262.57
  5031.5  262.45  5037.7  261.45  5042.9  259.22  5050.3  258.52  5050.5  258.02
  5054.3  258.52  5071.6  260.27  5076.8  262.24  5083.5  262.86  5103.3  262.03
  5110.8  263.26    5116  262.43  5144.8  264.03  5256.6  266.23  5447.8  271.34
  5488.7   274.1  5499.1  273.27  5520.9  273.67  5549.7  275.76  5571.9  276.17
#Mann= 9 ,-1 , 0
  4555.4     .07       0  4562.9     .05       0  4757.1     .07       0
  4928.8     .12       0  5001.9     .07       0  5050.3     .05       0
  5054.3     .07       0  5103.3     .05       0  5256.6     .07       0
Bank Sta=5050.3,5054.3
XS Rating Curve= 0 ,0
Exp/Cntr=0.3,0.1

Type RM Length L Ch R = 1 ,2586    ,141,141,141
BEGIN DESCRIPTION:
H21092
END DESCRIPTION:
XS GIS Cut Line= 3
      2456547.26     13596424.13      2455880.56      13595823.4
      2455249.28     13595778.31
#Sta/Elev= 30
  4134.8  262.91  4155.4  262.47    4198  261.95  4263.1   260.7  4291.5  257.87
    4299  259.77  4326.6  250.15  4334.1  256.35  4340.8  255.59  4348.3  259.47
    4355  260.17  4397.6  258.65  4427.1   259.9  4647.1  258.49  4772.8  257.48
    4903  258.76  5006.7   258.5  5013.5  257.92  5020.9  252.65  5032.2  252.58
  5035.8  247.74    5036  247.24  5039.8  247.74  5057.8  257.53  5101.6  259.25
  5269.7  261.44  5488.9  267.41  5559.1  267.95  5579.2   269.4  5665.1   270.1
#Mann= 10 ,-1 , 0
  4134.8     .07       0  4155.4     .12       0    4198     .07       0
  4427.1     .05       0  4647.1     .07       0    4903    .035       0
  5035.8     .05       0  5039.8    .035       0  5101.6     .12       0
  5269.7     .07       0
Bank Sta=5035.8,5039.8
XS Rating Curve= 0 ,0
Exp/Cntr=0.3,0.1

Type RM Length L Ch R = 1 ,2445    ,171,171,171
BEGIN DESCRIPTION:
H21091
END DESCRIPTION:
XS GIS Cut Line= 3
      2456658.32     13596306.03      2455974.31     13595719.23
      2455220.82     13595667.15
#Sta/Elev= 30
  4138.8  269.01  4298.2  261.24  4376.1  260.38  4425.5  254.28    4433  247.79
  4444.3  243.11  4444.6  242.61  4448.3  243.11    4454  249.09  4468.3  254.18
  4489.1  253.81  4511.1  256.72  4595.6  254.32  4666.9  254.98  4709.7  252.92
  4801.9  255.94  4975.7  256.73  4999.6   255.4  5007.1  248.71  5013.7  248.41
  5019.8  253.17    5028   256.6  5035.7  257.04  5159.1  258.21  5222.6  258.27
  5395.5  261.29  5530.5  264.41  5670.8  265.46    5750  268.25  5795.3  267.81
#Mann= 8 ,-1 , 0
  4138.8     .07       0  4444.3    .035       0  4448.3     .07       0
  4975.7    .035       0  5019.8     .07       0  5159.1    .035       0
  5222.6     .12       0  5395.5     .07       0
Bank Sta=4444.3,4448.3
XS Rating Curve= 0 ,0
Exp/Cntr=0.3,0.1

Type RM Length L Ch R = 1 ,2274    ,216,216,216
BEGIN DESCRIPTION:
Stream0807 5.0
END DESCRIPTION:
XS GIS Cut Line= 3
      2456725.03     13596225.03        2456125.       13595625.
      2455224.96       13595575.
#Sta/Elev= 30
  4155.7  271.62  4169.9  270.19  4240.6  267.61  4254.7  266.16  4367.9  260.54
    4580  253.08  4594.1  248.92  4608.3   246.1  4622.4  244.95  4634.6   239.7
  4634.8   239.2  4638.6   239.7  4650.7  244.07    4679  245.08  4693.1  249.44
  4707.3  251.36  4721.4  250.77  4735.6  248.72  4792.1  252.28  4947.7  253.94
  4961.8  252.08    4976  243.44  4990.1  251.04  5044.3  255.19  5071.2  255.45
  5116.4  255.44  5341.3  257.96  5531.8  261.54    5813   265.2  5905.7  265.58
#Mann= 7 ,-1 , 0
  4155.7     .07       0  4634.6     .05       0  4638.6     .07       0
  5071.2    .035       0  5116.4     .07       0  5341.3     .12       0
  5531.8     .07       0
Bank Sta=4634.6,4638.6
XS Rating Curve= 0 ,0
Exp/Cntr=0.3,0.1

Type RM Length L Ch R = 1 ,2058    ,231,231,231
BEGIN DESCRIPTION:
H21089
END DESCRIPTION:
XS GIS Cut Line= 3
      2456748.59     13596135.87      2456259.03      13595486.6
      2455474.33     13595378.96
#Sta/Elev= 30
  4302.1  269.42  4733.4  250.84  4741.5  248.58  4754.3  239.45  4762.6  236.89
  4783.4   248.3  4791.6   249.7  4912.5   248.6  4933.3  241.64  4962.4  239.07
  4968.7  241.48    4977  239.73  4991.6  240.88  5018.7  245.33    5027  249.74
  5033.2  249.96  5041.5  249.06  5062.4  238.94  5081.2  235.46  5081.4  234.96
  5085.2  235.46  5097.7  239.04  5104.7  248.01  5112.3  251.28  5129.4  249.55
  5210.2  253.14  5321.2  253.21  5754.5  260.15  5887.6  260.65  5907.3  260.76
#Mann= 5 ,-1 , 0
  4302.1     .07       0  5081.2     .05       0  5085.2     .07       0
  5754.5     .12       0  5887.6     .07       0
Bank Sta=5081.2,5085.2
XS Rating Curve= 0 ,0
Exp/Cntr=0.3,0.1

Type RM Length L Ch R = 1 ,1827    ,209,209,209
BEGIN DESCRIPTION:
Stream0807 4.0
END DESCRIPTION:
XS GIS Cut Line= 3
      2456811.47     13595912.18        2456525.       13595475.
      2456082.78     13594909.31
#Sta/Elev= 30
  4477.3  260.17  4567.4  255.45    4697  250.58  4833.6  247.62  4920.1  247.16
  4928.2  245.49  4935.2  241.95  4941.1  240.05  4971.3  237.11  4977.3  235.22
  4990.4  234.38  4990.7  233.88  4994.4  234.38  5003.1  234.81  5007.2  237.76
    5028  241.16  5036.1  243.74  5042.5  244.11  5050.6  247.42    5080     248
  5105.8  248.36  5121.2  247.96  5127.5  248.89  5164.6  247.53  5419.6  246.87
  5455.5  245.22  5491.9  246.03  5527.2  248.05  5645.6  250.98    5718  252.73
#Mann= 8 ,-1 , 0
  4477.3     .07       0  4833.6     .12       0  4990.4     .05       0
  4994.4     .12       0    5080     .07       0  5105.8     .05       0
  5455.5     .07       0  5645.6     .05       0
Bank Sta=4990.4,4994.4
XS Rating Curve= 0 ,0
Exp/Cntr=0.3,0.1

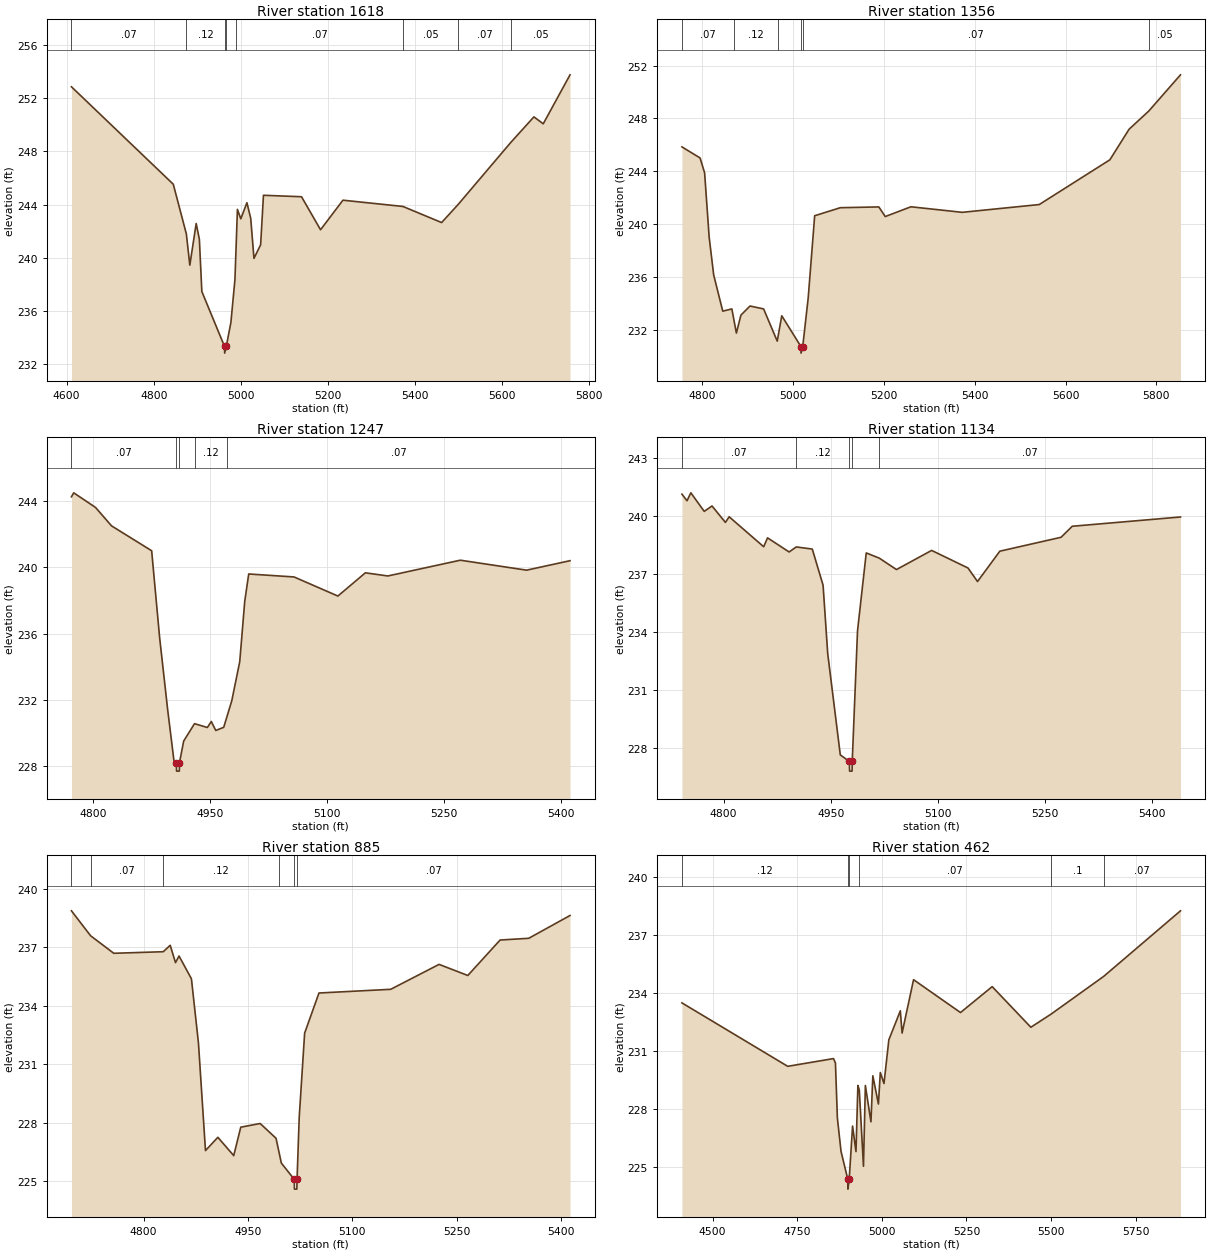
Type RM Length L Ch R = 1 ,1618    ,262,262,262
BEGIN DESCRIPTION:
H21090
END DESCRIPTION:
XS GIS Cut Line= 3
        2456891.     13595736.64      2456609.72     13595219.23
      2456228.89     13594814.16
#Sta/Elev= 30
  4611.1  252.85  4844.9  245.53  4874.9   241.8  4882.9  239.45  4897.5  242.58
  4904.8   241.4  4910.5  237.47  4962.6  233.34  4962.9  232.84  4966.6  233.34
  4977.2  235.14  4986.5  238.36  4988.8  240.49  4992.2  243.64    5000  242.93
    5014  244.14  5022.7  242.98  5030.2  239.96  5045.5  240.98    5052   244.7
  5139.4  244.59  5183.1  242.11  5234.5  244.33  5372.3  243.86  5461.1  242.65
  5498.3  243.98  5620.5  248.69  5673.1  250.59  5694.5  250.07    5756  253.75
#Mann= 8 ,-1 , 0
  4611.1     .07       0  4874.9     .12       0  4962.6     .05       0
  4966.6     .12       0  4988.8     .07       0  5372.3     .05       0
  5498.3     .07       0  5620.5     .05       0
Bank Sta=4962.6,4966.6
XS Rating Curve= 0 ,0
Exp/Cntr=0.3,0.1

Type RM Length L Ch R = 1 ,1356    ,109,109,109
BEGIN DESCRIPTION:
Stream0807 3.0
END DESCRIPTION:
XS GIS Cut Line= 3
        2456925.     13595525.05        2456925.       13595275.
      2456324.98     13594674.98
#Sta/Elev= 30
  4754.7  245.84  4794.7     245  4804.7  243.87  4814.7     239  4824.7  236.13
  4844.7  233.39  4864.7  233.56  4868.8  232.81  4874.7  231.73  4884.7  233.09
  4904.7  233.78  4934.7  233.56  4964.7  231.12  4967.4  231.64  4974.7  233.04
  5016.9  230.71  5017.1  230.21  5020.9  230.71    5033  234.41  5047.2  240.62
  5103.7  241.23  5188.6  241.29  5202.7  240.56  5259.3   241.3  5372.4  240.88
  5542.1  241.47  5697.7  244.86  5740.1  247.18  5783.3  248.55  5853.3   251.3
#Mann= 6 ,-1 , 0
  4754.7     .07       0  4868.8     .12       0  4967.4     .07       0
  5016.9     .05       0  5020.9     .07       0  5783.3     .05       0
Bank Sta=5016.9,5020.9
XS Rating Curve= 0 ,0
Exp/Cntr=0.3,0.1

Type RM Length L Ch R = 1 ,1247    ,113,113,113
BEGIN DESCRIPTION:
H21088
END DESCRIPTION:
XS GIS Cut Line= 3
      2457070.16     13595455.02      2457010.52      13595196.6
      2456719.47     13594962.87
#Sta/Elev= 30
  4772.6  244.25  4775.5  244.49  4803.4  243.61  4823.9   242.5  4875.3     241
  4885.5  235.77  4895.8  231.42  4903.8  228.37  4906.9  228.22  4907.2  227.72
  4910.7  227.72  4910.9  228.22  4916.3  229.53  4930.2  230.58  4946.6  230.35
  4951.7  230.71  4957.4  230.17  4967.6  230.36  4971.7     231  4977.9  231.96
  4988.1  234.31  4994.5  237.95  4999.6   239.6  5057.7  239.42  5113.8  238.27
    5149  239.67  5177.8  239.48  5270.6  240.43  5355.5  239.83  5411.1   240.4
#Mann= 5 ,-1 , 0
  4772.6     .07       0  4906.9     .05       0  4910.9     .07       0
  4930.2     .12       0  4971.7     .07       0
Bank Sta=4906.9,4910.9
XS Rating Curve= 0 ,0
Exp/Cntr=0.3,0.1

Type RM Length L Ch R = 1 ,1134    ,249,249,249
BEGIN DESCRIPTION:
H21087
END DESCRIPTION:
XS GIS Cut Line= 3
      2457213.71     13595424.07      2457101.07      13595145.8
      2456759.33     13594942.96
#Sta/Elev= 30
  4741.8  241.13  4748.9  240.79  4754.3   241.2    4773  240.24  4783.9  240.52
  4802.6  239.67  4807.9  239.96  4856.2  238.41  4861.6  238.87  4891.8  238.14
  4901.8   238.4  4924.2  238.29  4939.3  236.42  4945.8  232.88  4963.4  227.64
  4976.1   227.3  4976.4   226.8  4979.9   226.8  4980.1   227.3  4987.5  234.06
  4999.7  238.09    5018  237.82    5042  237.23  5091.2  238.22  5142.1  237.31
  5155.4  236.61  5186.6  238.18  5272.3   238.9    5288  239.47  5439.4  239.95
#Mann= 5 ,-1 , 0
  4741.8     .07       0  4901.8     .12       0  4976.1     .05       0
  4980.1     .12       0    5018     .07       0
Bank Sta=4976.1,4980.1
XS Rating Curve= 0 ,0
Exp/Cntr=0.3,0.1

Type RM Length L Ch R = 1 ,885     ,423,423,423
BEGIN DESCRIPTION:
Stream0807 2.0
END DESCRIPTION:
XS GIS Cut Line= 3
        2457275.     13595375.01        2457325.       13595075.
      2456924.96     13594974.99
#Sta/Elev= 30
  4696.3  238.87  4723.8  237.59  4757.1  236.69  4828.2  236.77  4838.2   237.1
  4845.8  236.21  4850.9  236.55  4868.7  235.38  4878.8  232.08  4888.9  226.56
  4906.7  227.24  4929.5   226.3  4939.6  227.76  4967.5  227.95  4990.3  227.19
  4994.3  226.52  4997.9  225.92  5016.5  225.08  5016.7  224.58  5020.2  224.58
  5020.5  225.08  5023.6  228.26  5031.4  232.59    5052  234.65  5155.1  234.84
  5224.6  236.12  5265.9  235.55  5312.3  237.37  5353.5  237.46  5412.8  238.63
#Mann= 6 ,-1 , 0
  4696.3     .12       0  4723.8     .07       0  4828.2     .12       0
  4994.3     .07       0  5016.5     .05       0  5020.5     .07       0
Bank Sta=5016.5,5020.5
XS Rating Curve= 0 ,0
Exp/Cntr=0.3,0.1

Type RM Length L Ch R = 1 ,462     ,0,0,0
BEGIN DESCRIPTION:
Stream0807 1.0
END DESCRIPTION:
XS GIS Cut Line= 4
        2457575.     13595275.01      2457658.68      13594981.6
        2457525.       13594725.      2456679.72     13594485.13
#Sta/Elev= 30
  4409.5  233.48    4722   230.2  4857.4   230.6  4863.1  230.37  4868.8  227.53
  4879.6   225.8  4899.7  224.35  4899.9  223.85  4903.7  224.35  4913.7  227.11
  4923.8  225.79  4929.4  229.21  4933.6  228.97  4945.9  225.03  4951.5  229.21
    4968  227.33  4973.6  229.71  4990.1  228.25  4995.7  229.88  5006.5  229.31
  5020.9  231.57  5054.8  233.07    5060  231.92  5093.9  234.68  5232.6  232.98
  5326.2  234.32  5440.5  232.22  5500.3   232.9  5655.7  234.85  5882.6  238.24
#Mann= 6 ,-1 , 0
  4409.5     .12       0  4899.7     .05       0  4903.7     .12       0
  4933.6     .07       0  5500.3      .1       0  5655.7     .07       0
Bank Sta=4899.7,4903.7
XS Rating Curve= 0 ,0
Exp/Cntr=0.3,0.1

Chan Stop Cuts=-1
Use User Specified Reach Order=0
Composite Channel Slope=5