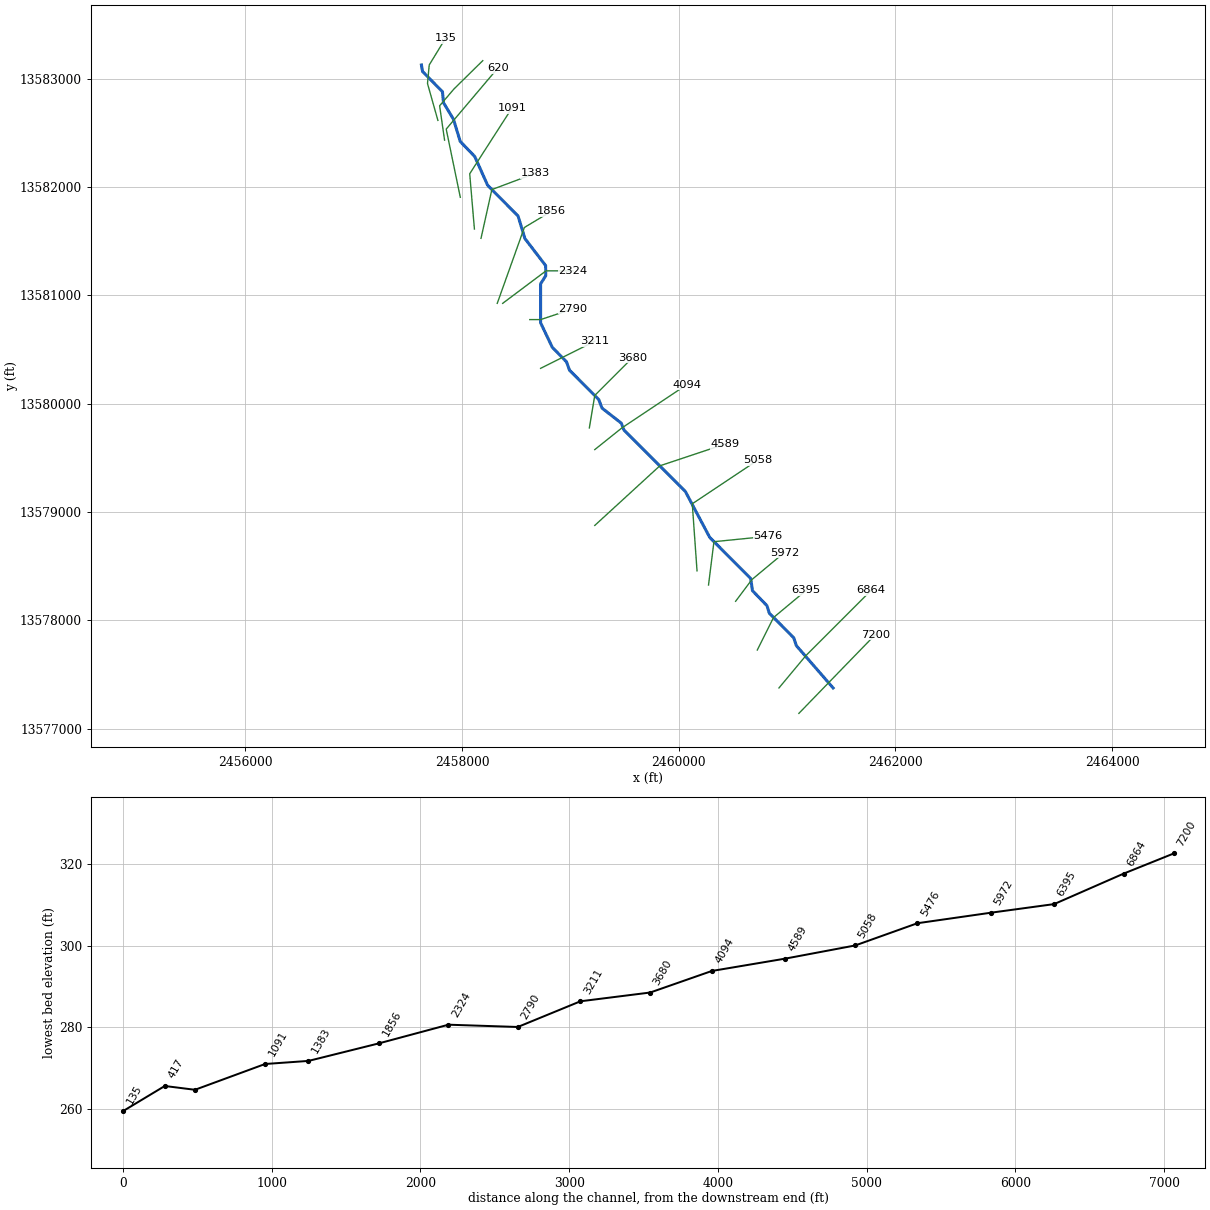
--- Stream0809.prj (project) ---

Proj Title=Stream0809 Base Level Engineering
Current Plan=p01
Default Exp/Contr=0.3,0.1
English Units
Geom File=g01
Flow File=f01
Plan File=p01
BEGIN DESCRIPTION:
Stream0809
END DESCRIPTION:

--- Stream0809.p01 (plan) ---

Plan Title=Multiple Run
Short Identifier=Multiple
Geom File=g01
Flow File=f01
Subcritical Flow
K Sum by GR= 0
Std Step Tol= 0.01
Critical Tol= 0.01
Num of Std Step Trials= 20
Max Error Tol= 0.3
Flow Tol Ratio= 0.001
Split Flow NTrial= 30
Split Flow Tol= 0.02
Split Flow Ratio= 0.02
Log Output Level= 0
Friction Slope Method= 1
Unsteady Friction Slope Method= 2
Unsteady Bridges Friction Slope Method= 1
Parabolic Critical Depth
Global Vel Dist=  1 , 1 , 1
Global Log Level= 0
CheckData=True
Encroach Param= -1, 0, 0, 0
BEGIN DESCRIPTION:
Multiple Run
END DESCRIPTION:

--- Stream0809.f01 (steady flow) ---

Flow Title=Multiple
Number of Profiles=7
Profile Names=10-year,25-year,50-year,1pct_min,100-year,1pct_plu,500-year
River Rch & RM= Stream0809,Reach-1,7200
     374     591     783     505    1007    2009    1645
River Rch & RM= Stream0809,Reach-1,4589
     776    1283    1752    1160    2315    4618    4000
River Rch & RM= Stream0809,Reach-1,2324
     845    1400    1915    1268    2531    5050    4383
Boundary for River Rch & Prof#=Stream0809,Reach-1,1
Up Type=0
Dn Type=3
Dn Slope=0.005
Boundary for River Rch & Prof#=Stream0809,Reach-1,2
Up Type=0
Dn Type=3
Dn Slope=0.005
Boundary for River Rch & Prof#=Stream0809,Reach-1,3
Up Type=0
Dn Type=3
Dn Slope=0.005
Boundary for River Rch & Prof#=Stream0809,Reach-1,4
Up Type=0
Dn Type=3
Dn Slope=0.005
Boundary for River Rch & Prof#=Stream0809,Reach-1,5
Up Type=0
Dn Type=3
Dn Slope=0.005
Boundary for River Rch & Prof#=Stream0809,Reach-1,6
Up Type=0
Dn Type=3
Dn Slope=0.005
Boundary for River Rch & Prof#=Stream0809,Reach-1,7
Up Type=0
Dn Type=3
Dn Slope=0.005

--- Stream0809.g01 (geometry) ---

Geom Title=Existing Conditions

River Reach=Stream0809,Reach-1
Reach XY= 30
      2461425.00     13577375.00      2461085.78     13577765.32
      2461061.37     13577838.21      2460835.78     13578065.32
      2460814.22     13578134.68      2460680.52     13578272.57
      2460664.48     13578384.79      2460285.76     13578765.32
      2460061.37     13579188.21      2459494.86     13579755.08
      2459469.38     13579819.38      2459291.65     13579958.33
      2459261.37     13580038.21      2458991.65     13580308.33
      2458964.22     13580384.68      2458833.14     13580518.94
      2458725.06     13580745.03      2458725.07     13581104.97
      2458772.84     13581180.98      2458771.53     13581273.50
      2458580.54     13581522.58      2458516.86     13581731.06
      2458235.76     13582015.32      2458116.86     13582281.06
      2457983.14     13582418.94      2457921.17     13582623.42
      2457828.83     13582776.59      2457819.48     13582877.43
      2457635.52     13583065.21      2457625.00     13583125.00

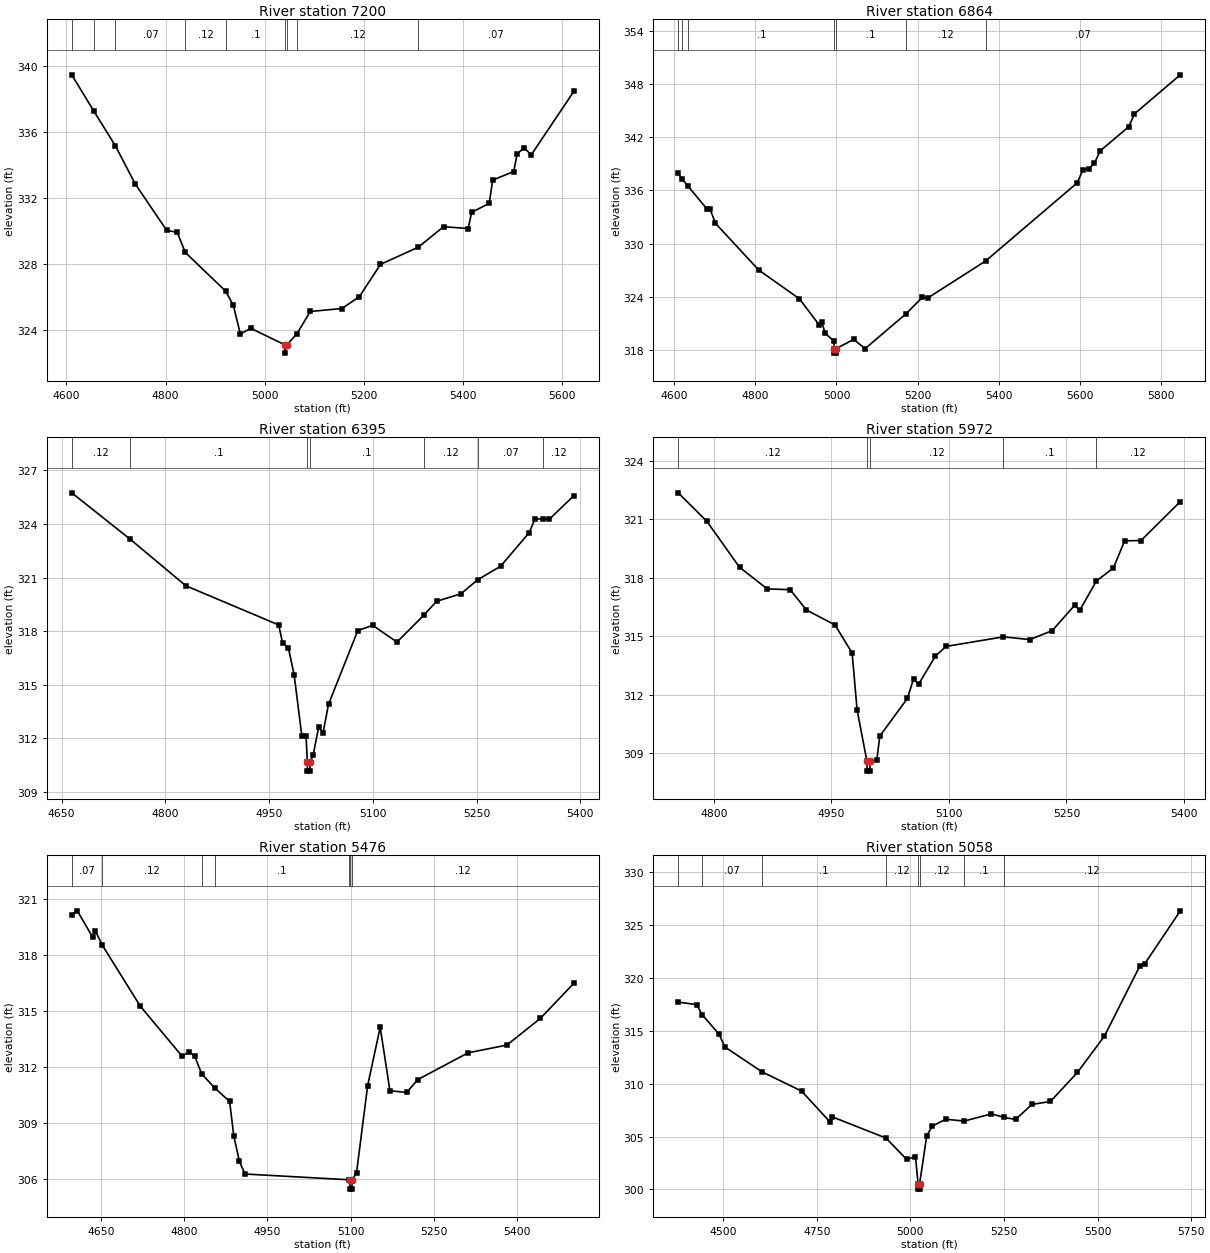
Type RM Length L Ch R = 1,7200,336,336,336
BEGIN DESCRIPTION:
XS7758
END DESCRIPTION:
XS GIS Cut Line= 2
      2461108.88     13577140.39      2461814.18     13577867.39
#Sta/Elev= 30
  4610.8  339.44  4655.4  337.24  4698.7  335.15  4738.6  332.85  4802.2  330.03
  4823.5  329.91  4839.9  328.69  4921.6  326.34  4936.7  325.49  4950.9  323.76
  4972.0  324.10  5040.7  323.10  5041.0  322.60  5044.7  323.10  5064.5  323.75
  5092.1  325.12  5155.9  325.30  5191.1  326.02  5233.6  327.97  5309.8  329.01
  5360.9  330.25  5410.5  330.14  5417.5  331.12  5453.0  331.66  5459.9  333.07
  5502.4  333.59  5509.3  334.66  5523.5  335.03  5537.6  334.59  5623.7  338.44
#Mann=9,-1,0
  4610.8    0.07       0  4655.4    0.12       0  4698.7    0.07       0
  4839.9    0.12       0  4921.6     0.1       0  5040.7    0.05       0
  5044.7     0.1       0  5064.5    0.12       0  5309.8    0.07       0
Bank Sta=5040.7,5044.7
Exp/Cntr=0.3,0.1

Type RM Length L Ch R = 1,6864,469,469,469
BEGIN DESCRIPTION:
Stream0809 13.0
END DESCRIPTION:
XS GIS Cut Line= 3
      2460924.99     13577374.99      2461175.00     13577675.00
      2461775.03     13578275.03
#Sta/Elev= 30
  4609.5  337.93  4619.4  337.27  4634.3  336.45  4680.5  333.91  4687.6  333.96
  4701.3  332.30  4808.0  327.04  4908.3  323.80  4957.7  320.83  4964.2  321.13
  4972.0  319.90  4992.9  319.06  4994.8  318.17  4995.0  317.67  4998.5  317.67
  4998.8  318.17  5042.5  319.21  5070.7  318.18  5172.2  322.12  5212.2  323.97
  5226.3  323.91  5368.3  328.06  5594.0  336.85  5608.1  338.31  5622.3  338.43
  5636.4  339.05  5650.6  340.45  5721.3  343.18  5735.4  344.63  5848.6  349.03
#Mann=7,-1,0
  4609.5    0.12       0  4619.4    0.07       0  4634.3     0.1       0
  4994.8    0.05       0  4998.8     0.1       0  5172.2    0.12       0
  5368.3    0.07       0
Bank Sta=4994.8,4998.8
Exp/Cntr=0.3,0.1

Type RM Length L Ch R = 1,6395,423,423,423
BEGIN DESCRIPTION:
Stream0809 12.0
END DESCRIPTION:
XS GIS Cut Line= 3
      2460724.99     13577724.98      2460875.00     13578025.00
      2461174.97     13578274.97
#Sta/Elev= 30
  4664.8  325.74  4749.7  323.13  4829.7  320.54  4963.9  318.35  4969.5  317.36
  4977.9  317.08  4986.3  315.56  4997.4  312.15  5003.5  312.15  5005.4  310.67
  5005.6  310.17  5009.1  310.17  5009.4  310.67  5013.9  311.09  5021.7  312.62
  5028.2  312.33  5036.0  313.91  5078.3  318.03  5099.8  318.33  5135.0  317.39
  5173.7  318.89  5192.2  319.67  5227.4  320.09  5251.8  320.88  5284.7  321.63
  5326.3  323.52  5334.1  324.25  5346.1  324.30  5354.9  324.25  5390.7  325.58
#Mann=7,-1,0
  4664.8    0.12       0  4749.7     0.1       0  5005.4    0.05       0
  5009.4     0.1       0  5173.7    0.12       0  5251.8    0.07       0
  5346.1    0.12       0
Bank Sta=5005.4,5009.4
Exp/Cntr=0.3,0.1

Type RM Length L Ch R = 1,5972,496,496,496
BEGIN DESCRIPTION:
Stream0809 11.0
END DESCRIPTION:
XS GIS Cut Line= 3
      2460524.97     13578174.96      2460675.00     13578375.00
      2460975.03     13578625.02
#Sta/Elev= 30
  4754.7  322.35  4791.2  320.89  4832.9  318.53  4868.3  317.42  4897.5  317.38
  4918.3  316.34  4954.7  315.57  4976.6  314.13  4982.9  311.21  4995.5  308.57
  4995.7  308.07  4999.2  308.07  4999.5  308.57  5008.0  308.63  5011.9  309.87
  5047.1  311.80  5054.9  312.80  5061.4  312.53  5082.9  313.98  5096.5  314.47
  5169.7  314.96  5203.3  314.82  5231.9  315.28  5260.5  316.58  5267.0  316.32
  5288.1  317.82  5310.0  318.50  5324.3  319.89  5345.1  319.90  5395.3  321.90
#Mann=5,-1,0
  4754.7    0.12       0  4995.5    0.05       0  4999.5    0.12       0
  5169.7     0.1       0  5288.1    0.12       0
Bank Sta=4995.5,4999.5
Exp/Cntr=0.3,0.1

Type RM Length L Ch R = 1,5476,418,418,418
BEGIN DESCRIPTION:
Stream0809 10.0
END DESCRIPTION:
XS GIS Cut Line= 3
      2460275.00     13578325.04      2460325.00     13578725.00
      2460825.03     13578775.00
#Sta/Elev= 30
  4597.2  320.19  4607.2  320.39  4635.0  318.97  4640.0  319.30  4652.3  318.55
  4720.6  315.29  4796.2  312.60  4808.8  312.84  4818.9  312.61  4831.5  311.66
  4855.3  310.89  4881.9  310.18  4889.4  308.34  4899.5  306.97  4909.6  306.29
  5097.8  305.98  5098.8  305.98  5099.0  305.48  5102.5  305.48  5102.8  305.98
  5110.8  306.35  5130.9  311.03  5153.5  314.15  5171.1  310.75  5201.3  310.66
  5221.4  311.35  5311.8  312.78  5382.2  313.20  5442.5  314.63  5502.8  316.51
#Mann=7,-1,0
  4597.2    0.07       0  4652.3    0.12       0  4831.5    0.07       0
  4855.3     0.1       0  5097.8    0.12       0  5098.8    0.05       0
  5102.8    0.12       0
Bank Sta=5098.8,5102.8
Exp/Cntr=0.3,0.1

Type RM Length L Ch R = 1,5058,469,469,469
BEGIN DESCRIPTION:
Stream0809 9.0
END DESCRIPTION:
XS GIS Cut Line= 3
      2460168.84     13578456.23      2460125.00     13579075.00
      2460724.98     13579474.98
#Sta/Elev= 30
  4379.7  317.69  4428.6  317.47  4443.9  316.50  4488.7  314.67  4504.3  313.46
  4603.5  311.11  4709.3  309.29  4786.1  306.34  4791.1  306.86  4934.9  304.85
  4990.0  302.84  5013.5  303.10  5020.6  300.53  5020.8  300.03  5024.3  300.03
  5024.6  300.53  5043.6  305.07  5058.6  305.99  5094.7  306.63  5143.9  306.46
  5216.4  307.14  5250.1  306.81  5281.0  306.61  5324.5  308.03  5374.1  308.31
  5446.2  311.05  5518.3  314.48  5613.0  321.11  5626.5  321.34  5721.1  326.32
#Mann=8,-1,0
  4379.7    0.12       0  4443.9    0.07       0  4603.5     0.1       0
  4934.9    0.12       0  5020.6    0.05       0  5024.6    0.12       0
  5143.9     0.1       0  5250.1    0.12       0
Bank Sta=5020.6,5024.6
Exp/Cntr=0.3,0.1

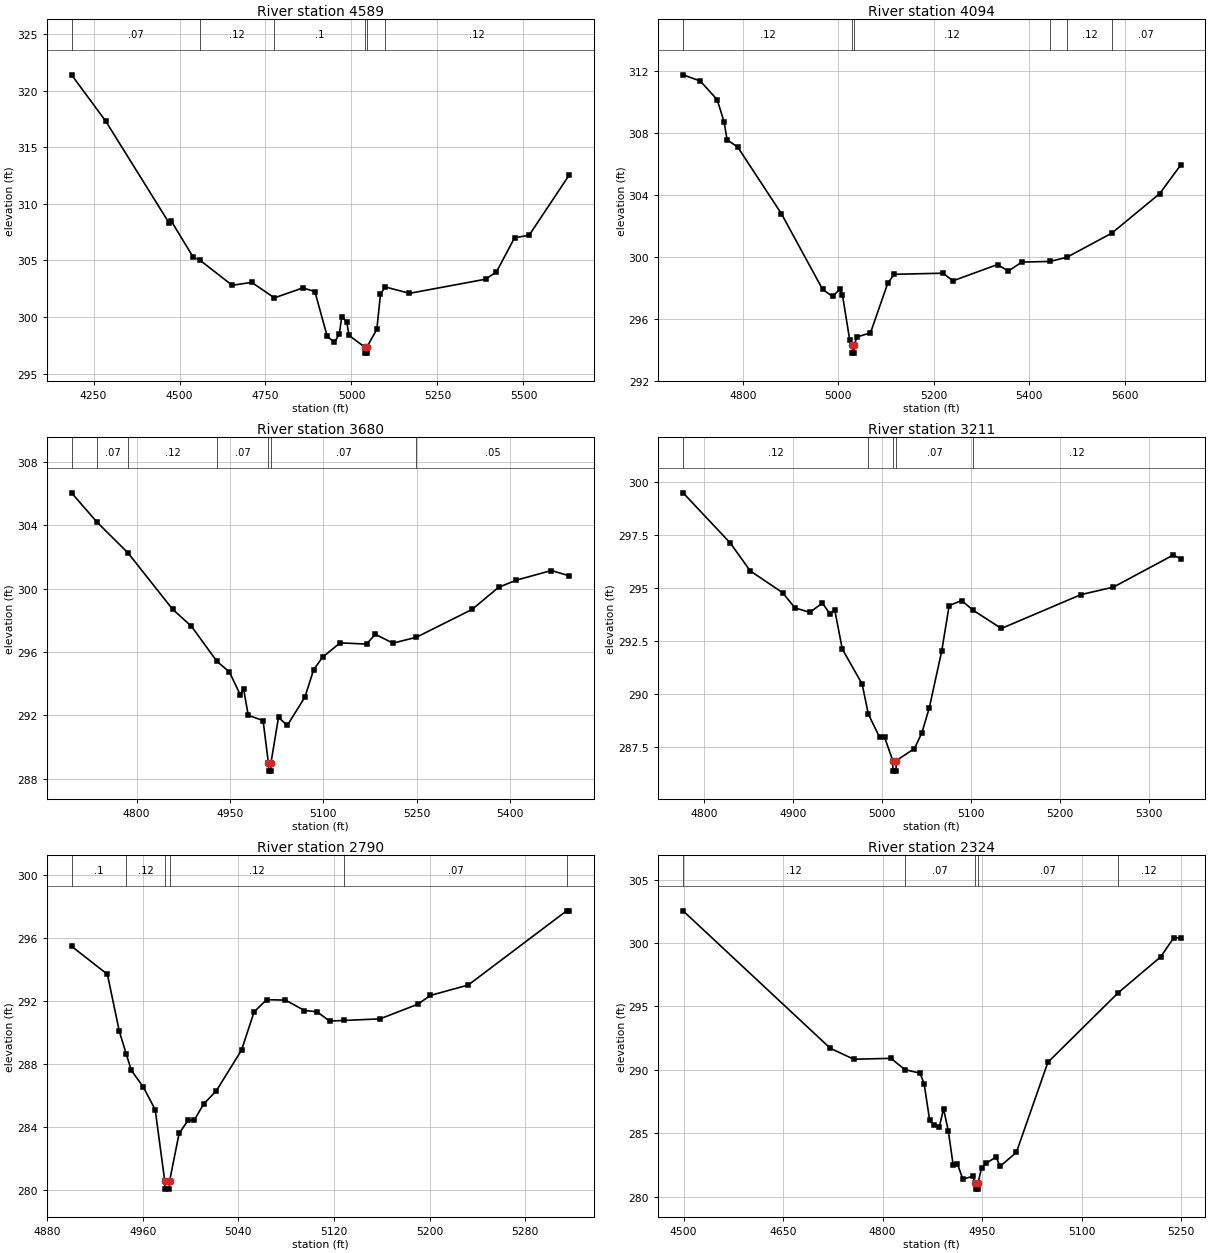
Type RM Length L Ch R = 1,4589,495,495,495
BEGIN DESCRIPTION:
Stream0809 8.0
END DESCRIPTION:
XS GIS Cut Line= 3
      2459225.03     13578875.03      2459825.00     13579425.00
      2460425.04     13579625.01
#Sta/Elev= 30
  4186.1  321.39  4285.0  317.32  4469.4  308.32  4476.2  308.47  4539.7  305.29
  4558.5  305.04  4653.2  302.80  4709.9  303.06  4775.9  301.69  4858.5  302.57
  4893.6  302.25  4929.4  298.30  4950.4  297.75  4964.5  298.49  4971.9  300.04
  4986.1  299.59  4992.9  298.37  5040.2  297.31  5040.4  296.81  5043.9  296.81
  5044.2  297.31  5073.8  298.92  5084.3  302.00  5097.6  302.66  5168.7  302.09
  5390.0  303.34  5421.6  303.99  5474.3  307.00  5516.5  307.22  5632.5  312.51
#Mann=6,-1,0
  4186.1    0.07       0  4558.5    0.12       0  4775.9     0.1       0
  5040.2    0.05       0  5044.2     0.1       0  5097.6    0.12       0
Bank Sta=5040.2,5044.2
Exp/Cntr=0.3,0.1

Type RM Length L Ch R = 1,4094,414,414,414
BEGIN DESCRIPTION:
Stream0809 7.0
END DESCRIPTION:
XS GIS Cut Line= 3
      2459224.98     13579574.99      2459475.00     13579775.00
      2460075.01     13580175.01
#Sta/Elev= 30
  4675.1  311.74  4711.1  311.34  4746.4  310.14  4760.8  308.72  4767.2  307.55
  4789.6  307.07  4880.8  302.78  4967.3  297.88  4988.1  297.43  5002.8  297.89
  5008.8  297.52  5023.8  294.64  5029.3  294.27  5029.6  293.77  5033.1  293.77
  5033.3  294.27  5038.8  294.81  5067.4  295.08  5103.4  298.27  5117.0  298.86
  5219.1  298.93  5240.2  298.44  5333.3  299.49  5355.8  299.07  5384.4  299.65
  5443.3  299.69  5478.6  299.96  5572.7  301.52  5672.8  304.07  5716.4  305.90
#Mann=6,-1,0
  4675.1    0.12       0  5029.3    0.05       0  5033.3    0.12       0
  5443.3    0.07       0  5478.6    0.12       0  5572.7    0.07       0
Bank Sta=5029.3,5033.3
Exp/Cntr=0.3,0.1

Type RM Length L Ch R = 1,3680,469,469,469
BEGIN DESCRIPTION:
Stream0809 6.0
END DESCRIPTION:
XS GIS Cut Line= 3
      2459174.99     13579774.95      2459225.00     13580075.00
      2459575.03     13580425.03
#Sta/Elev= 30
  4695.6  306.04  4736.3  304.20  4786.5  302.24  4857.9  298.70  4888.3  297.62
  4929.2  295.41  4949.1  294.75  4966.8  293.29  4971.9  293.70  4979.5  292.01
  5003.3  291.68  5011.9  288.99  5012.2  288.49  5015.7  288.49  5015.9  288.99
  5028.1  291.88  5042.2  291.37  5070.5  293.16  5084.6  294.89  5098.8  295.67
  5127.1  296.58  5169.5  296.50  5183.6  297.12  5211.9  296.56  5249.5  296.93
  5339.2  298.69  5381.6  300.08  5409.9  300.53  5466.5  301.14  5494.8  300.81
#Mann=7,-1,0
  4695.6    0.12       0  4736.3    0.07       0  4786.5    0.12       0
  4929.2    0.07       0  5011.9    0.05       0  5015.9    0.07       0
  5249.5    0.05       0
Bank Sta=5011.9,5015.9
Exp/Cntr=0.3,0.1

Type RM Length L Ch R = 1,3211,421,421,421
BEGIN DESCRIPTION:
Stream0809 5.0
END DESCRIPTION:
XS GIS Cut Line= 3
      2458725.02     13580325.01      2458925.00     13580425.00
      2459225.01     13580575.00
#Sta/Elev= 30
  4776.2  299.47  4829.3  297.10  4851.6  295.79  4888.0  294.76  4902.0  294.04
  4918.7  293.83  4932.7  294.27  4941.1  293.77  4946.7  293.93  4955.1  292.10
  4977.4  290.45  4984.4  289.03  4997.0  287.94  5002.6  287.94  5011.8  286.84
  5012.0  286.34  5015.5  286.34  5015.8  286.84  5036.1  287.40  5044.5  288.14
  5052.9  289.33  5066.9  292.02  5075.2  294.15  5089.2  294.39  5101.8  293.94
  5133.9  293.07  5223.4  294.67  5259.7  295.02  5326.8  296.53  5335.2  296.37
#Mann=5,-1,0
  4776.2    0.12       0  4984.4    0.07       0  5011.8    0.05       0
  5015.8    0.07       0  5101.8    0.12       0
Bank Sta=5011.8,5015.8
Exp/Cntr=0.3,0.1

Type RM Length L Ch R = 1,2790,466,466,466
BEGIN DESCRIPTION:
Stream0809 4.0
END DESCRIPTION:
XS GIS Cut Line= 3
      2458625.01     13580775.00      2458725.00     13580775.00
      2459024.98     13580874.99
#Sta/Elev= 30
  4900.4  295.46  4930.4  293.68  4940.4  290.05  4946.1  288.64  4950.4  287.58
  4960.4  286.53  4970.4  285.08  4978.4  280.54  4978.6  280.04  4982.1  280.04
  4982.4  280.54  4990.4  283.58  4997.9  284.41  5003.0  284.41  5010.9  285.44
  5021.5  286.28  5042.6  288.86  5053.1  291.29  5063.6  292.07  5079.4  292.04
  5095.3  291.38  5105.8  291.30  5116.3  290.71  5128.4  290.75  5158.5  290.85
  5190.1  291.78  5200.7  292.34  5232.3  293.00  5314.6  297.71  5316.6  297.71
#Mann=6,-1,0
  4900.4     0.1       0  4946.1    0.12       0  4978.4    0.05       0
  4982.4    0.12       0  5128.4    0.07       0  5314.6    0.12       0
Bank Sta=4978.4,4982.4
Exp/Cntr=0.3,0.1

Type RM Length L Ch R = 1,2324,468,468,468
BEGIN DESCRIPTION:
Stream0809 3.0
END DESCRIPTION:
XS GIS Cut Line= 3
      2458375.02     13580925.02      2458775.00     13581225.00
      2459025.03     13581225.00
#Sta/Elev= 30
  4499.2  302.54  4721.0  291.71  4756.5  290.84  4812.7  290.91  4833.6  290.02
  4856.5  289.74  4862.7  288.89  4871.0  286.02  4877.3  285.62  4885.6  285.53
  4891.9  286.93  4899.2  285.15  4906.5  282.47  4912.7  282.61  4921.0  281.38
  4935.6  281.61  4939.9  281.10  4940.1  280.60  4943.6  280.60  4943.9  281.10
  4949.2  282.26  4956.5  282.65  4971.0  283.13  4977.3  282.40  5001.7  283.50
  5049.2  290.60  5155.2  296.08  5219.2  298.91  5239.2  300.43  5249.2  300.39
#Mann=5,-1,0
  4499.2    0.12       0  4833.6    0.07       0  4939.9    0.05       0
  4943.9    0.07       0  5155.2    0.12       0
Bank Sta=4939.9,4943.9
Exp/Cntr=0.3,0.1

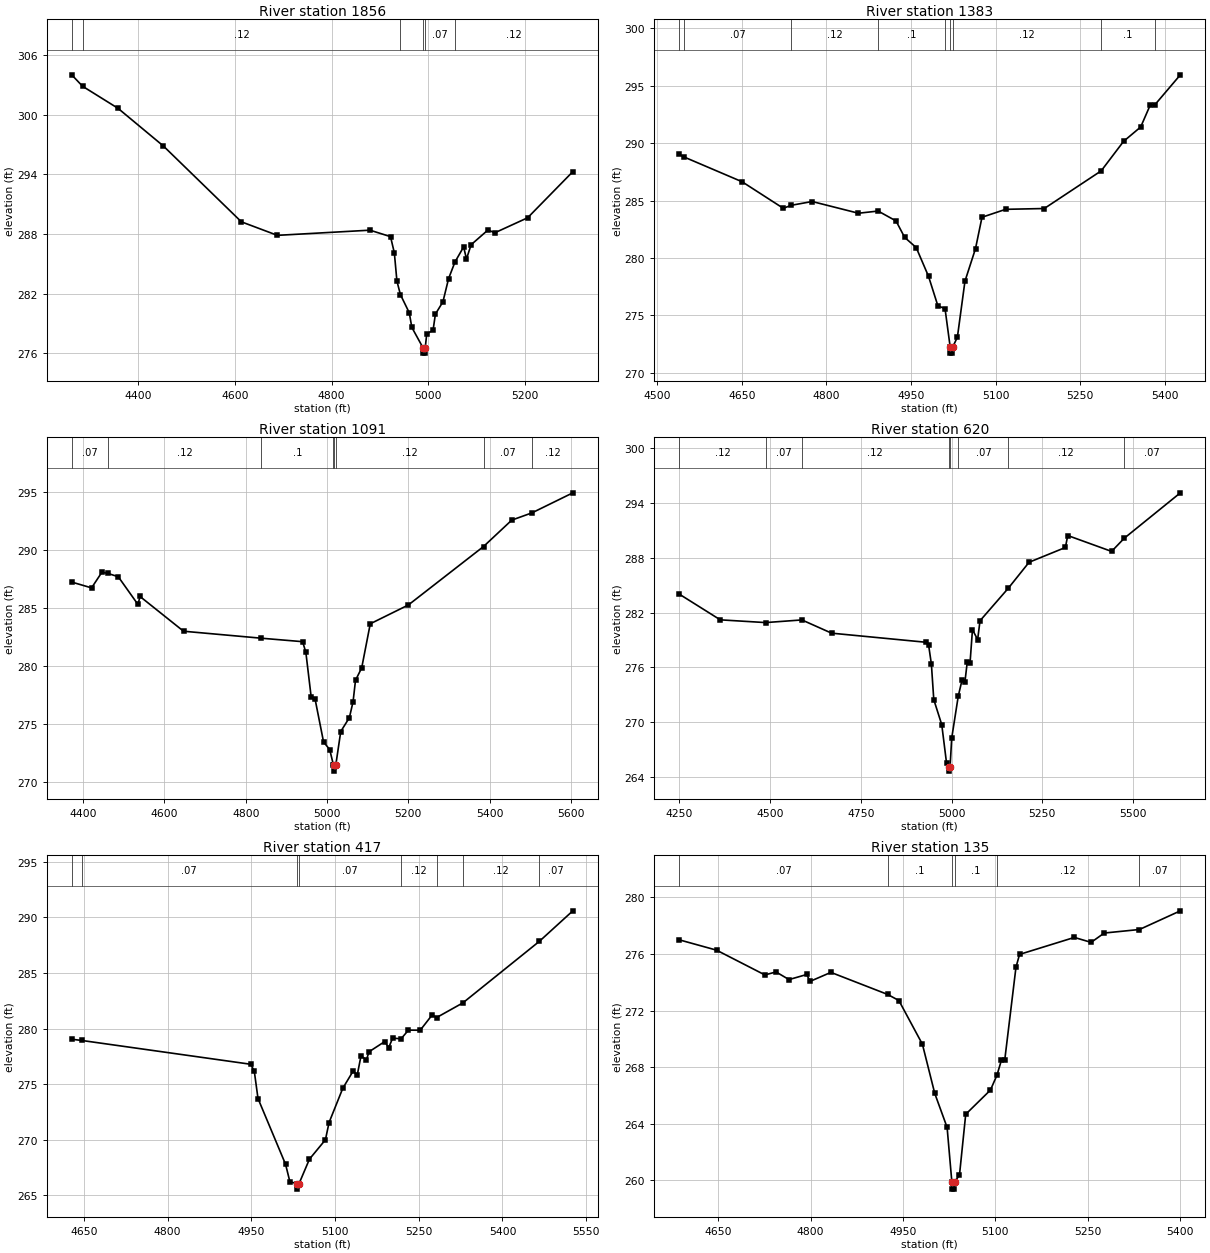
Type RM Length L Ch R = 1,1856,473,473,473
BEGIN DESCRIPTION:
Stream0809 2.0
END DESCRIPTION:
XS GIS Cut Line= 3
      2458325.00     13580925.00      2458575.00     13581625.00
      2458825.04     13581775.02
#Sta/Elev= 30
  4263.4  304.02  4285.8  302.87  4359.0  300.65  4452.9  296.85  4613.8  289.23
  4688.1  287.87  4879.3  288.39  4921.8  287.74  4929.7  286.10  4935.0  283.27
  4942.2  281.91  4960.5  280.08  4965.8  278.61  4989.3  276.52  4989.5  276.02
  4993.1  276.02  4993.4  276.52  4996.6  277.97  5009.6  278.31  5014.5  279.95
  5030.0  281.18  5041.7  283.52  5055.0  285.20  5072.8  286.71  5078.6  285.49
  5088.3  286.93  5123.3  288.42  5136.9  288.12  5205.0  289.64  5298.3  294.28
#Mann=6,-1,0
  4263.4    0.07       0  4285.8    0.12       0  4942.2    0.07       0
  4989.3    0.05       0  4993.4    0.07       0  5055.0    0.12       0
Bank Sta=4989.3,4993.4
Exp/Cntr=0.3,0.1

Type RM Length L Ch R = 1,1383,292,292,292
BEGIN DESCRIPTION:
Stream0809 1.0
END DESCRIPTION:
XS GIS Cut Line= 3
      2458175.00     13581524.99      2458275.00     13581975.00
      2458675.01     13582125.00
#Sta/Elev= 30
  4539.3  289.02  4548.1  288.79  4650.7  286.64  4723.7  284.33  4737.8  284.59
  4774.9  284.92  4856.9  283.90  4891.8  284.09  4923.5  283.23  4938.8  281.80
  4959.3  280.91  4981.1  278.41  4997.7  275.84  5010.4  275.59  5019.6  272.22
  5019.8  271.72  5023.4  271.72  5023.7  272.22  5032.3  273.11  5045.7  277.98
  5064.4  280.82  5075.9  283.55  5117.8  284.24  5186.3  284.31  5287.2  287.59
  5326.9  290.16  5357.2  291.41  5374.1  293.32  5382.3  293.34  5427.5  295.95
#Mann=9,-1,0
  4539.3    0.12       0  4548.1    0.07       0  4737.8    0.12       0
  4891.8     0.1       0  5010.4    0.12       0  5019.6    0.05       0
  5023.7    0.12       0  5287.2     0.1       0  5382.3    0.12       0
Bank Sta=5019.6,5023.7
Exp/Cntr=0.3,0.1

Type RM Length L Ch R = 1,1091,471,471,471
BEGIN DESCRIPTION:
XS7757
END DESCRIPTION:
XS GIS Cut Line= 3
      2458114.10     13581610.92      2458070.70     13582120.88
      2458460.64     13582727.45
#Sta/Elev= 30
  4371.8  287.23  4420.6  286.73  4446.1  288.08  4461.1  287.97  4486.3  287.69
  4534.8  285.30  4539.8  285.99  4646.9  283.00  4837.8  282.40  4939.9  282.10
  4947.9  281.17  4961.0  277.32  4970.3  277.20  4991.4  273.47  5006.6  272.81
  5015.6  271.50  5017.1  271.46  5017.4  270.96  5021.4  271.46  5033.7  274.37
  5054.9  275.56  5064.0  276.93  5070.0  278.78  5085.2  279.84  5106.3  283.64
  5200.1  285.26  5385.0  290.29  5454.4  292.56  5504.4  293.19  5604.7  294.91
#Mann=8,-1,0
  4371.8    0.07       0  4461.1    0.12       0  4837.8     0.1       0
  5015.6    0.12       0  5017.1    0.05       0  5021.4    0.12       0
  5385.0    0.07       0  5504.4    0.12       0
Bank Sta=5017.1,5021.4
Exp/Cntr=0.3,0.1

Type RM Length L Ch R = 1,620,203,203,203
BEGIN DESCRIPTION:
XS7756
END DESCRIPTION:
XS GIS Cut Line= 3
      2457983.89     13581903.89      2457853.69     13582533.20
      2458330.56     13583096.78
#Sta/Elev= 30
  4249.4  284.04  4362.5  281.22  4487.3  280.92  4587.4  281.21  4669.2  279.76
  4930.0  278.76  4936.5  278.47  4944.2  276.37  4950.8  272.48  4972.8  269.73
  4986.1  265.48  4991.5  265.14  4991.8  264.64  4995.8  265.14  5000.2  268.25
  5018.3  272.87  5028.8  274.64  5036.5  274.37  5043.1  276.61  5050.8  276.53
  5057.4  280.14  5071.7  279.06  5078.2  281.12  5156.7  284.71  5213.4  287.53
  5313.4  289.15  5320.0  290.46  5440.8  288.72  5475.6  290.16  5630.3  295.14
#Mann=8,-1,0
  4249.4    0.12       0  4487.3    0.07       0  4587.4    0.12       0
  4991.5    0.05       0  4995.8    0.12       0  5018.3    0.07       0
  5156.7    0.12       0  5475.6    0.07       0
Bank Sta=4991.5,4995.8
Exp/Cntr=0.3,0.1

Type RM Length L Ch R = 1,417,282,282,282
BEGIN DESCRIPTION:
H21094
END DESCRIPTION:
XS GIS Cut Line= 4
      2457838.66     13582431.03      2457792.99     13582748.48
      2457925.46     13582903.79      2458191.37     13583165.15
#Sta/Elev= 30
  4628.3  279.05  4646.4  278.94  4949.0  276.80  4955.4  276.16  4962.0  273.72
  5011.4  267.80  5019.1  266.24  5031.2  266.07  5031.5  265.57  5035.6  266.07
  5054.2  268.27  5082.8  270.01  5089.3  271.56  5113.9  274.64  5132.2  276.17
  5139.9  275.86  5146.5  277.55  5156.3  277.20  5160.8  277.92  5189.0  278.84
  5196.1  278.29  5203.2  279.15  5218.3  279.09  5231.5  279.87  5252.6  279.86
  5273.9  281.23  5281.9  281.00  5329.0  282.32  5465.9  287.85  5526.0  290.60
#Mann=8,-1,0
  4628.3    0.12       0  4646.4    0.07       0  5031.2    0.05       0
  5035.6    0.07       0  5218.3    0.12       0  5281.9    0.07       0
  5329.0    0.12       0  5465.9    0.07       0
Bank Sta=5031.2,5035.6
Exp/Cntr=0.3,0.1

Type RM Length L Ch R = 1,135,0,0,0
BEGIN DESCRIPTION:
H21093
END DESCRIPTION:
XS GIS Cut Line= 4
      2457777.01     13582613.69      2457681.07     13582954.04
      2457697.06     13583125.35      2457847.20     13583371.03
#Sta/Elev= 30
  4586.9  277.00  4647.5  276.27  4725.9  274.52  4744.1  274.73  4765.1  274.19
  4793.9  274.55  4799.1  274.06  4833.1  274.70  4925.3  273.14  4943.5  272.71
  4981.7  269.62  5001.7  266.15  5021.8  263.74  5029.5  259.88  5029.8  259.38
  5033.6  259.38  5033.9  259.88  5041.9  260.38  5052.0  264.67  5092.1  266.38
  5102.7  267.43  5109.9  268.48  5115.3  268.48  5133.6  275.06  5139.4  275.97
  5228.4  277.17  5255.6  276.82  5276.9  277.48  5334.1  277.73  5400.5  279.05
#Mann=6,-1,0
  4586.9    0.07       0  4925.3     0.1       0  5029.5    0.05       0
  5033.9     0.1       0  5102.7    0.12       0  5334.1    0.07       0
Bank Sta=5029.5,5033.9
Exp/Cntr=0.3,0.1

Chan Stop Cuts=-1