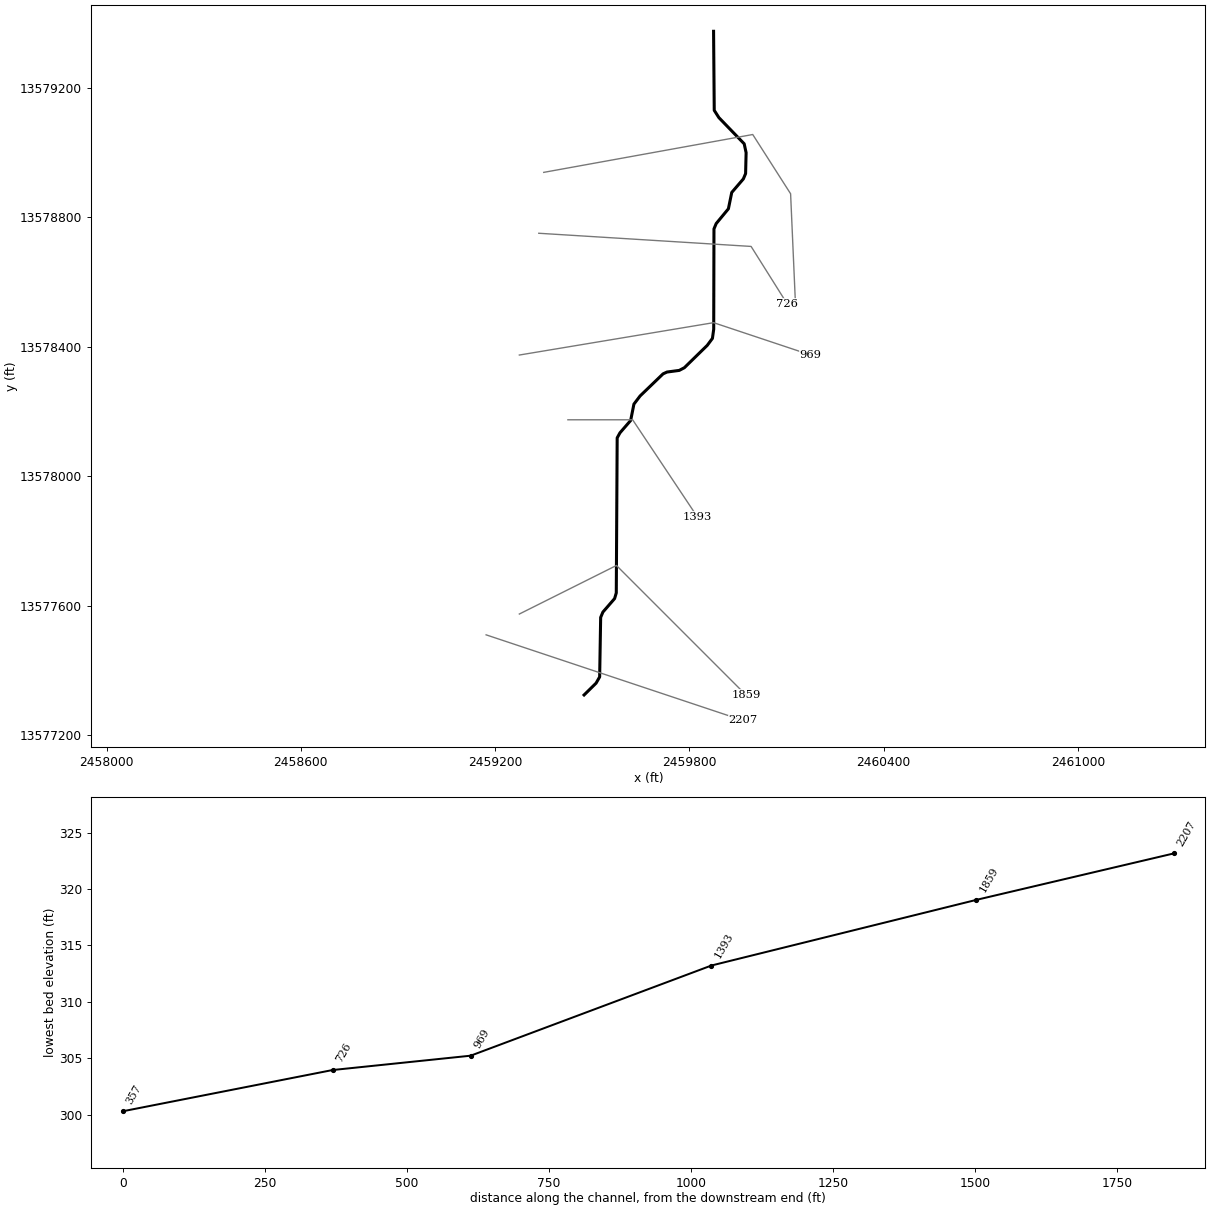
--- Stream0810.prj (project) ---

Proj Title=Stream0810 Base Level Engineering
Current Plan=p01
Default Exp/Contr=0.3,0.1
English Units
Geom File=g01
Flow File=f01
Plan File=p01
BEGIN DESCRIPTION:
Stream0810
END DESCRIPTION:

--- Stream0810.p01 (plan) ---

Plan Title=Multiple Run
Short Identifier=Multiple
Geom File=g01
Flow File=f01
Subcritical Flow
K Sum by GR= 0
Std Step Tol= 0.01
Critical Tol= 0.01
Num of Std Step Trials= 20
Max Error Tol= 0.3
Flow Tol Ratio= 0.001
Split Flow NTrial= 30
Split Flow Tol= 0.02
Split Flow Ratio= 0.02
Log Output Level= 0
Friction Slope Method= 1
Unsteady Friction Slope Method= 2
Unsteady Bridges Friction Slope Method= 1
Parabolic Critical Depth
Global Vel Dist=  1 , 1 , 1
Global Log Level= 0
CheckData=True
Encroach Param= -1, 0, 0, 0
BEGIN DESCRIPTION:
Multiple Run
END DESCRIPTION:

--- Stream0810.f01 (steady flow) ---

Flow Title=Multiple
Number of Profiles=7
Profile Names=10-year,25-year,50-year,1pct_min,100-year,1pct_plu,500-year
River Rch & RM= Stream0810,Reach-1,2207
     344     541     714     459     916    1828    1488
Boundary for River Rch & Prof#=Stream0810,Reach-1,1
Up Type=0
Dn Type=3
Dn Slope=0.005
Boundary for River Rch & Prof#=Stream0810,Reach-1,2
Up Type=0
Dn Type=3
Dn Slope=0.005
Boundary for River Rch & Prof#=Stream0810,Reach-1,3
Up Type=0
Dn Type=3
Dn Slope=0.005
Boundary for River Rch & Prof#=Stream0810,Reach-1,4
Up Type=0
Dn Type=3
Dn Slope=0.005
Boundary for River Rch & Prof#=Stream0810,Reach-1,5
Up Type=0
Dn Type=3
Dn Slope=0.005
Boundary for River Rch & Prof#=Stream0810,Reach-1,6
Up Type=0
Dn Type=3
Dn Slope=0.005
Boundary for River Rch & Prof#=Stream0810,Reach-1,7
Up Type=0
Dn Type=3
Dn Slope=0.005

--- Stream0810.g01 (geometry) ---

Geom Title=Existing Conditions

River Reach=Stream0810,Reach-1
Reach XY= 30
      2459475.00     13577325.00      2459512.08     13577361.50
      2459523.11     13577380.78      2459526.22     13577564.49
      2459533.14     13577581.06      2459569.25     13577622.67
      2459574.48     13577640.22      2459577.24     13578119.07
      2459585.79     13578134.67      2459618.86     13578172.83
      2459628.94     13578223.38      2459647.99     13578248.52
      2459718.94     13578316.85      2459731.04     13578322.47
      2459768.96     13578327.53      2459784.70     13578335.77
      2459855.41     13578404.80      2459871.47     13578426.45
      2459875.43     13578454.82      2459876.20     13578764.50
      2459883.09     13578781.08      2459920.81     13578826.74
      2459931.12     13578877.18      2459966.96     13578918.95
      2459973.92     13578935.55      2459975.49     13579000.04
      2459969.59     13579027.42      2459891.47     13579108.25
      2459877.06     13579130.86      2459875.00     13579375.00

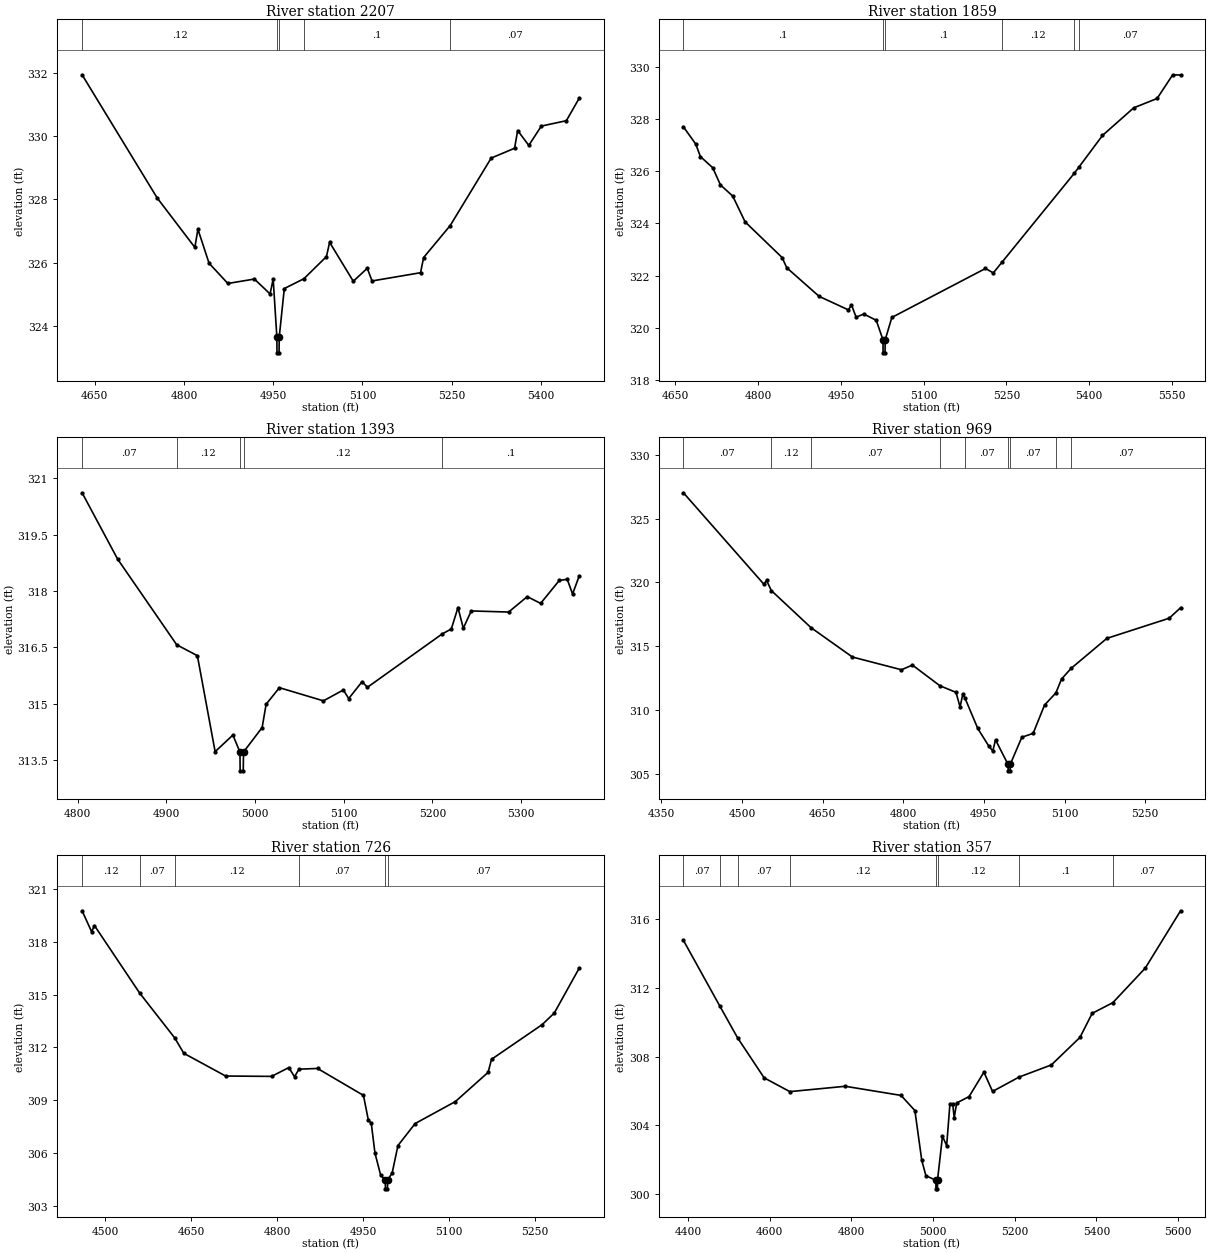
Type RM Length L Ch R = 1,2207,348,348,348
BEGIN DESCRIPTION:
XS7761
END DESCRIPTION:
XS GIS Cut Line= 2
      2459172.44     13577510.71      2459965.45     13577246.38
#Sta/Elev= 30
  4628.5  331.93  4754.8  328.04  4818.1  326.48  4823.3  327.05  4842.0  325.98
  4873.6  325.34  4918.2  325.48  4944.6  325.01  4949.8  325.48  4956.0  323.65
  4956.2  323.15  4959.7  323.15  4960.0  323.65  4968.5  325.18  5001.5  325.49
  5039.4  326.19  5044.7  326.64  5084.5  325.41  5108.0  325.82  5116.1  325.42
  5197.6  325.68  5202.8  326.16  5247.5  327.17  5316.4  329.30  5355.7  329.61
  5360.9  330.17  5379.6  329.70  5400.7  330.31  5442.8  330.48  5464.4  331.19
#Mann=5,-1,0
  4628.5    0.12       0  4956.0    0.05       0  4960.0    0.12       0
  5001.5     0.1       0  5247.5    0.07       0
Bank Sta=4956,4960
Exp/Cntr=0.3,0.1

Type RM Length L Ch R = 1,1859,466,466,466
BEGIN DESCRIPTION:
Stream0810 3.0
END DESCRIPTION:
XS GIS Cut Line= 3
      2459275.03     13577575.01      2459575.00     13577725.00
      2459975.03     13577324.97
#Sta/Elev= 30
  4664.5  327.71  4686.8  327.05  4695.2  326.57  4717.6  326.14  4731.6  325.48
  4753.9  325.05  4776.3  324.06  4843.4  322.69  4851.7  322.30  4910.4  321.20
  4963.5  320.68  4969.1  320.87  4977.5  320.40  4991.5  320.52  5014.0  320.28
  5026.2  319.53  5026.4  319.03  5029.9  319.03  5030.2  319.53  5042.3  320.39
  5212.0  322.27  5226.2  322.10  5241.9  322.51  5373.1  325.93  5380.9  326.15
  5424.1  327.38  5480.7  328.44  5523.1  328.80  5551.4  329.71  5565.6  329.70
#Mann=6,-1,0
  4664.5     0.1       0  5026.2    0.05       0  5030.2     0.1       0
  5241.9    0.12       0  5373.1     0.1       0  5380.9    0.07       0
Bank Sta=5026.2,5030.2
Exp/Cntr=0.3,0.1

Type RM Length L Ch R = 1,1393,424,424,424
BEGIN DESCRIPTION:
Stream0810 2.0
END DESCRIPTION:
XS GIS Cut Line= 3
      2459425.02     13578175.00      2459625.00     13578175.00
      2459824.98     13577875.03
#Sta/Elev= 30
  4805.1  320.61  4845.1  318.85  4911.8  316.57  4935.1  316.28  4955.1  313.73
  4975.1  314.17  4983.1  313.72  4983.3  313.22  4986.8  313.22  4987.1  313.72
  5008.1  314.37  5012.6  314.99  5027.6  315.43  5077.2  315.08  5099.7  315.37
  5105.7  315.14  5120.8  315.59  5126.8  315.44  5211.2  316.86  5221.4  316.99
  5228.9  317.56  5234.9  317.01  5243.9  317.47  5286.0  317.44  5307.0  317.85
  5322.1  317.67  5343.1  318.28  5352.1  318.31  5358.1  317.92  5365.6  318.40
#Mann=5,-1,0
  4805.1    0.07       0  4911.8    0.12       0  4983.1    0.05       0
  4987.1    0.12       0  5211.2     0.1       0
Bank Sta=4983.1,4987.1
Exp/Cntr=0.3,0.1

Type RM Length L Ch R = 1,969,243,243,243
BEGIN DESCRIPTION:
Stream0810 1.0
END DESCRIPTION:
XS GIS Cut Line= 3
      2459275.03     13578375.01      2459875.00     13578475.00
      2460175.03     13578374.99
#Sta/Elev= 30
  4391.3  327.02  4540.8  319.86  4545.9  320.15  4554.7  319.36  4628.3  316.46
  4705.5  314.15  4796.8  313.15  4817.1  313.52  4868.2  311.90  4898.2  311.38
  4905.8  310.23  4910.8  311.25  4914.8  310.94  4938.7  308.55  4959.0  307.18
  4966.6  306.78  4971.7  307.66  4995.0  305.73  4995.3  305.23  4998.8  305.23
  4999.0  305.73  5020.6  307.86  5041.7  308.17  5062.8  310.38  5084.0  311.34
  5094.4  312.42  5112.3  313.26  5178.7  315.61  5294.7  317.19  5315.8  318.01
#Mann=9,-1,0
  4391.3    0.07       0  4554.7    0.12       0  4628.3    0.07       0
  4868.2    0.12       0  4914.8    0.07       0  4995.0    0.05       0
  4999.0    0.07       0  5084.0    0.12       0  5112.3    0.07       0
Bank Sta=4995,4999
Exp/Cntr=0.3,0.1

Type RM Length L Ch R = 1,726,369,369,369
BEGIN DESCRIPTION:
XS7760
END DESCRIPTION:
XS GIS Cut Line= 3
      2459335.09     13578751.13      2459990.91     13578710.46
      2460102.73     13578532.56
#Sta/Elev= 30
  4459.4  319.76  4476.0  318.57  4481.0  318.92  4559.7  315.09  4620.9  312.54
  4636.9  311.66  4709.8  310.37  4789.9  310.35  4820.0  310.85  4830.0  310.33
  4837.7  310.76  4870.1  310.80  4950.2  309.27  4958.8  307.86  4963.8  307.70
  4970.3  305.99  4980.3  304.73  4988.3  304.46  4988.6  303.96  4992.1  303.96
  4992.3  304.46  5000.3  304.86  5010.4  306.42  5040.4  307.67  5110.6  308.92
  5167.7  310.58  5173.6  311.32  5261.9  313.29  5283.1  313.95  5326.6  316.50
#Mann=6,-1,0
  4459.4    0.12       0  4559.7    0.07       0  4620.9    0.12       0
  4837.7    0.07       0  4988.3    0.05       0  4992.3    0.07       0
Bank Sta=4988.3,4992.3
Exp/Cntr=0.3,0.1

Type RM Length L Ch R = 1,357,0,0,0
BEGIN DESCRIPTION:
XS7759
END DESCRIPTION:
XS GIS Cut Line= 4
      2459350.41     13578939.23      2459995.99     13579056.15
      2460112.92     13578873.14      2460128.11     13578528.72
#Sta/Elev= 30
  4388.3  314.75  4477.5  310.93  4520.9  309.09  4586.1  306.76  4649.0  305.96
  4784.8  306.27  4921.4  305.74  4955.4  304.86  4972.2  301.97  4982.4  301.07
  5006.8  300.81  5007.1  300.31  5010.6  300.31  5010.8  300.81  5023.0  303.37
  5033.2  302.82  5041.3  305.26  5048.0  305.26  5051.7  304.44  5057.7  305.30
  5088.1  305.67  5124.5  307.09  5145.7  305.97  5211.0  306.81  5289.7  307.51
  5359.8  309.11  5389.8  310.51  5440.4  311.13  5519.9  313.14  5606.3  316.47
#Mann=8,-1,0
  4388.3    0.07       0  4477.5    0.12       0  4520.9    0.07       0
  4649.0    0.12       0  5006.8    0.05       0  5010.8    0.12       0
  5211.0     0.1       0  5440.4    0.07       0
Bank Sta=5006.8,5010.8
Exp/Cntr=0.3,0.1

Chan Stop Cuts=-1