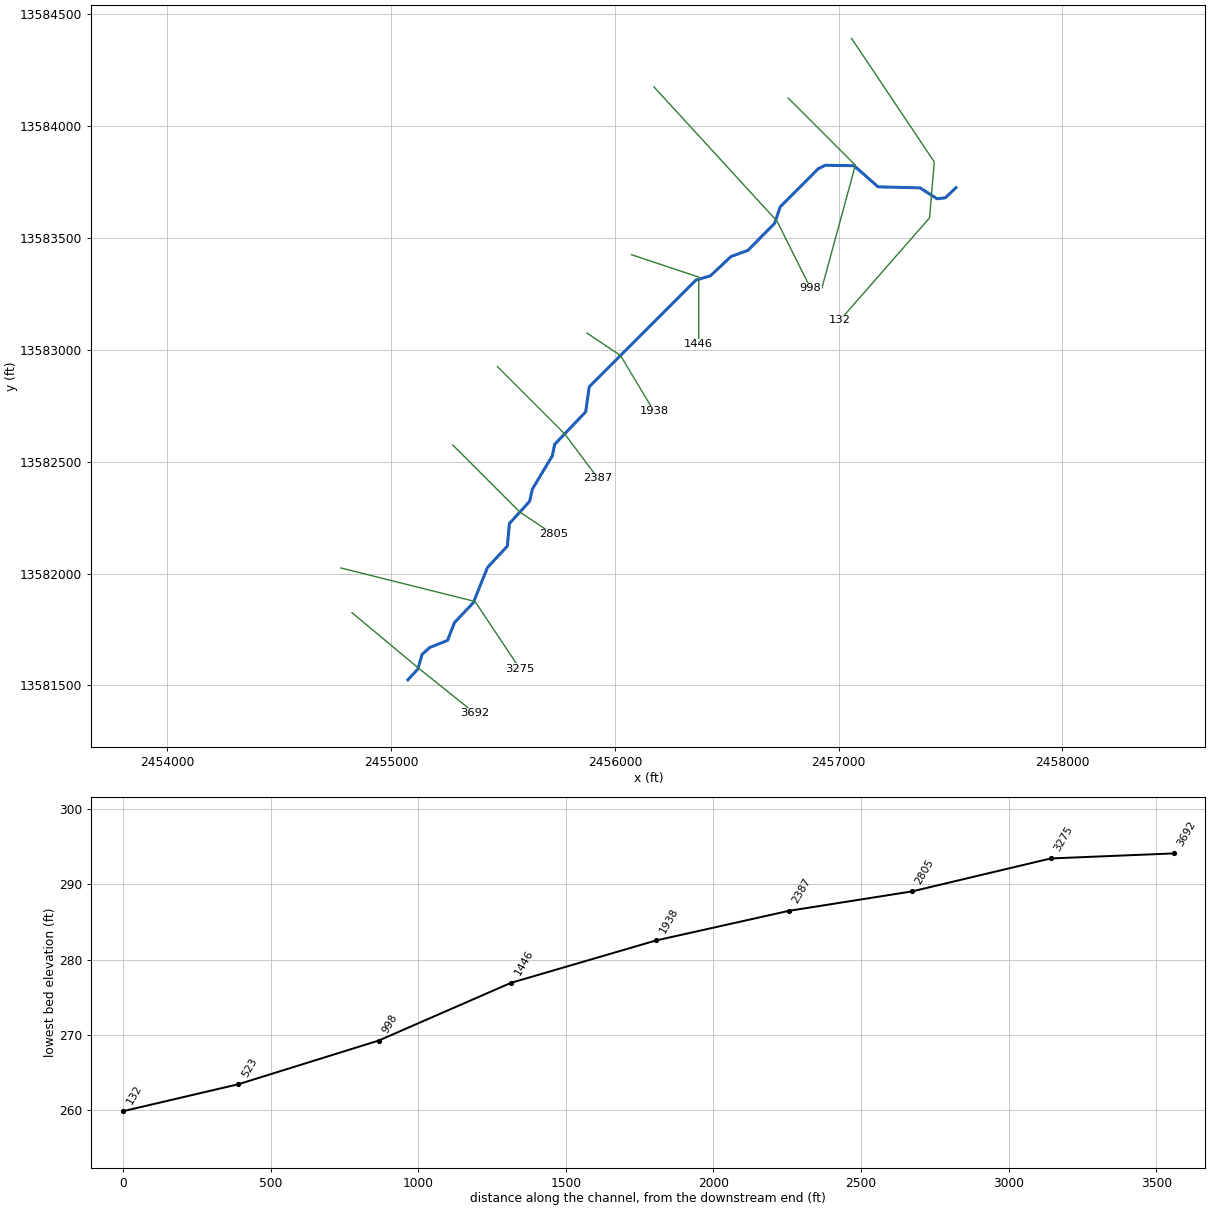
--- Stream0811.prj (project) ---

Proj Title=Stream0811 Base Level Engineering
Current Plan=p01
Default Exp/Contr=0.3,0.1
English Units
Geom File=g01
Flow File=f01
Plan File=p01
BEGIN DESCRIPTION:
Stream0811
END DESCRIPTION:

--- Stream0811.p01 (plan) ---

Plan Title=Multiple Run
Short Identifier=Multiple
Geom File=g01
Flow File=f01
Subcritical Flow
K Sum by GR= 0
Std Step Tol= 0.01
Critical Tol= 0.01
Num of Std Step Trials= 20
Max Error Tol= 0.3
Flow Tol Ratio= 0.001
Split Flow NTrial= 30
Split Flow Tol= 0.02
Split Flow Ratio= 0.02
Log Output Level= 0
Friction Slope Method= 1
Unsteady Friction Slope Method= 2
Unsteady Bridges Friction Slope Method= 1
Parabolic Critical Depth
Global Vel Dist=  1 , 1 , 1
Global Log Level= 0
CheckData=True
Encroach Param= -1, 0, 0, 0
BEGIN DESCRIPTION:
Multiple Run
END DESCRIPTION:

--- Stream0811.f01 (steady flow) ---

Flow Title=Multiple
Number of Profiles=7
Profile Names=10-year,25-year,50-year,1pct_min,100-year,1pct_plu,500-year
River Rch & RM= Stream0811,Reach-1,3692
     618     999    1344     876    1749    3489    2930
Boundary for River Rch & Prof#=Stream0811,Reach-1,1
Up Type=0
Dn Type=3
Dn Slope=0.005
Boundary for River Rch & Prof#=Stream0811,Reach-1,2
Up Type=0
Dn Type=3
Dn Slope=0.005
Boundary for River Rch & Prof#=Stream0811,Reach-1,3
Up Type=0
Dn Type=3
Dn Slope=0.005
Boundary for River Rch & Prof#=Stream0811,Reach-1,4
Up Type=0
Dn Type=3
Dn Slope=0.005
Boundary for River Rch & Prof#=Stream0811,Reach-1,5
Up Type=0
Dn Type=3
Dn Slope=0.005
Boundary for River Rch & Prof#=Stream0811,Reach-1,6
Up Type=0
Dn Type=3
Dn Slope=0.005
Boundary for River Rch & Prof#=Stream0811,Reach-1,7
Up Type=0
Dn Type=3
Dn Slope=0.005

--- Stream0811.g01 (geometry) ---

Geom Title=Existing Conditions

River Reach=Stream0811,Reach-1
Reach XY= 30
      2455075.00     13581525.00      2455119.28     13581572.68
      2455138.42     13581638.60      2455172.48     13581669.24
      2455252.13     13581701.17      2455283.18     13581781.02
      2455366.84     13581868.95      2455430.85     13582027.29
      2455519.46     13582122.58      2455528.63     13582223.50
      2455619.15     13582322.71      2455631.10     13582377.19
      2455720.81     13582526.74      2455730.83     13582577.30
      2455869.48     13582722.57      2455885.52     13582834.79
      2456361.79     13583311.37      2456427.28     13583330.87
      2456518.96     13583416.82      2456595.09     13583444.79
      2456714.22     13583565.32      2456738.63     13583638.21
      2456908.24     13583808.57      2456940.16     13583824.64
      2457069.14     13583822.94      2457176.47     13583728.55
      2457364.51     13583723.77      2457440.33     13583674.97
      2457477.37     13583679.61      2457525.00     13583725.00

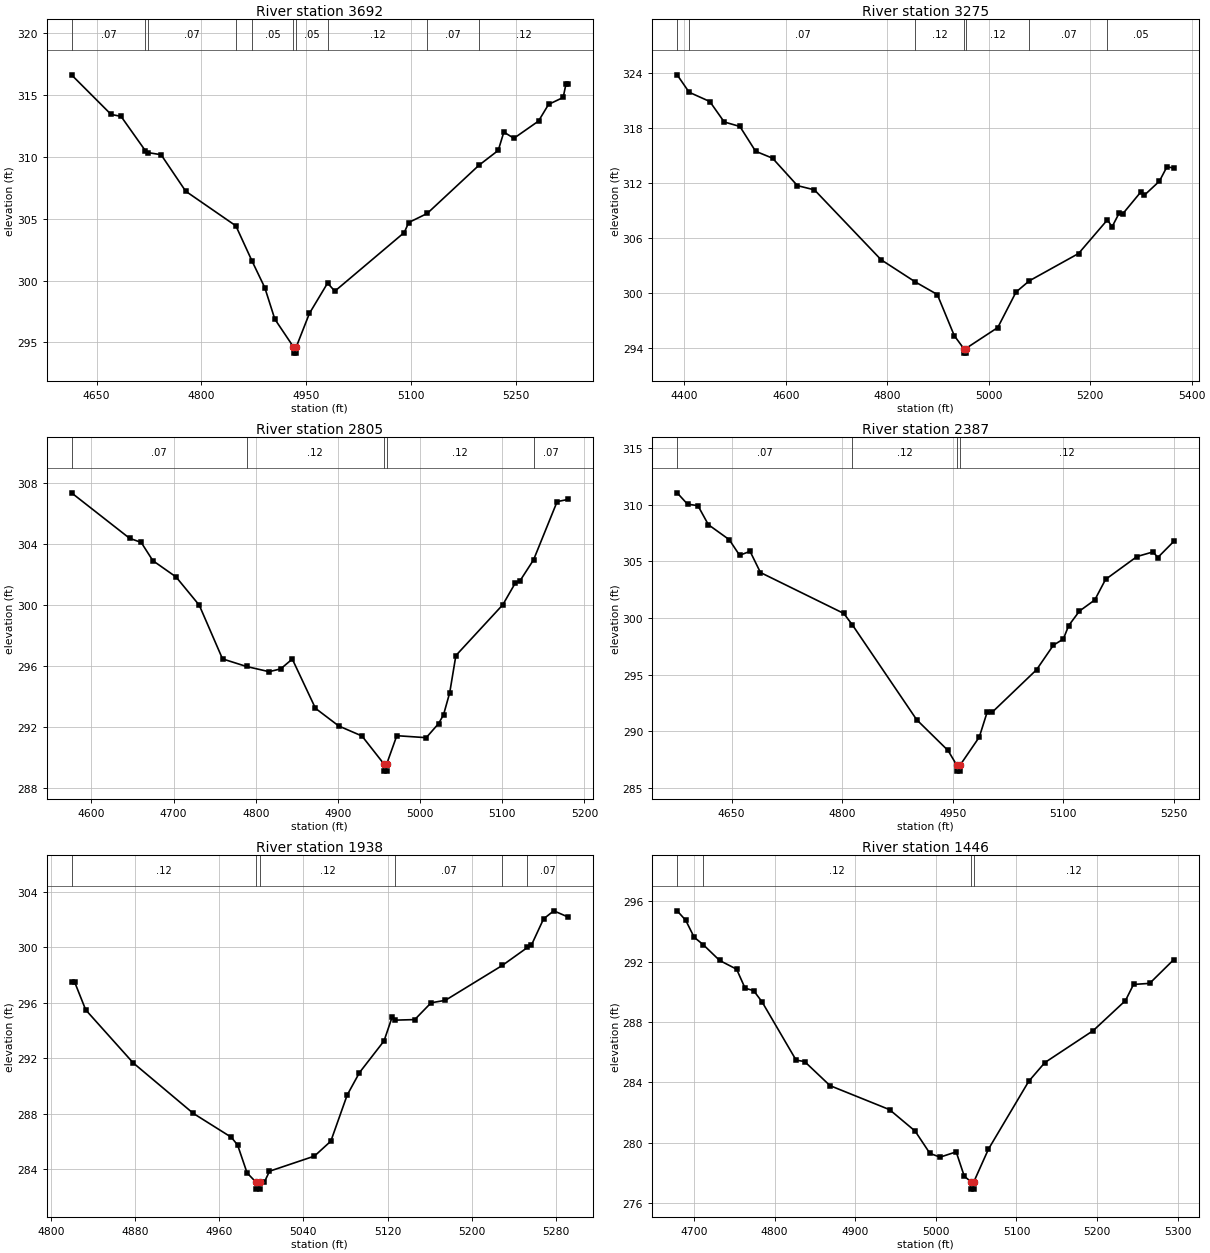
Type RM Length L Ch R = 1,3692,417,417,417
BEGIN DESCRIPTION:
Stream0811 8.0
END DESCRIPTION:
XS GIS Cut Line= 3
      2454825.01     13581824.99      2455125.00     13581575.00
      2455375.03     13581374.97
#Sta/Elev= 30
  4614.1  316.63  4670.7  313.43  4685.0  313.27  4719.6  310.51  4723.9  310.34
  4742.3  310.17  4777.5  307.22  4849.3  304.42  4872.7  301.54  4890.7  299.42
  4905.0  296.88  4931.7  294.63  4931.9  294.13  4935.4  294.13  4935.7  294.63
  4954.5  297.34  4980.5  299.79  4990.9  299.14  5090.2  303.88  5096.6  304.69
  5123.0  305.42  5197.1  309.32  5224.7  310.52  5232.7  312.00  5247.1  311.50
  5282.3  312.89  5296.7  314.24  5317.6  314.80  5321.6  315.89  5324.8  315.89
#Mann=10,-1,0
  4614.1    0.07       0  4719.6    0.12       0  4723.9    0.07       0
  4849.3    0.12       0  4872.7    0.05       0  4931.7    0.05       0
  4935.7    0.05       0  4980.5    0.12       0  5123.0    0.07       0
  5197.1    0.12       0
Bank Sta=4931.7,4935.7
Exp/Cntr=0.3,0.1

Type RM Length L Ch R = 1,3275,470,470,470
BEGIN DESCRIPTION:
Stream0811 7.0
END DESCRIPTION:
XS GIS Cut Line= 3
      2454775.00     13582025.00      2455375.00     13581875.00
      2455574.99     13581575.02
#Sta/Elev= 30
  4385.9  323.80  4409.6  321.90  4450.3  320.89  4478.7  318.66  4509.6  318.17
  4540.5  315.47  4574.0  314.71  4623.0  311.72  4656.5  311.26  4787.9  303.64
  4855.7  301.21  4898.7  299.85  4932.2  295.36  4950.8  293.96  4951.1  293.46
  4954.6  293.46  4954.8  293.96  5017.9  296.25  5053.9  300.12  5080.0  301.34
  5177.1  304.32  5234.0  307.99  5243.2  307.23  5256.8  308.69  5264.3  308.65
  5300.3  311.06  5306.3  310.65  5336.4  312.20  5351.4  313.78  5364.9  313.63
#Mann=7,-1,0
  4385.9    0.05       0  4409.6    0.07       0  4855.7    0.12       0
  4950.8    0.05       0  4954.8    0.12       0  5080.0    0.07       0
  5234.0    0.05       0
Bank Sta=4950.8,4954.8
Exp/Cntr=0.3,0.1

Type RM Length L Ch R = 1,2805,418,418,418
BEGIN DESCRIPTION:
Stream0811 6.0
END DESCRIPTION:
XS GIS Cut Line= 3
      2455275.03     13582574.97      2455575.00     13582275.00
      2455725.00     13582175.00
#Sta/Elev= 30
  4575.8  307.38  4646.5  304.39  4660.6  304.12  4674.8  302.92  4703.0  301.85
  4731.3  299.99  4759.6  296.46  4788.8  295.96  4816.2  295.62  4830.3  295.80
  4844.5  296.45  4872.7  293.21  4901.0  292.05  4929.3  291.39  4955.6  289.58
  4955.8  289.08  4959.3  289.08  4959.6  289.58  4971.7  291.41  5007.5  291.28
  5022.6  292.21  5028.6  292.79  5036.1  294.24  5043.6  296.68  5100.7  300.02
  5115.7  301.43  5121.7  301.60  5138.1  302.97  5166.8  306.80  5180.3  306.95
#Mann=5,-1,0
  4575.8    0.07       0  4788.8    0.12       0  4955.6    0.05       0
  4959.6    0.12       0  5138.1    0.07       0
Bank Sta=4955.6,4959.6
Exp/Cntr=0.3,0.1

Type RM Length L Ch R = 1,2387,449,449,449
BEGIN DESCRIPTION:
Stream0811 5.0
END DESCRIPTION:
XS GIS Cut Line= 3
      2455475.03     13582924.97      2455775.00     13582625.00
      2455924.98     13582425.02
#Sta/Elev= 30
  4576.0  311.04  4590.1  310.04  4604.2  309.91  4618.4  308.23  4646.7  306.91
  4660.8  305.53  4675.0  305.88  4689.1  304.01  4802.2  300.40  4814.0  299.38
  4901.2  291.02  4943.7  288.31  4955.8  286.99  4956.0  286.49  4959.5  286.49
  4959.8  286.99  4986.1  289.49  4996.7  291.67  5003.4  291.67  5063.8  295.43
  5086.7  297.60  5100.2  298.14  5107.5  299.33  5122.1  300.61  5142.9  301.59
  5157.5  303.40  5200.2  305.42  5222.1  305.83  5228.4  305.33  5250.2  306.76
#Mann=4,-1,0
  4576.0    0.07       0  4814.0    0.12       0  4955.8    0.05       0
  4959.8    0.12       0
Bank Sta=4955.8,4959.8
Exp/Cntr=0.3,0.1

Type RM Length L Ch R = 1,1938,492,492,492
BEGIN DESCRIPTION:
Stream0811 4.0
END DESCRIPTION:
XS GIS Cut Line= 3
      2455874.98     13583075.02      2456025.00     13582975.00
      2456175.02     13582724.96
#Sta/Elev= 30
  4819.7  297.48  4822.7  297.48  4833.2  295.48  4878.3  291.66  4935.4  288.02
  4971.5  286.30  4977.5  285.74  4986.5  283.73  4995.0  283.06  4995.3  282.56
  4998.8  282.56  4999.0  283.06  5002.9  283.06  5007.8  283.85  5050.5  284.94
  5066.1  286.02  5081.6  289.34  5093.3  290.96  5116.6  293.24  5124.4  294.98
  5127.1  294.74  5145.8  294.78  5161.3  295.99  5174.9  296.17  5228.9  298.68
  5252.9  299.98  5256.6  300.14  5268.2  302.04  5277.9  302.62  5291.6  302.17
#Mann=6,-1,0
  4819.7    0.12       0  4995.0    0.05       0  4999.0    0.12       0
  5127.1    0.07       0  5228.9    0.12       0  5252.9    0.07       0
Bank Sta=4995,4999
Exp/Cntr=0.3,0.1

Type RM Length L Ch R = 1,1446,448,448,448
BEGIN DESCRIPTION:
Stream0811 3.0
END DESCRIPTION:
XS GIS Cut Line= 3
      2456074.99     13583425.00      2456375.00     13583325.00
      2456375.00     13583025.04
#Sta/Elev= 30
  4679.0  295.37  4689.6  294.75  4700.1  293.62  4711.5  293.12  4731.7  292.08
  4752.8  291.50  4763.3  290.24  4773.9  290.08  4784.4  289.33  4826.6  285.47
  4837.1  285.38  4868.7  283.78  4942.5  282.19  4974.2  280.77  4992.6  279.29
  5005.2  279.04  5025.2  279.39  5035.2  277.78  5043.2  277.42  5043.5  276.92
  5047.0  276.92  5047.2  277.42  5065.2  279.57  5115.2  284.07  5135.2  285.31
  5195.2  287.43  5235.2  289.42  5245.2  290.49  5265.2  290.56  5295.2  292.14
#Mann=4,-1,0
  4679.0    0.07       0  4711.5    0.12       0  5043.2    0.05       0
  5047.2    0.12       0
Bank Sta=5043.2,5047.2
Exp/Cntr=0.3,0.1

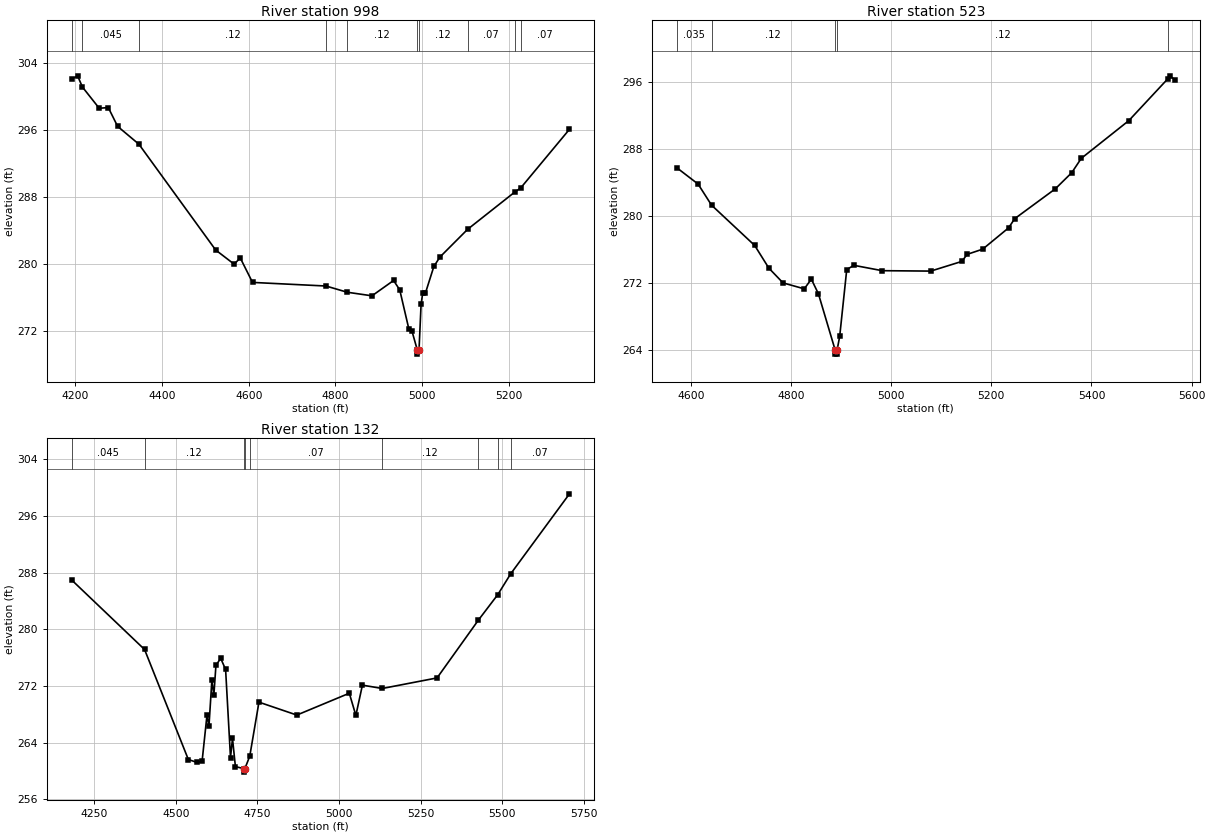
Type RM Length L Ch R = 1,998,475,475,475
BEGIN DESCRIPTION:
Stream0811 2.0
END DESCRIPTION:
XS GIS Cut Line= 3
      2456175.01     13584174.99      2456725.00     13583575.00
      2456874.99     13583275.03
#Sta/Elev= 30
  4191.0  302.06  4204.9  302.47  4216.1  301.13  4254.8  298.60  4275.8  298.68
  4297.3  296.44  4346.4  294.31  4523.6  281.68  4566.2  279.99  4580.4  280.73
  4608.7  277.81  4778.3  277.38  4827.1  276.64  4884.4  276.21  4934.3  278.04
  4948.5  276.92  4969.5  272.26  4976.9  271.97  4989.0  269.75  4989.3  269.25
  4993.0  269.75  4997.8  275.22  5001.5  276.52  5007.7  276.52  5027.3  279.72
  5041.3  280.84  5105.2  284.15  5213.9  288.59  5227.6  289.08  5340.3  296.09
#Mann=10,-1,0
  4191.0   0.035       0  4216.1   0.045       0  4346.4    0.12       0
  4778.3    0.07       0  4827.1    0.12       0  4989.0    0.05       0
  4993.0    0.12       0  5105.2    0.07       0  5213.9    0.12       0
  5227.6    0.07       0
Bank Sta=4989,4993
Exp/Cntr=0.3,0.1

Type RM Length L Ch R = 1,523,391,391,391
BEGIN DESCRIPTION:
Stream0811 1.0
END DESCRIPTION:
XS GIS Cut Line= 3
      2456774.97     13584125.03      2457075.00     13583825.00
      2456925.00     13583274.99
#Sta/Elev= 30
  4571.8  285.72  4614.3  283.77  4641.2  281.25  4727.4  276.43  4755.7  273.72
  4784.0  271.96  4826.4  271.25  4840.5  272.41  4854.7  270.65  4888.0  263.95
  4888.3  263.45  4891.8  263.45  4892.0  263.95  4897.1  265.56  4911.2  273.55
  4925.4  274.06  4982.0  273.42  5079.0  273.37  5141.2  274.53  5151.6  275.37
  5182.7  275.99  5234.5  278.54  5246.6  279.63  5327.8  283.20  5360.6  285.13
  5379.6  286.84  5474.6  291.35  5552.5  296.35  5555.8  296.70  5566.2  296.25
#Mann=5,-1,0
  4571.8   0.035       0  4641.2    0.12       0  4888.0    0.05       0
  4892.0    0.12       0  5552.5    0.07       0
Bank Sta=4888,4892
Exp/Cntr=0.3,0.1

Type RM Length L Ch R = 1,132,0,0,0
BEGIN DESCRIPTION:
XS7762
END DESCRIPTION:
XS GIS Cut Line= 4
      2457057.78     13584392.23      2457427.60     13583840.10
      2457406.77     13583590.10      2457005.74     13583131.79
#Sta/Elev= 30
  4181.0  286.98  4404.5  277.16  4538.5  261.64  4565.6  261.22  4580.6  261.38
  4595.6  267.90  4601.6  266.32  4610.6  272.86  4616.6  270.68  4623.0  274.93
  4637.6  275.91  4652.6  274.34  4667.6  261.92  4673.7  264.61  4682.6  260.64
  4707.7  260.36  4707.9  259.86  4711.7  260.36  4726.6  262.12  4754.7  269.73
  4870.7  267.91  5031.3  270.99  5051.4  267.86  5071.4  272.13  5132.2  271.66
  5300.0  273.15  5426.6  281.31  5485.9  284.90  5525.5  287.84  5705.4  299.12
#Mann=9,-1,0
  4181.0   0.045       0  4404.5    0.12       0  4707.7    0.05       0
  4711.7    0.12       0  4726.6    0.07       0  5132.2    0.12       0
  5426.6    0.07       0  5485.9    0.05       0  5525.5    0.07       0
Bank Sta=4707.7,4711.7
Exp/Cntr=0.3,0.1

Chan Stop Cuts=-1