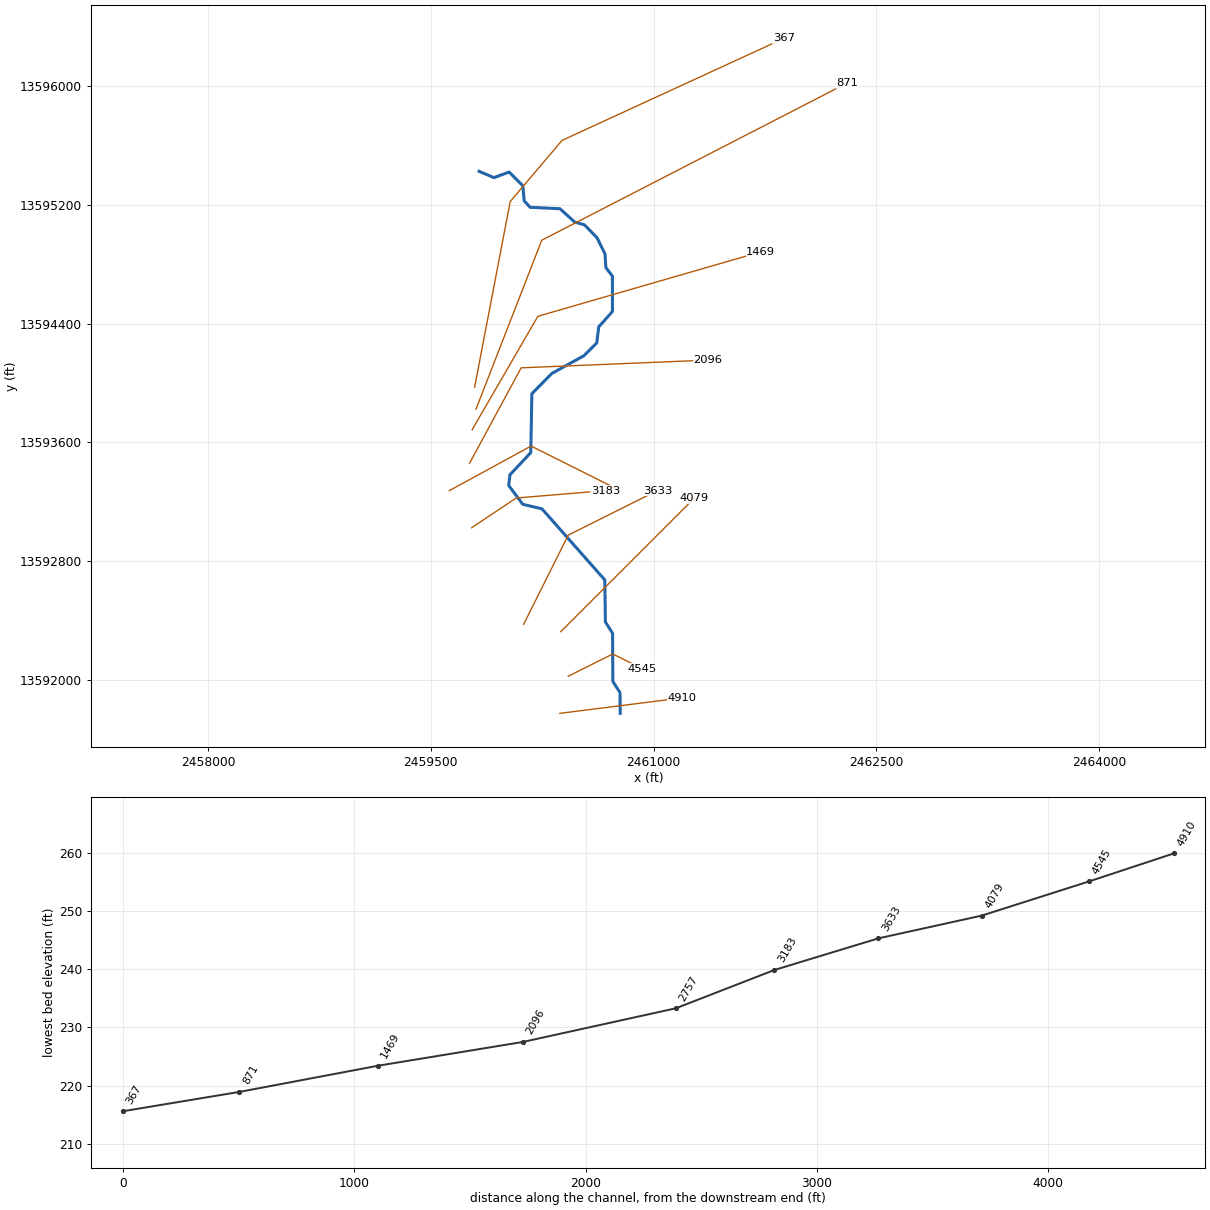
--- Stream0812.prj (project) ---

Proj Title=Stream0812 Base Level Engineering
Current Plan=p01
Default Exp/Contr=0.3,0.1
English Units
Geom File=g01
Flow File=f01
Plan File=p01
BEGIN DESCRIPTION:
Stream0812
END DESCRIPTION:

--- Stream0812.p01 (plan) ---

Plan Title=Multiple Run
Short Identifier=Multiple
Geom File=g01
Flow File=f01
Subcritical Flow
K Sum by GR= 0
Std Step Tol= 0.01
Critical Tol= 0.01
Num of Std Step Trials= 20
Max Error Tol= 0.3
Flow Tol Ratio= 0.001
Split Flow NTrial= 30
Split Flow Tol= 0.02
Split Flow Ratio= 0.02
Log Output Level= 0
Friction Slope Method= 1
Unsteady Friction Slope Method= 2
Unsteady Bridges Friction Slope Method= 1
Parabolic Critical Depth
Global Vel Dist=  1 , 1 , 1
Global Log Level= 0
CheckData=True
Encroach Param= -1, 0, 0, 0
BEGIN DESCRIPTION:
Multiple Run
END DESCRIPTION:

--- Stream0812.f01 (steady flow) ---

Flow Title=Multiple
Number of Profiles=7
Profile Names=10-year,25-year,50-year,1pct_min,100-year,1pct_plu,500-year
River Rch & RM= Stream0812,Reach-1,4910
     298     460     601     382     761    1519    1209
River Rch & RM= Stream0812,Reach-1,3633
     660    1070    1442     942    1879    3749    3161
Boundary for River Rch & Prof#=Stream0812,Reach-1,1
Up Type=0
Dn Type=3
Dn Slope=0.005
Boundary for River Rch & Prof#=Stream0812,Reach-1,2
Up Type=0
Dn Type=3
Dn Slope=0.005
Boundary for River Rch & Prof#=Stream0812,Reach-1,3
Up Type=0
Dn Type=3
Dn Slope=0.005
Boundary for River Rch & Prof#=Stream0812,Reach-1,4
Up Type=0
Dn Type=3
Dn Slope=0.005
Boundary for River Rch & Prof#=Stream0812,Reach-1,5
Up Type=0
Dn Type=3
Dn Slope=0.005
Boundary for River Rch & Prof#=Stream0812,Reach-1,6
Up Type=0
Dn Type=3
Dn Slope=0.005
Boundary for River Rch & Prof#=Stream0812,Reach-1,7
Up Type=0
Dn Type=3
Dn Slope=0.005

--- Stream0812.g01 (geometry) ---

Geom Title=Existing Conditions

River Reach=Stream0812,Reach-1
Reach XY= 30
      2460775.00     13591775.00      2460773.83     13591914.52
      2460725.52     13591990.22      2460723.78     13592314.50
      2460675.52     13592390.22      2460671.46     13592673.54
      2460248.52     13593152.12      2460118.81     13593182.86
      2460024.21     13593309.92      2460032.76     13593381.17
      2460172.94     13593530.85      2460180.46     13593927.45
      2460315.32     13594064.22      2460531.07     13594183.15
      2460617.14     13594268.81      2460630.54     13594377.42
      2460722.93     13594480.86      2460722.74     13594719.06
      2460678.86     13594776.60      2460672.67     13594869.03
      2460619.18     13594977.31      2460534.70     13595064.23
      2460468.96     13595083.18      2460369.14     13595172.93
      2460168.48     13595182.68      2460128.51     13595226.25
      2460119.48     13595327.44      2460027.30     13595419.89
      2459924.97     13595382.35      2459825.00     13595425.00

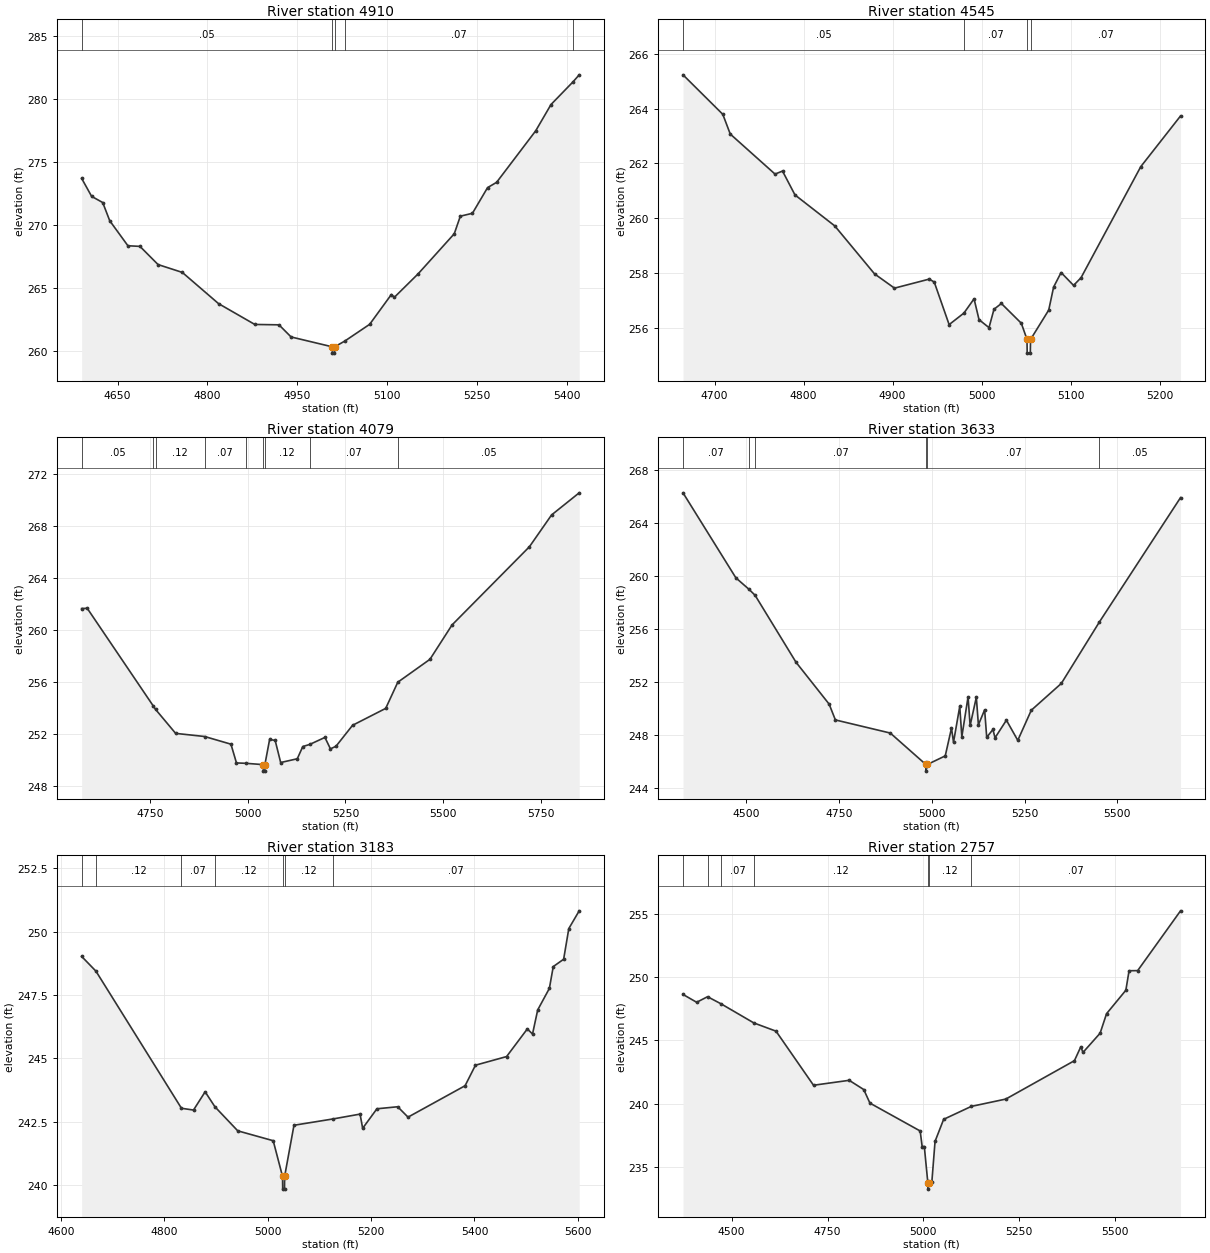
Type RM Length L Ch R = 1,4910,365,365,365
BEGIN DESCRIPTION:
XS7766
END DESCRIPTION:
XS GIS Cut Line= 2
      2460368.56     13591775.17      2461191.62     13591879.14
#Sta/Elev= 30
  4590.2  273.70  4606.8  272.28  4625.3  271.79  4637.0  270.35  4667.3  268.37
  4687.4  268.32  4717.6  266.88  4758.0  266.26  4818.4  263.79  4878.9  262.14
  4919.2  262.11  4939.4  261.15  5008.0  260.37  5008.2  259.87  5011.7  259.87
  5012.0  260.37  5028.8  260.82  5070.4  262.15  5106.6  264.51  5111.6  264.29
  5151.1  266.14  5211.5  269.32  5221.6  270.71  5241.8  270.94  5267.0  272.97
  5282.1  273.39  5347.3  277.47  5372.8  279.55  5409.6  281.35  5419.8  281.90
#Mann=5,-1,0
  4590.2    0.05       0  5008.0    0.05       0  5012.0    0.05       0
  5028.8    0.07       0  5409.6    0.05       0
Bank Sta=5008,5012
Exp/Cntr=0.3,0.1

Type RM Length L Ch R = 1,4545,466,466,466
BEGIN DESCRIPTION:
Stream0812 8.0
END DESCRIPTION:
XS GIS Cut Line= 3
      2460425.02     13592025.01      2460725.00     13592175.00
      2460925.01     13592075.00
#Sta/Elev= 30
  4664.6  265.23  4709.3  263.79  4717.7  263.07  4768.0  261.61  4776.4  261.72
  4790.4  260.85  4835.1  259.72  4879.8  257.97  4902.2  257.45  4941.3  257.78
  4946.9  257.67  4963.6  256.12  4980.2  256.54  4991.6  257.06  4997.2  256.30
  5008.4  256.01  5014.0  256.68  5022.3  256.89  5044.7  256.17  5051.1  255.58
  5051.3  255.08  5054.8  255.08  5055.1  255.58  5075.5  256.65  5081.0  257.49
  5089.4  258.02  5103.4  257.55  5111.8  257.83  5178.9  261.88  5223.6  263.73
#Mann=4,-1,0
  4664.6    0.05       0  4980.2    0.07       0  5051.1    0.05       0
  5055.1    0.07       0
Bank Sta=5051.1,5055.1
Exp/Cntr=0.3,0.1

Type RM Length L Ch R = 1,4079,446,446,446
BEGIN DESCRIPTION:
Stream0812 7.0
END DESCRIPTION:
XS GIS Cut Line= 3
      2460374.99     13592324.99      2460675.00     13592625.00
      2461274.99     13593224.99
#Sta/Elev= 30
  4575.1  261.67  4589.3  261.69  4758.2  254.19  4764.2  253.92  4815.5  252.08
  4889.6  251.84  4957.0  251.25  4971.1  249.81  4995.3  249.78  5039.8  249.68
  5040.1  249.18  5043.6  249.18  5043.8  249.68  5055.9  251.61  5070.1  251.54
  5084.2  249.84  5126.7  250.13  5140.8  251.07  5158.5  251.23  5197.4  251.77
  5211.5  250.89  5225.7  251.09  5268.1  252.70  5352.9  254.00  5383.8  256.01
  5466.1  257.77  5522.6  260.41  5720.6  266.42  5777.2  268.86  5847.9  270.56
#Mann=9,-1,0
  4575.1    0.05       0  4758.2    0.07       0  4764.2    0.12       0
  4889.6    0.07       0  4995.3    0.12       0  5039.8    0.05       0
  5043.8    0.12       0  5158.5    0.07       0  5383.8    0.05       0
Bank Sta=5039.8,5043.8
Exp/Cntr=0.3,0.1

Type RM Length L Ch R = 1,3633,450,450,450
BEGIN DESCRIPTION:
Stream0812 6.0
END DESCRIPTION:
XS GIS Cut Line= 3
      2460124.99     13592374.97      2460425.00     13592975.00
      2461025.02     13593275.01
#Sta/Elev= 30
  4328.9  266.26  4471.5  259.85  4506.3  259.00  4523.2  258.54  4633.6  253.49
  4723.0  250.33  4739.8  249.14  4887.9  248.15  4983.8  245.78  4984.0  245.28
  4987.8  245.78  5036.1  246.43  5052.9  248.52  5058.4  247.46  5075.2  250.16
  5080.8  247.87  5097.6  250.88  5103.2  248.72  5119.9  250.85  5125.5  248.77
  5142.3  249.90  5147.9  247.83  5164.7  248.42  5170.3  247.79  5201.0  249.12
  5231.7  247.60  5268.1  249.87  5349.1  251.89  5451.7  256.52  5670.6  265.90
#Mann=6,-1,0
  4328.9    0.07       0  4506.3   0.035       0  4523.2    0.07       0
  4983.8    0.05       0  4987.8    0.07       0  5451.7    0.05       0
Bank Sta=4983.8,4987.8
Exp/Cntr=0.3,0.1

Type RM Length L Ch R = 1,3183,426,426,426
BEGIN DESCRIPTION:
Stream0812 5.0
END DESCRIPTION:
XS GIS Cut Line= 3
      2459774.96     13593024.98      2460075.00     13593225.00
      2460675.02     13593275.00
#Sta/Elev= 30
  4639.9  249.02  4667.5  248.44  4833.0  243.03  4856.3  242.96  4878.8  243.68
  4897.7  243.09  4941.9  242.14  5010.5  241.75  5028.6  240.34  5028.9  239.84
  5032.4  239.84  5032.6  240.34  5050.7  242.36  5126.6  242.61  5178.6  242.80
  5183.6  242.24  5211.2  243.01  5251.4  243.09  5271.4  242.68  5381.8  243.92
  5401.9  244.73  5462.1  245.07  5502.2  246.16  5512.3  245.96  5522.3  246.91
  5544.9  247.76  5552.4  248.62  5572.5  248.91  5582.5  250.12  5602.6  250.82
#Mann=7,-1,0
  4639.9    0.07       0  4667.5    0.12       0  4833.0    0.07       0
  4897.7    0.12       0  5028.6    0.05       0  5032.6    0.12       0
  5126.6    0.07       0
Bank Sta=5028.6,5032.6
Exp/Cntr=0.3,0.1

Type RM Length L Ch R = 1,2757,661,661,661
BEGIN DESCRIPTION:
Stream0812 4.0
END DESCRIPTION:
XS GIS Cut Line= 3
      2459625.04     13593275.02      2460175.00     13593575.00
      2460775.02     13593274.99
#Sta/Elev= 30
  4373.1  248.63  4408.7  248.01  4437.1  248.45  4472.8  247.88  4557.8  246.38
  4615.6  245.73  4713.4  241.46  4806.4  241.85  4844.4  241.12  4860.5  240.05
  4991.5  237.85  4996.7  236.62  5002.3  236.62  5011.5  233.76  5011.8  233.26
  5015.5  233.76  5021.9  233.81  5030.3  237.03  5052.7  238.77  5124.8  239.79
  5214.8  240.37  5393.7  243.40  5410.4  244.50  5416.0  244.05  5460.7  245.57
  5477.5  247.11  5527.8  248.96  5536.2  250.50  5558.6  250.51  5670.4  255.23
#Mann=7,-1,0
  4373.1    0.07       0  4437.1    0.12       0  4472.8    0.07       0
  4557.8    0.12       0  5011.5    0.05       0  5015.5    0.12       0
  5124.8    0.07       0
Bank Sta=5011.5,5015.5
Exp/Cntr=0.3,0.1

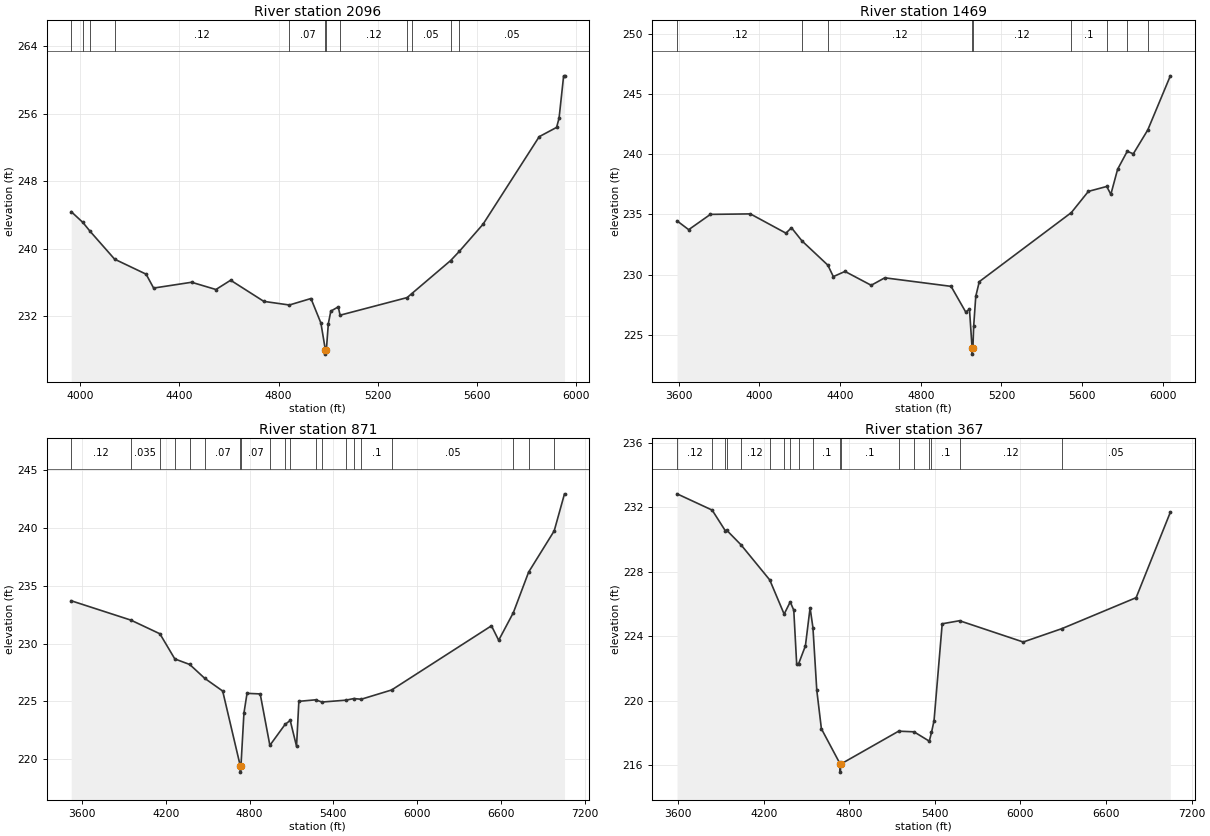
Type RM Length L Ch R = 1,2096,627,627,627
BEGIN DESCRIPTION:
XS7765
END DESCRIPTION:
XS GIS Cut Line= 3
      2459760.94     13593459.20      2460108.16     13594101.56
      2461366.88     13594153.65
#Sta/Elev= 30
  3963.2  244.39  4010.2  243.11  4039.6  242.05  4138.3  238.75  4265.3  236.97
  4295.7  235.32  4448.9  236.01  4547.0  235.15  4606.4  236.25  4740.3  233.74
  4843.2  233.31  4930.4  234.08  4970.5  231.17  4988.5  227.98  4988.7  227.48
  4992.5  227.98  5000.5  231.10  5010.5  232.58  5040.5  233.09  5047.8  232.10
  5318.3  234.19  5337.0  234.66  5494.0  238.59  5528.7  239.67  5624.6  242.90
  5851.2  253.29  5921.3  254.39  5931.3  255.49  5949.7  260.51  5953.2  260.51
#Mann=12,-1,0
  3963.2    0.07       0  4010.2    0.12       0  4039.6    0.07       0
  4138.3    0.12       0  4843.2    0.07       0  4988.5    0.05       0
  4992.5    0.07       0  5047.8    0.12       0  5318.3    0.07       0
  5337.0    0.05       0  5494.0    0.07       0  5528.7    0.05       0
Bank Sta=4988.5,4992.5
Exp/Cntr=0.3,0.1

Type RM Length L Ch R = 1,1469,598,598,598
BEGIN DESCRIPTION:
XS7764
END DESCRIPTION:
XS GIS Cut Line= 3
      2459778.29     13593684.89      2460221.01     13594448.78
      2461721.39     13594882.42
#Sta/Elev= 30
  3592.4  234.46  3650.1  233.73  3757.7  235.00  3955.7  235.04  4132.1  233.44
  4159.4  233.89  4211.3  232.80  4339.8  230.78  4366.9  229.83  4424.7  230.26
  4554.6  229.11  4621.9  229.73  4950.5  229.02  5022.9  226.89  5041.6  227.12
  5054.6  223.89  5054.8  223.39  5058.6  223.89  5062.4  225.70  5072.8  228.19
  5090.2  229.41  5546.5  235.15  5630.9  236.91  5722.0  237.32  5742.2  236.66
  5775.8  238.75  5823.5  240.24  5853.5  240.03  5925.1  242.01  6037.1  246.51
#Mann=9,-1,0
  3592.4    0.12       0  4211.3   0.035       0  4339.8    0.12       0
  5054.6    0.05       0  5058.6    0.12       0  5546.5     0.1       0
  5722.0    0.12       0  5823.5    0.07       0  5925.1    0.05       0
Bank Sta=5054.6,5058.6
Exp/Cntr=0.3,0.1

Type RM Length L Ch R = 1,871,504,504,504
BEGIN DESCRIPTION:
XS7763
END DESCRIPTION:
XS GIS Cut Line= 3
      2459804.33     13593823.76      2460247.05     13594960.94
      2462304.35     13596019.97
#Sta/Elev= 30
  3521.6  233.69  3949.1  232.02  4157.0  230.84  4263.9  228.67  4370.9  228.19
  4477.8  227.00  4606.8  225.90  4733.6  219.40  4733.8  218.90  4737.6  219.40
  4759.1  223.99  4781.3  225.70  4875.6  225.65  4944.9  221.21  5054.0  223.02
  5090.7  223.36  5136.0  221.13  5152.6  225.01  5272.1  225.14  5318.6  224.95
  5490.1  225.11  5546.5  225.25  5599.2  225.19  5817.2  225.99  6532.5  231.53
  6584.2  230.28  6689.5  232.67  6798.6  236.16  6981.9  239.72  7055.8  242.92
#Mann=20,-1,0
  3521.6    0.12       0  3949.1   0.035       0  4157.0    0.12       0
  4263.9   0.035       0  4370.9    0.07       0  4477.8    0.07       0
  4733.6    0.05       0  4737.6    0.07       0  4944.9    0.12       0
  5054.0     0.1       0  5090.7    0.12       0  5272.1     0.1       0
  5318.6    0.12       0  5490.1     0.1       0  5546.5    0.12       0
  5599.2     0.1       0  5817.2    0.05       0  6689.5   0.035       0
  6798.6    0.12       0  6981.9    0.07       0
Bank Sta=4733.6,4737.6
Exp/Cntr=0.3,0.1

Type RM Length L Ch R = 1,367,0,0,0
BEGIN DESCRIPTION:
H21095
END DESCRIPTION:
XS GIS Cut Line= 4
      2459795.06     13593971.57      2460034.64     13595221.54
      2460383.59     13595633.00      2461877.79     13596320.23
#Sta/Elev= 30
  3593.3  232.84  3839.4  231.83  3931.6  230.55  3940.3  230.59  4041.2  229.68
  4242.9  227.50  4343.8  225.38  4386.5  226.14  4411.3  225.62  4431.7  222.27
  4444.7  222.29  4492.8  223.41  4525.6  225.77  4545.6  224.54  4572.5  220.66
  4604.8  218.27  4736.7  216.08  4737.0  215.58  4740.7  216.08  5146.2  218.12
  5253.8  218.08  5361.0  217.50  5376.4  218.04  5394.2  218.77  5451.4  224.78
  5572.9  224.97  6019.3  223.65  6290.4  224.48  6810.4  226.40  7050.2  231.70
#Mann=18,-1,0
  3593.3    0.12       0  3839.4   0.035       0  3931.6    0.12       0
  3940.3   0.035       0  4041.2    0.12       0  4242.9    0.07       0
  4343.8   0.035       0  4386.5    0.07       0  4444.7   0.035       0
  4545.6     0.1       0  4736.7    0.05       0  4740.7     0.1       0
  5146.2    0.12       0  5253.8     0.1       0  5361.0    0.12       0
  5376.4     0.1       0  5572.9    0.12       0  6290.4    0.05       0
Bank Sta=4736.7,4740.7
Exp/Cntr=0.3,0.1

Chan Stop Cuts=-1