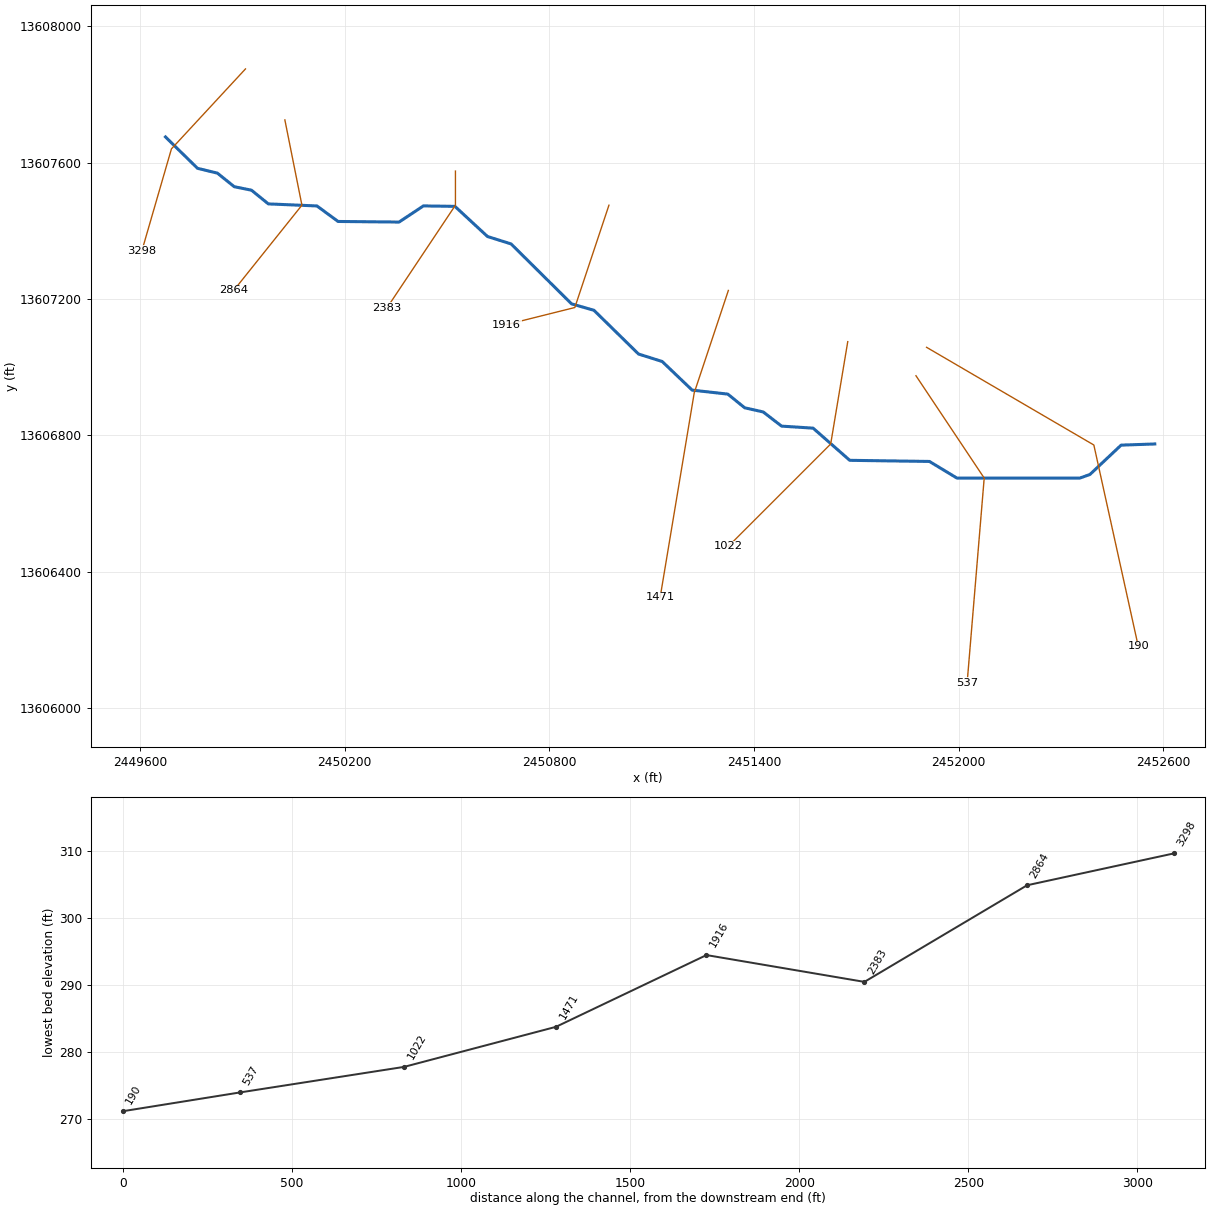
--- Stream0814.prj (project) ---

Proj Title=Stream0814 Base Level Engineering
Current Plan=p01
Default Exp/Contr=0.3,0.1
English Units
Geom File=g01
Flow File=f01
Plan File=p01
BEGIN DESCRIPTION:
Stream0814
END DESCRIPTION:

--- Stream0814.p01 (plan) ---

Plan Title=Multiple Run
Short Identifier=Multiple
Geom File=g01
Flow File=f01
Subcritical Flow
K Sum by GR= 0
Std Step Tol= 0.01
Critical Tol= 0.01
Num of Std Step Trials= 20
Max Error Tol= 0.3
Flow Tol Ratio= 0.001
Split Flow NTrial= 30
Split Flow Tol= 0.02
Split Flow Ratio= 0.02
Log Output Level= 0
Friction Slope Method= 1
Unsteady Friction Slope Method= 2
Unsteady Bridges Friction Slope Method= 1
Parabolic Critical Depth
Global Vel Dist=  1 , 1 , 1
Global Log Level= 0
CheckData=True
Encroach Param= -1, 0, 0, 0
BEGIN DESCRIPTION:
Multiple Run
END DESCRIPTION:

--- Stream0814.f01 (steady flow) ---

Flow Title=Multiple
Number of Profiles=7
Profile Names=10-year,25-year,50-year,1pct_min,100-year,1pct_plu,500-year
River Rch & RM= Stream0814,Reach-1,3298
     603     981    1327     871    1737    3467    2948
Boundary for River Rch & Prof#=Stream0814,Reach-1,1
Up Type=0
Dn Type=3
Dn Slope=0.005
Boundary for River Rch & Prof#=Stream0814,Reach-1,2
Up Type=0
Dn Type=3
Dn Slope=0.005
Boundary for River Rch & Prof#=Stream0814,Reach-1,3
Up Type=0
Dn Type=3
Dn Slope=0.005
Boundary for River Rch & Prof#=Stream0814,Reach-1,4
Up Type=0
Dn Type=3
Dn Slope=0.005
Boundary for River Rch & Prof#=Stream0814,Reach-1,5
Up Type=0
Dn Type=3
Dn Slope=0.005
Boundary for River Rch & Prof#=Stream0814,Reach-1,6
Up Type=0
Dn Type=3
Dn Slope=0.005
Boundary for River Rch & Prof#=Stream0814,Reach-1,7
Up Type=0
Dn Type=3
Dn Slope=0.005

--- Stream0814.g01 (geometry) ---

Geom Title=Existing Conditions

River Reach=Stream0814,Reach-1
Reach XY= 30
      2449675.00     13607675.00      2449768.92     13607583.09
      2449827.19     13607568.90      2449876.72     13607529.16
      2449927.18     13607518.88      2449976.56     13607478.76
      2450119.06     13607472.73      2450180.94     13607427.26
      2450359.78     13607425.52      2450430.98     13607472.84
      2450523.50     13607471.53      2450618.96     13607383.18
      2450688.21     13607361.37      2450865.32     13607185.78
      2450931.05     13607166.84      2451061.79     13607038.63
      2451131.04     13607016.82      2451218.84     13606932.88
      2451323.41     13606921.17      2451372.82     13606881.11
      2451427.18     13606868.89      2451480.97     13606827.33
      2451573.50     13606821.38      2451680.86     13606727.07
      2451914.50     13606723.78      2451995.03     13606675.07
      2452355.02     13606674.96      2452384.79     13606685.50
      2452476.41     13606771.61      2452575.00     13606775.00

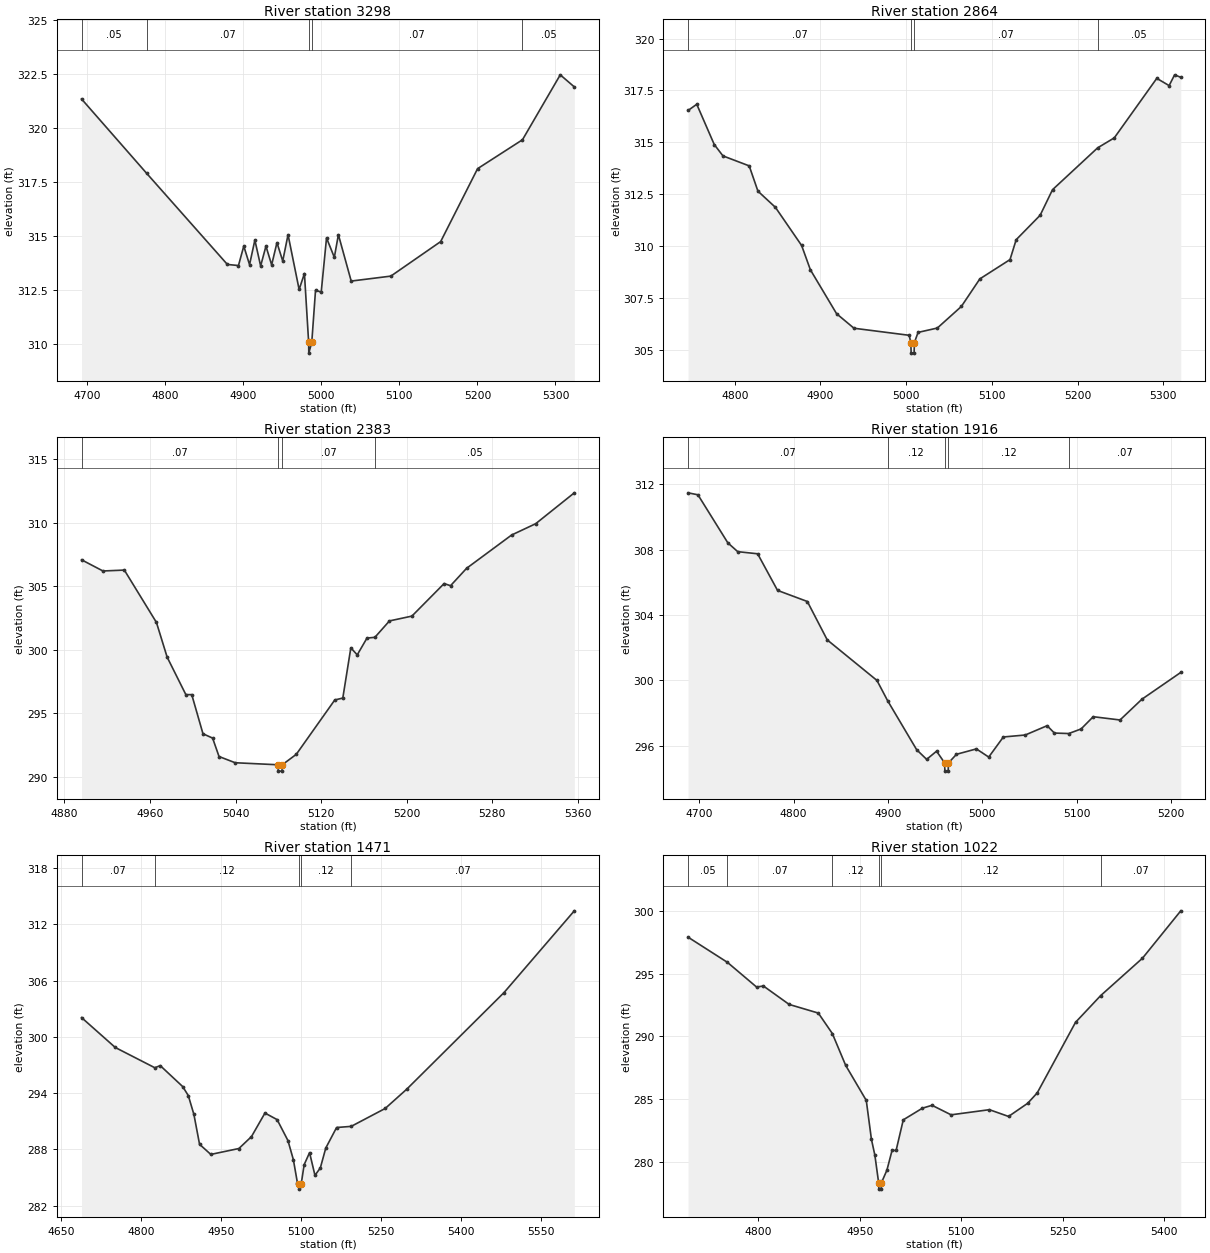
Type RM Length L Ch R = 1,3298,434,434,434
BEGIN DESCRIPTION:
XS7768
END DESCRIPTION:
XS GIS Cut Line= 3
      2449909.45     13607874.38      2449692.45     13607640.02
      2449605.64     13607340.55
#Sta/Elev= 30
  4692.9  321.35  4776.4  317.90  4879.7  313.68  4893.9  313.63  4900.7  314.53
  4908.1  313.67  4914.9  314.81  4922.3  313.61  4929.1  314.53  4936.4  313.66
  4943.2  314.69  4950.6  313.84  4957.4  315.06  4971.6  312.52  4978.4  313.26
  4983.8  310.07  4984.0  309.57  4987.8  310.07  4992.6  312.48  4999.9  312.40
  5006.7  314.91  5016.7  314.01  5021.9  315.06  5038.3  312.91  5089.1  313.14
  5152.9  314.74  5200.2  318.12  5257.7  319.46  5306.1  322.47  5324.1  321.91
#Mann=5,-1,0
  4692.9    0.05       0  4776.4    0.07       0  4983.8    0.05       0
  4987.8    0.07       0  5257.7    0.05       0
Bank Sta=4983.8,4987.8
Exp/Cntr=0.3,0.1

Type RM Length L Ch R = 1,2864,481,481,481
BEGIN DESCRIPTION:
Stream0814 6.0
END DESCRIPTION:
XS GIS Cut Line= 3
      2450025.00     13607724.99      2450075.00     13607475.00
      2449875.00     13607224.99
#Sta/Elev= 30
  4745.4  316.53  4755.6  316.83  4776.0  314.89  4786.2  314.34  4816.8  313.86
  4827.0  312.64  4847.4  311.86  4878.0  310.02  4888.2  308.85  4918.8  306.73
  4939.1  306.03  5003.5  305.69  5005.5  305.33  5005.8  304.83  5009.3  304.83
  5009.5  305.33  5013.9  305.83  5036.4  306.04  5064.4  307.08  5086.0  308.41
  5121.2  309.34  5128.4  310.30  5156.4  311.48  5170.8  312.71  5223.5  314.73
  5242.9  315.21  5292.5  318.08  5306.9  317.73  5313.3  318.25  5320.5  318.13
#Mann=4,-1,0
  4745.4    0.07       0  5005.5    0.05       0  5009.5    0.07       0
  5223.5    0.05       0
Bank Sta=5005.5,5009.5
Exp/Cntr=0.3,0.1

Type RM Length L Ch R = 1,2383,467,467,467
BEGIN DESCRIPTION:
Stream0814 5.0
END DESCRIPTION:
XS GIS Cut Line= 3
      2450525.00     13607575.00      2450525.00     13607475.00
      2450324.98     13607174.96
#Sta/Elev= 30
  4896.1  307.08  4916.1  306.20  4936.1  306.27  4966.1  302.15  4976.1  299.42
  4993.6  296.47  4999.1  296.47  5009.6  293.39  5018.6  293.05  5024.6  291.60
  5039.7  291.11  5079.7  290.95  5080.0  290.45  5083.5  290.45  5083.7  290.95
  5096.8  291.77  5132.8  296.05  5140.3  296.20  5147.8  300.15  5153.8  299.60
  5162.9  300.92  5170.3  300.98  5183.9  302.27  5204.9  302.65  5235.0  305.21
  5241.0  305.04  5256.0  306.41  5298.1  309.03  5320.6  309.92  5356.7  312.35
#Mann=4,-1,0
  4896.1    0.07       0  5079.7    0.05       0  5083.7    0.07       0
  5170.3    0.05       0
Bank Sta=5079.7,5083.7
Exp/Cntr=0.3,0.1

Type RM Length L Ch R = 1,1916,445,445,445
BEGIN DESCRIPTION:
Stream0814 4.0
END DESCRIPTION:
XS GIS Cut Line= 3
      2450975.00     13607475.00      2450875.00     13607175.00
      2450674.99     13607125.00
#Sta/Elev= 30
  4688.1  311.47  4698.6  311.35  4730.3  308.41  4740.8  307.87  4761.9  307.74
  4783.0  305.50  4814.6  304.82  4835.7  302.47  4888.4  299.99  4899.7  298.75
  4930.5  295.75  4941.1  295.16  4951.6  295.66  4960.2  294.94  4960.4  294.44
  4963.9  294.44  4964.2  294.94  4972.7  295.47  4993.8  295.80  5006.9  295.30
  5022.4  296.53  5045.6  296.65  5068.8  297.22  5076.5  296.77  5091.7  296.74
  5104.8  297.02  5117.7  297.77  5146.1  297.57  5169.3  298.84  5210.5  300.48
#Mann=5,-1,0
  4688.1    0.07       0  4899.7    0.12       0  4960.2    0.05       0
  4964.2    0.12       0  5091.7    0.07       0
Bank Sta=4960.2,4964.2
Exp/Cntr=0.3,0.1

Type RM Length L Ch R = 1,1471,449,449,449
BEGIN DESCRIPTION:
Stream0814 3.0
END DESCRIPTION:
XS GIS Cut Line= 3
      2451325.01     13607225.02      2451225.00     13606925.00
      2451125.00     13606325.02
#Sta/Elev= 30
  4687.7  302.05  4751.0  298.86  4825.2  296.70  4835.3  296.93  4877.5  294.69
  4888.0  293.73  4898.5  291.72  4909.1  288.54  4930.2  287.46  4982.9  288.09
  5006.5  289.36  5031.8  291.87  5054.6  291.17  5074.9  288.94  5085.1  286.90
  5092.7  284.43  5095.7  284.26  5096.0  283.76  5099.7  284.26  5105.3  286.36
  5115.5  287.65  5125.6  285.23  5135.7  286.02  5145.9  288.14  5166.2  290.33
  5193.6  290.45  5257.4  292.36  5297.9  294.42  5480.4  304.72  5612.2  313.43
#Mann=5,-1,0
  4687.7    0.07       0  4825.2    0.12       0  5095.7    0.05       0
  5099.7    0.12       0  5193.6    0.07       0
Bank Sta=5095.7,5099.7
Exp/Cntr=0.3,0.1

Type RM Length L Ch R = 1,1022,485,485,485
BEGIN DESCRIPTION:
Stream0814 2.0
END DESCRIPTION:
XS GIS Cut Line= 3
      2451674.99     13607074.95      2451625.00     13606775.00
      2451324.97     13606474.97
#Sta/Elev= 30
  4695.9  297.91  4754.1  295.90  4797.2  293.93  4807.4  294.01  4845.4  292.54
  4888.5  291.85  4909.2  290.22  4929.0  287.67  4959.4  284.88  4967.0  281.78
  4972.1  280.51  4977.7  278.30  4978.0  277.80  4981.5  277.80  4981.7  278.30
  4989.9  279.31  4997.5  280.89  5003.5  280.89  5014.1  283.33  5042.4  284.26
  5056.6  284.49  5084.8  283.73  5141.4  284.14  5169.7  283.60  5198.0  284.65
  5212.1  285.48  5268.7  291.11  5305.8  293.24  5367.7  296.23  5424.3  300.01
#Mann=6,-1,0
  4695.9    0.05       0  4754.1    0.07       0  4909.2    0.12       0
  4977.7    0.05       0  4981.7    0.12       0  5305.8    0.07       0
Bank Sta=4977.7,4981.7
Exp/Cntr=0.3,0.1

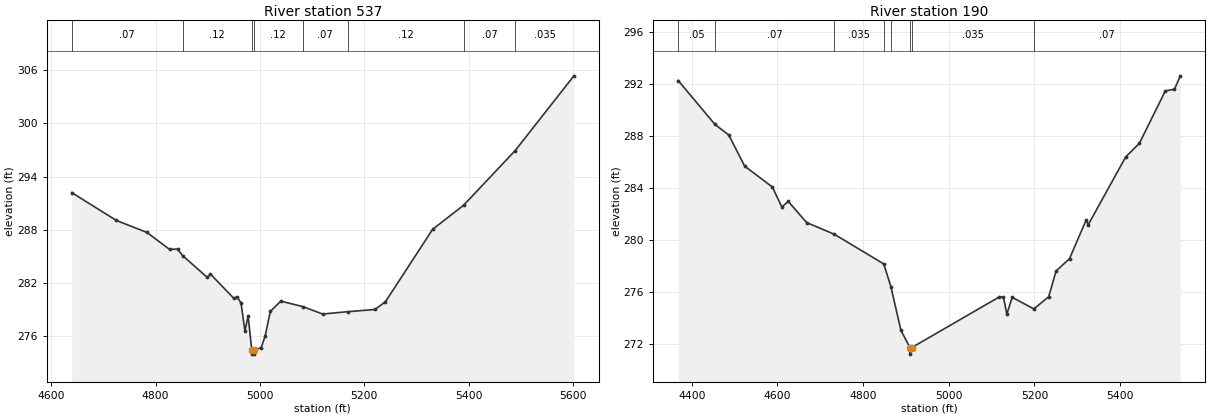
Type RM Length L Ch R = 1,537,347,347,347
BEGIN DESCRIPTION:
Stream0814 1.0
END DESCRIPTION:
XS GIS Cut Line= 3
      2451875.02     13606974.97      2452075.00     13606675.00
      2452025.00     13606074.99
#Sta/Elev= 30
  4639.4  292.20  4725.0  289.06  4783.6  287.71  4827.1  285.79  4842.2  285.84
  4851.9  285.10  4899.3  282.64  4905.3  283.02  4950.3  280.27  4956.3  280.47
  4963.9  279.75  4971.4  276.57  4977.4  278.32  4984.4  274.50  4984.6  274.00
  4988.1  274.00  4988.4  274.50  5002.4  274.71  5009.9  275.99  5020.0  278.81
  5040.1  279.97  5082.2  279.36  5120.3  278.52  5168.2  278.78  5220.7  279.03
  5240.7  279.90  5331.1  288.06  5390.4  290.77  5489.5  296.94  5602.0  305.36
#Mann=8,-1,0
  4639.4    0.07       0  4851.9    0.12       0  4984.4    0.05       0
  4988.4    0.12       0  5082.2    0.07       0  5168.2    0.12       0
  5390.4    0.07       0  5489.5   0.035       0
Bank Sta=4984.4,4988.4
Exp/Cntr=0.3,0.1

Type RM Length L Ch R = 1,190,0,0,0
BEGIN DESCRIPTION:
XS7767
END DESCRIPTION:
XS GIS Cut Line= 3
      2451906.02     13607058.40      2452396.44     13606771.96
      2452526.65     13606181.70
#Sta/Elev= 30
  4368.3  292.25  4454.2  288.87  4486.4  288.06  4523.6  285.66  4588.1  284.06
  4610.3  282.52  4625.3  282.95  4668.3  281.32  4732.4  280.43  4848.3  278.14
  4865.0  276.39  4888.3  273.04  4909.4  271.70  4909.7  271.20  4913.4  271.70
  5117.5  275.59  5127.7  275.61  5135.6  274.28  5148.2  275.57  5198.7  274.68
  5233.3  275.61  5250.6  277.59  5282.1  278.55  5320.7  281.51  5325.8  281.16
  5413.2  286.37  5445.2  287.42  5505.7  291.45  5527.1  291.58  5540.7  292.61
#Mann=8,-1,0
  4368.3    0.05       0  4454.2    0.07       0  4732.4   0.035       0
  4848.3    0.07       0  4865.0   0.035       0  4909.4   0.035       0
  4913.4   0.035       0  5198.7    0.07       0
Bank Sta=4909.4,4913.4
Exp/Cntr=0.3,0.1

Chan Stop Cuts=-1