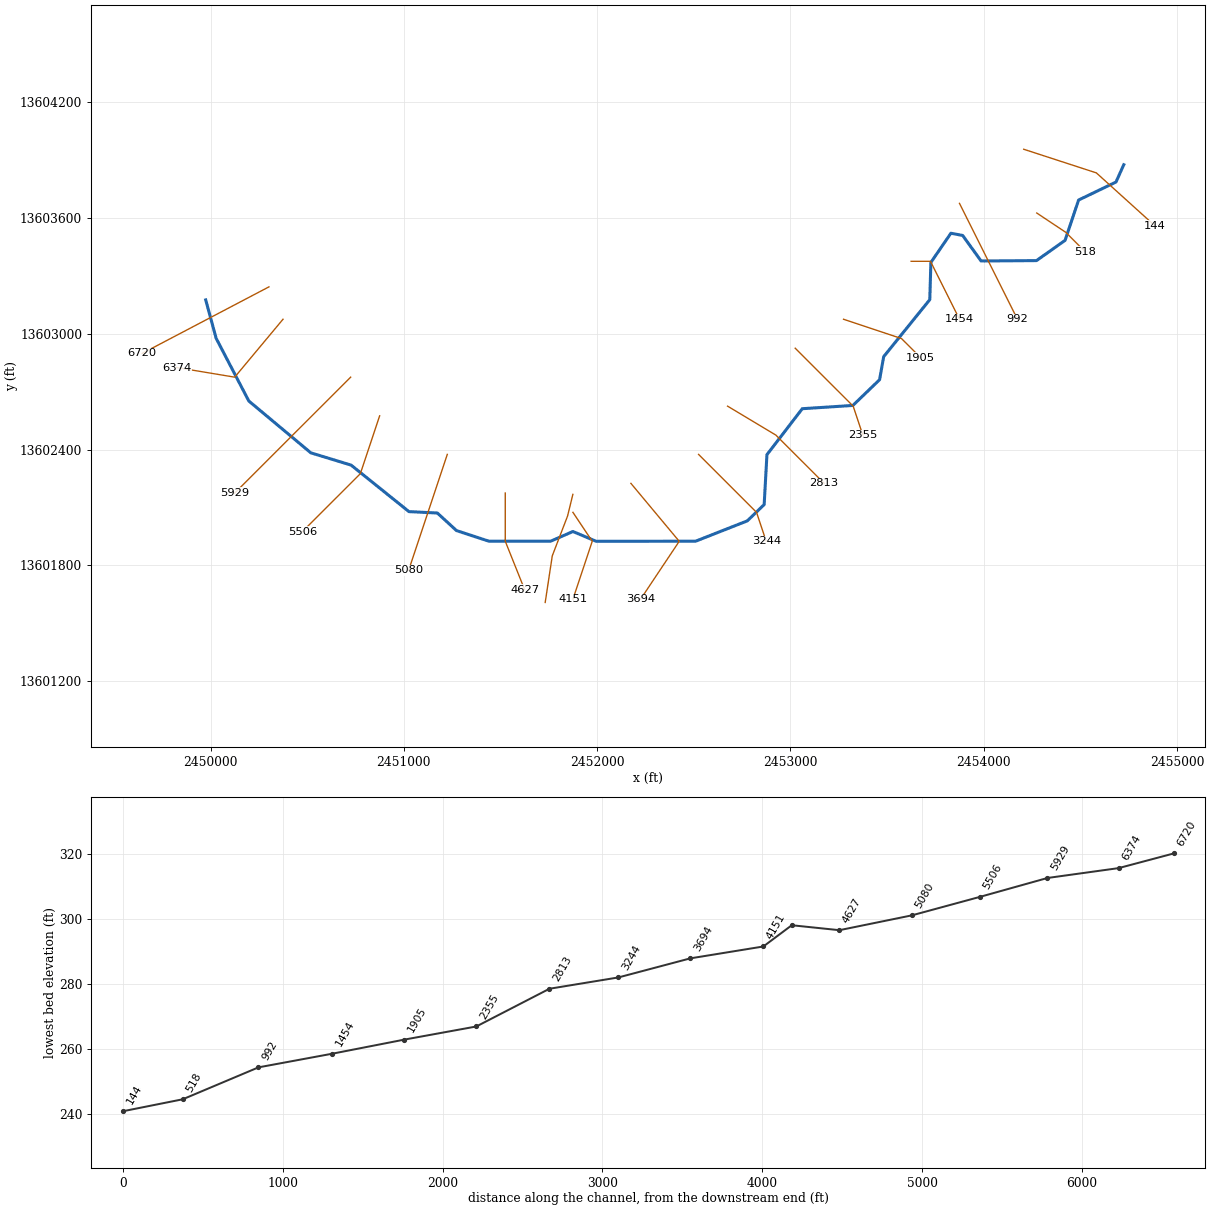
--- Stream0815.prj (project) ---

Proj Title=Stream0815 Base Level Engineering
Current Plan=p01
Default Exp/Contr=0.3,0.1
English Units
Geom File=g01
Flow File=f01
Plan File=p01
BEGIN DESCRIPTION:
Stream0815
END DESCRIPTION:

--- Stream0815.p01 (plan) ---

Plan Title=Multiple Run
Short Identifier=Multiple
Geom File=g01
Flow File=f01
Subcritical Flow
K Sum by GR= 0
Std Step Tol= 0.01
Critical Tol= 0.01
Num of Std Step Trials= 20
Max Error Tol= 0.3
Flow Tol Ratio= 0.001
Split Flow NTrial= 30
Split Flow Tol= 0.02
Split Flow Ratio= 0.02
Log Output Level= 0
Friction Slope Method= 1
Unsteady Friction Slope Method= 2
Unsteady Bridges Friction Slope Method= 1
Parabolic Critical Depth
Global Vel Dist=  1 , 1 , 1
Global Log Level= 0
CheckData=True
Encroach Param= -1, 0, 0, 0
BEGIN DESCRIPTION:
Multiple Run
END DESCRIPTION:

--- Stream0815.f01 (steady flow) ---

Flow Title=Multiple
Number of Profiles=7
Profile Names=10-year,25-year,50-year,1pct_min,100-year,1pct_plu,500-year
River Rch & RM= Stream0815,Reach-1,6720
     723    1184    1608    1059    2113    4215    3609
Boundary for River Rch & Prof#=Stream0815,Reach-1,1
Up Type=0
Dn Type=3
Dn Slope=0.005
Boundary for River Rch & Prof#=Stream0815,Reach-1,2
Up Type=0
Dn Type=3
Dn Slope=0.005
Boundary for River Rch & Prof#=Stream0815,Reach-1,3
Up Type=0
Dn Type=3
Dn Slope=0.005
Boundary for River Rch & Prof#=Stream0815,Reach-1,4
Up Type=0
Dn Type=3
Dn Slope=0.005
Boundary for River Rch & Prof#=Stream0815,Reach-1,5
Up Type=0
Dn Type=3
Dn Slope=0.005
Boundary for River Rch & Prof#=Stream0815,Reach-1,6
Up Type=0
Dn Type=3
Dn Slope=0.005
Boundary for River Rch & Prof#=Stream0815,Reach-1,7
Up Type=0
Dn Type=3
Dn Slope=0.005

--- Stream0815.g01 (geometry) ---

Geom Title=Existing Conditions

River Reach=Stream0815,Reach-1
Reach XY= 30
      2449975.00     13603175.00      2450028.82     13602976.58
      2450197.99     13602651.48      2450518.94     13602383.14
      2450727.43     13602319.48      2451026.56     13602078.76
      2451173.53     13602071.44      2451272.58     13601980.54
      2451440.22     13601925.52      2451759.78     13601925.52
      2451875.00     13601975.82      2451995.03     13601925.07
      2452509.78     13601925.52      2452777.31     13602030.82
      2452864.53     13602115.18      2452878.75     13602373.45
      2453061.68     13602611.63      2453323.54     13602628.54
      2453461.60     13602761.70      2453482.86     13602881.17
      2453721.45     13603176.47      2453727.07     13603369.15
      2453830.62     13603520.26      2453891.51     13603508.88
      2453986.83     13603376.62      2454273.53     13603378.55
      2454421.49     13603483.48      2454491.30     13603692.13
      2454684.98     13603785.55      2454725.00     13603875.00

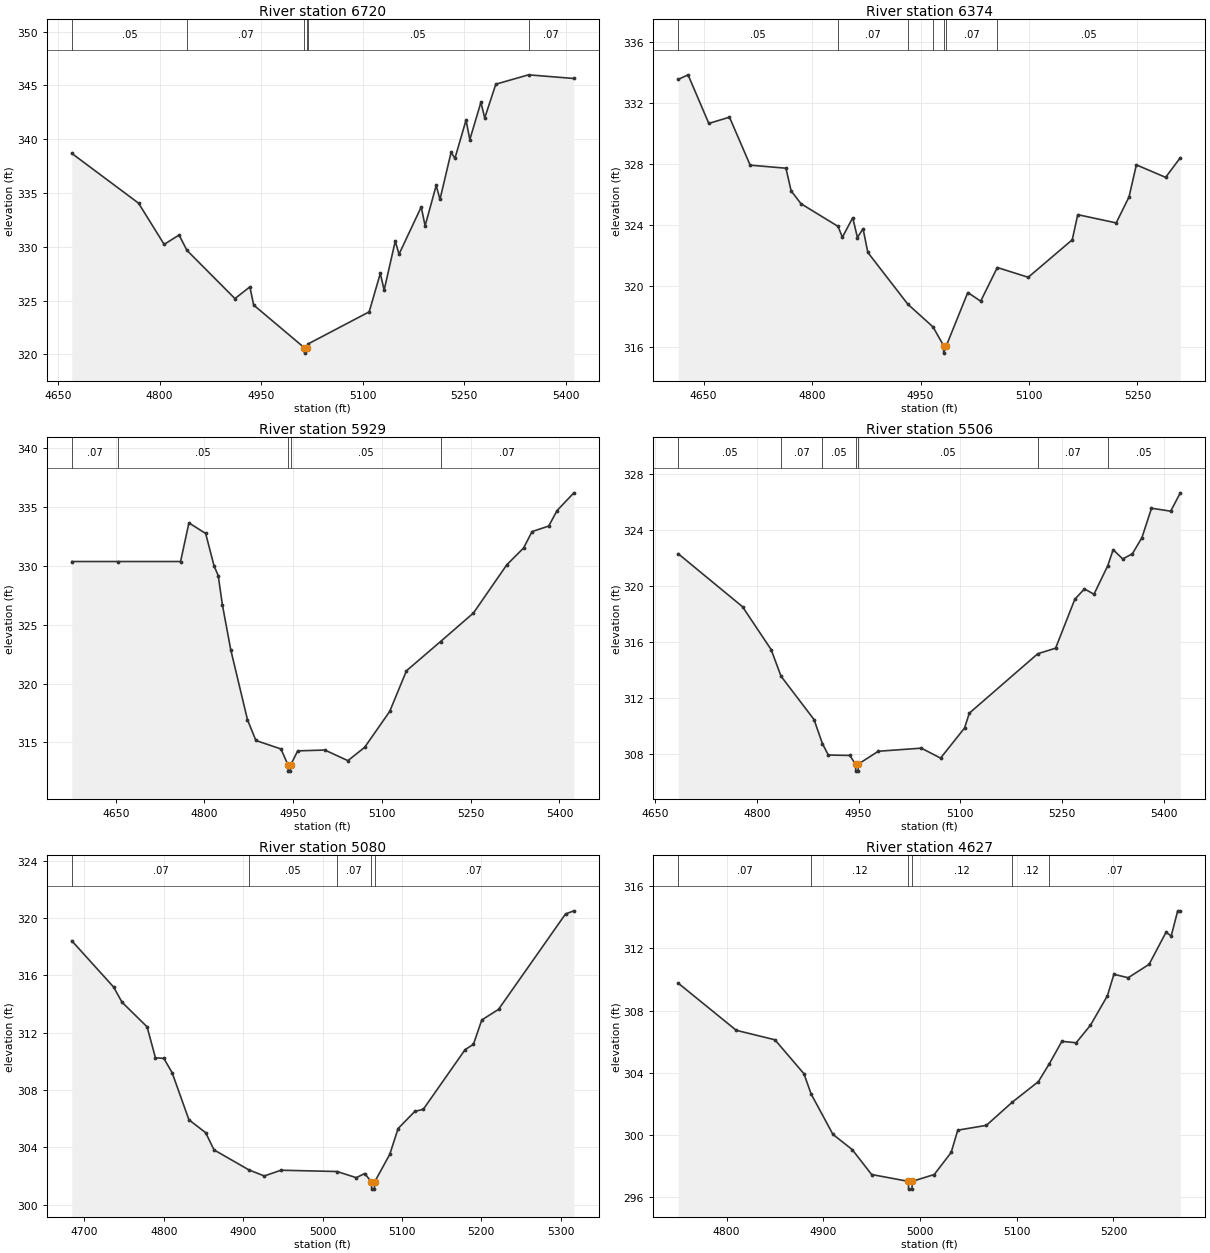
Type RM Length L Ch R = 1,6720,346,346,346
BEGIN DESCRIPTION:
XS7770
END DESCRIPTION:
XS GIS Cut Line= 2
      2450302.38     13603242.71      2449645.61     13602897.63
#Sta/Elev= 30
  4670.3  338.69  4769.0  334.06  4806.8  330.23  4828.9  331.10  4840.4  329.68
  4911.4  325.19  4933.5  326.28  4939.1  324.59  5014.0  320.62  5014.2  320.12
  5018.0  320.62  5019.4  320.97  5109.8  323.96  5126.2  327.53  5131.9  325.98
  5148.3  330.53  5153.9  329.32  5186.7  333.71  5192.4  331.95  5208.8  335.71
  5214.4  334.41  5230.8  338.78  5236.5  338.23  5252.9  341.78  5258.5  339.97
  5274.9  343.44  5280.5  341.98  5296.9  345.12  5345.2  345.99  5412.2  345.65
#Mann=6,-1,0
  4670.3    0.05       0  4840.4    0.07       0  5014.0    0.05       0
  5018.0    0.07       0  5019.4    0.05       0  5345.2    0.07       0
Bank Sta=5014,5018
Exp/Cntr=0.3,0.1

Type RM Length L Ch R = 1,6374,445,445,445
BEGIN DESCRIPTION:
Stream0815 14.0
END DESCRIPTION:
XS GIS Cut Line= 3
      2450374.97     13603074.97      2450125.00     13602775.00
      2449825.01     13602825.00
#Sta/Elev= 30
  4614.8  333.57  4628.4  333.87  4657.1  330.68  4685.7  331.09  4714.3  327.94
  4763.8  327.74  4771.0  326.25  4784.6  325.41  4835.9  323.92  4841.9  323.21
  4856.2  324.49  4862.7  323.19  4870.5  323.77  4877.1  322.21  4932.3  318.82
  4967.3  317.32  4981.8  316.10  4982.0  315.60  4985.8  316.10  5015.4  319.58
  5033.2  319.01  5056.2  321.22  5099.0  320.58  5159.9  323.04  5167.5  324.69
  5220.7  324.15  5238.4  325.85  5248.6  327.96  5289.1  327.14  5309.4  328.43
#Mann=7,-1,0
  4614.8    0.05       0  4835.9    0.07       0  4932.3    0.05       0
  4967.3    0.07       0  4981.8    0.05       0  4985.8    0.07       0
  5056.2    0.05       0
Bank Sta=4981.8,4985.8
Exp/Cntr=0.3,0.1

Type RM Length L Ch R = 1,5929,423,423,423
BEGIN DESCRIPTION:
Stream0815 13.0
END DESCRIPTION:
XS GIS Cut Line= 3
      2450725.03     13602775.03      2450425.00     13602475.00
      2450124.98     13602174.98
#Sta/Elev= 30
  4575.7  330.36  4654.5  330.36  4759.6  330.36  4773.7  333.64  4802.0  332.74
  4816.2  329.99  4823.2  329.17  4830.3  326.68  4844.4  322.87  4872.7  316.93
  4886.9  315.17  4929.3  314.45  4941.4  313.07  4941.7  312.57  4945.2  312.57
  4945.4  313.07  4957.6  314.29  5003.5  314.36  5042.4  313.46  5070.7  314.59
  5113.1  317.64  5141.4  321.09  5199.0  323.57  5254.6  325.99  5311.1  330.09
  5339.4  331.51  5353.6  332.90  5381.8  333.37  5396.0  334.69  5424.3  336.19
#Mann=5,-1,0
  4575.7    0.07       0  4654.5    0.05       0  4941.4    0.05       0
  4945.4    0.05       0  5199.0    0.07       0
Bank Sta=4941.4,4945.4
Exp/Cntr=0.3,0.1

Type RM Length L Ch R = 1,5506,426,426,426
BEGIN DESCRIPTION:
Stream0815 12.0
END DESCRIPTION:
XS GIS Cut Line= 3
      2450874.99     13602574.98      2450775.00     13602275.00
      2450474.98     13601974.98
#Sta/Elev= 30
  4684.1  322.28  4778.9  318.50  4821.1  315.44  4835.7  313.54  4884.4  310.44
  4896.7  308.73  4905.4  307.91  4937.1  307.88  4945.6  307.26  4945.9  306.76
  4949.4  306.76  4949.6  307.26  4979.2  308.18  5042.7  308.40  5071.0  307.69
  5106.4  309.84  5113.4  310.90  5214.3  315.14  5240.7  315.54  5269.0  319.03
  5283.2  319.77  5297.3  319.39  5317.6  321.43  5325.6  322.57  5339.7  321.91
  5353.9  322.28  5368.0  323.43  5382.1  325.53  5410.4  325.32  5424.6  326.63
#Mann=7,-1,0
  4684.1    0.05       0  4835.7    0.07       0  4896.7    0.05       0
  4945.6    0.05       0  4949.6    0.05       0  5214.3    0.07       0
  5317.6    0.05       0
Bank Sta=4945.6,4949.6
Exp/Cntr=0.3,0.1

Type RM Length L Ch R = 1,5080,453,453,453
BEGIN DESCRIPTION:
Stream0815 11.0
END DESCRIPTION:
XS GIS Cut Line= 3
      2451225.01     13602375.04      2451125.00     13602075.00
      2451025.00     13601774.99
#Sta/Elev= 30
  4684.1  318.42  4736.8  315.19  4747.4  314.13  4779.0  312.41  4789.5  310.25
  4800.1  310.21  4810.6  309.20  4831.7  305.92  4852.8  305.02  4863.3  303.82
  4907.3  302.42  4926.6  302.00  4947.7  302.40  5018.3  302.31  5042.5  301.88
  5053.1  302.17  5061.6  301.58  5061.9  301.08  5065.4  301.08  5065.6  301.58
  5084.7  303.51  5095.2  305.31  5116.3  306.51  5126.9  306.65  5179.6  310.82
  5190.1  311.19  5200.6  312.89  5221.7  313.63  5306.1  320.29  5316.6  320.51
#Mann=5,-1,0
  4684.1    0.07       0  4907.3    0.05       0  5018.3    0.07       0
  5061.6    0.05       0  5065.6    0.07       0
Bank Sta=5061.6,5065.6
Exp/Cntr=0.3,0.1

Type RM Length L Ch R = 1,4627,298,298,298
BEGIN DESCRIPTION:
Stream0815 10.0
END DESCRIPTION:
XS GIS Cut Line= 3
      2451525.00     13602175.02      2451525.00     13601925.00
      2451625.01     13601674.98
#Sta/Elev= 30
  4749.9  309.77  4809.9  306.74  4849.9  306.13  4879.9  303.95  4887.4  302.64
  4909.9  300.05  4929.9  299.07  4949.9  297.47  4987.9  297.03  4988.2  296.53
  4991.7  296.53  4991.9  297.03  5014.7  297.47  5032.2  298.89  5039.0  300.32
  5068.6  300.63  5095.4  302.12  5122.4  303.44  5133.8  304.60  5146.7  306.03
  5161.5  305.94  5176.3  307.07  5193.8  308.96  5200.5  310.34  5215.3  310.12
  5236.9  310.98  5254.4  313.04  5259.8  312.81  5266.5  314.42  5269.2  314.42
#Mann=6,-1,0
  4749.9    0.07       0  4887.4    0.12       0  4987.9    0.05       0
  4991.9    0.12       0  5095.4    0.12       0  5133.8    0.07       0
Bank Sta=4987.9,4991.9
Exp/Cntr=0.3,0.1

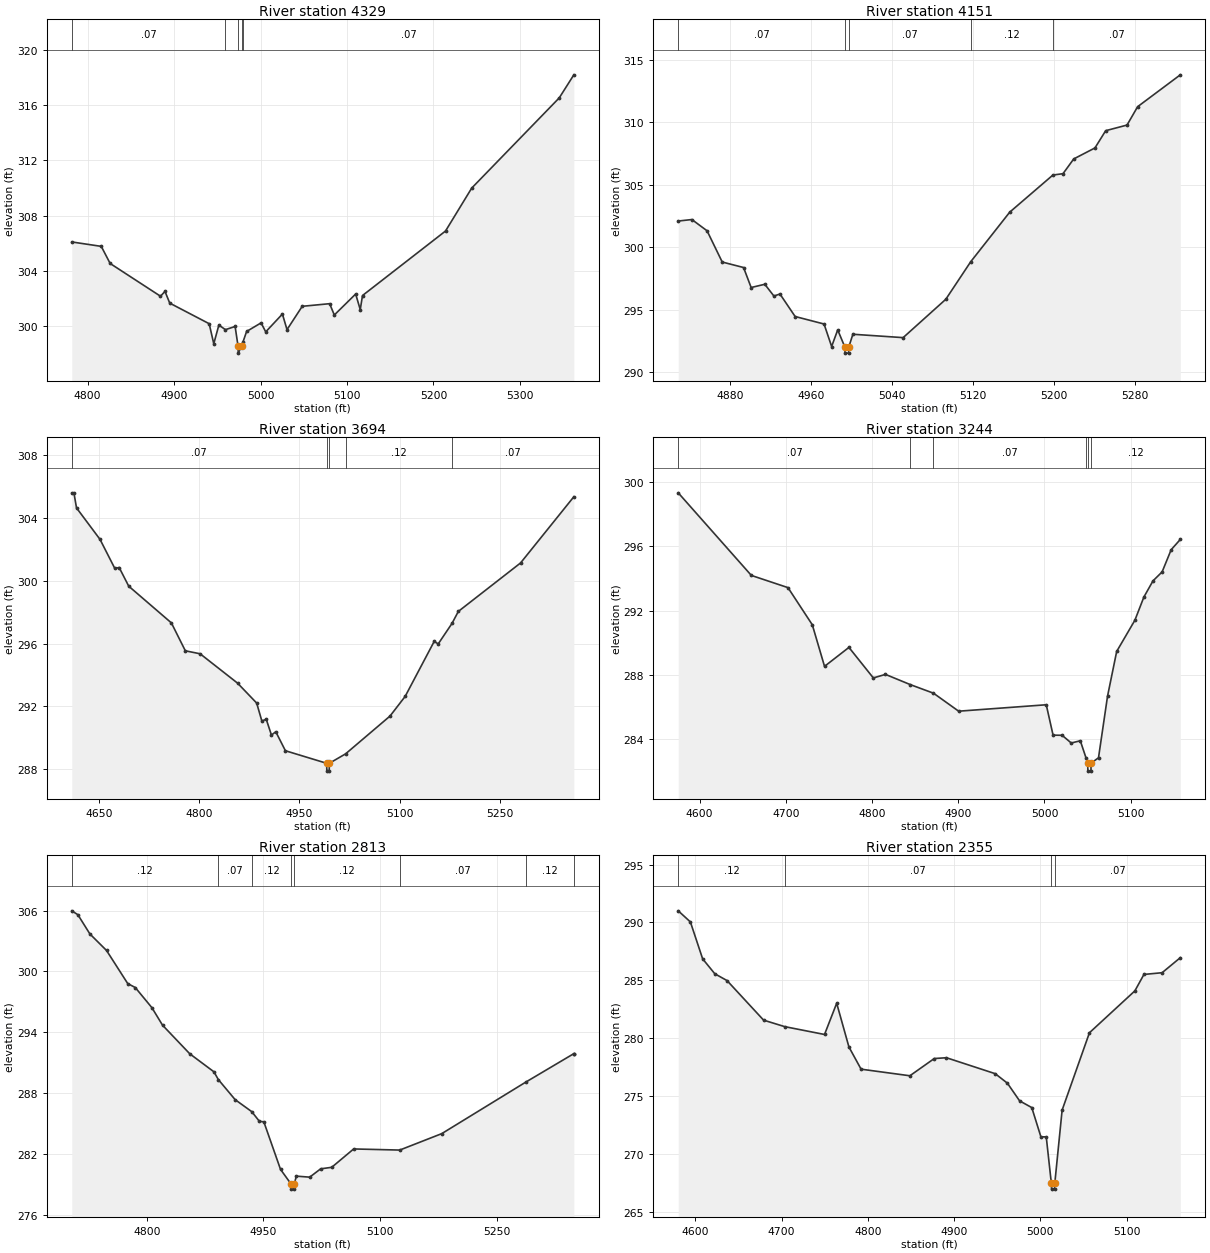
Type RM Length L Ch R = 1,4329,178,178,178
BEGIN DESCRIPTION:
Stream0815 10.0a
END DESCRIPTION:
XS GIS Cut Line= 4
      2451874.70     13602168.13      2451847.37     13602056.06
      2451768.14     13601849.78      2451731.50     13601608.27
#Sta/Elev= 30
  4781.7  306.10  4815.8  305.78  4826.1  304.54  4884.3  302.17  4889.5  302.52
  4895.0  301.67  4940.6  300.18  4945.9  298.73  4951.8  300.08  4959.4  299.75
  4970.6  299.98  4974.0  298.55  4974.2  298.05  4978.0  298.55  4979.7  298.86
  4983.9  299.62  5000.6  300.24  5006.0  299.59  5025.3  300.88  5030.6  299.75
  5048.2  301.44  5079.9  301.63  5085.3  300.81  5110.0  302.33  5115.3  301.20
  5117.9  302.22  5213.9  306.89  5244.2  310.00  5345.4  316.53  5362.3  318.20
#Mann=5,-1,0
  4781.7    0.07       0  4959.4    0.12       0  4974.0    0.05       0
  4978.0    0.12       0  4979.7    0.07       0
Bank Sta=4974,4978
Exp/Cntr=0.3,0.1

Type RM Length L Ch R = 1,4151,457,457,457
BEGIN DESCRIPTION:
Stream0815 9.0
END DESCRIPTION:
XS GIS Cut Line= 3
      2451875.02     13602074.97      2451975.00     13601925.00
      2451874.99     13601624.97
#Sta/Elev= 30
  4828.7  302.09  4842.2  302.21  4857.2  301.31  4872.2  298.81  4893.3  298.37
  4900.8  296.77  4914.3  297.03  4923.3  296.09  4929.3  296.25  4944.3  294.45
  4972.9  293.85  4980.4  292.05  4986.4  293.38  4993.4  292.02  4993.7  291.52
  4997.2  291.52  4997.4  292.02  5001.4  293.03  5051.1  292.76  5093.3  295.83
  5117.9  298.83  5156.5  302.80  5199.2  305.77  5209.2  305.88  5219.8  307.06
  5240.8  307.94  5251.4  309.32  5272.5  309.77  5283.0  311.24  5325.2  313.79
#Mann=5,-1,0
  4828.7    0.07       0  4993.4    0.05       0  4997.4    0.07       0
  5117.9    0.12       0  5199.2    0.07       0
Bank Sta=4993.4,4997.4
Exp/Cntr=0.3,0.1

Type RM Length L Ch R = 1,3694,450,450,450
BEGIN DESCRIPTION:
Stream0815 8.0
END DESCRIPTION:
XS GIS Cut Line= 3
      2452175.01     13602224.99      2452425.00     13601925.00
      2452224.97     13601624.96
#Sta/Elev= 30
  4609.4  305.61  4612.6  305.61  4616.5  304.65  4651.7  302.64  4673.8  300.79
  4680.3  300.85  4694.6  299.66  4758.4  297.32  4779.3  295.54  4801.4  295.35
  4857.4  293.48  4886.0  292.21  4893.8  291.06  4900.3  291.18  4908.1  290.17
  4914.6  290.38  4929.0  289.17  4990.7  288.37  4991.0  287.87  4994.5  287.87
  4994.7  288.37  5019.0  288.97  5085.5  291.38  5108.1  292.63  5151.6  296.14
  5157.6  295.98  5178.3  297.29  5187.7  298.05  5280.8  301.14  5360.5  305.36
#Mann=5,-1,0
  4609.4    0.07       0  4990.7    0.05       0  4994.7    0.07       0
  5019.0    0.12       0  5178.3    0.07       0
Bank Sta=4990.7,4994.7
Exp/Cntr=0.3,0.1

Type RM Length L Ch R = 1,3244,431,431,431
BEGIN DESCRIPTION:
Stream0815 7.0
END DESCRIPTION:
XS GIS Cut Line= 3
      2452525.01     13602374.99      2452825.00     13602075.00
      2452875.01     13601924.96
#Sta/Elev= 30
  4575.2  299.33  4660.0  294.19  4702.5  293.43  4730.7  291.12  4744.9  288.53
  4773.2  289.71  4801.5  287.81  4815.6  288.03  4844.6  287.39  4871.3  286.86
  4900.5  285.74  5002.1  286.14  5010.0  284.25  5020.5  284.24  5031.1  283.76
  5041.6  283.90  5048.3  282.82  5050.2  282.51  5050.4  282.01  5053.9  282.01
  5054.2  282.51  5062.7  282.84  5073.2  286.68  5083.8  289.46  5104.9  291.40
  5115.4  292.85  5125.9  293.85  5136.5  294.41  5147.0  295.79  5157.6  296.43
#Mann=6,-1,0
  4575.2    0.07       0  4844.6    0.12       0  4871.3    0.07       0
  5048.3    0.12       0  5050.2    0.05       0  5054.2    0.12       0
Bank Sta=5050.2,5054.2
Exp/Cntr=0.3,0.1

Type RM Length L Ch R = 1,2813,458,458,458
BEGIN DESCRIPTION:
Stream0815 6.0
END DESCRIPTION:
XS GIS Cut Line= 3
      2452675.01     13602624.99      2452925.00     13602475.00
      2453175.01     13602224.99
#Sta/Elev= 30
  4703.7  305.97  4711.5  305.59  4727.0  303.69  4748.4  302.06  4775.6  298.80
  4785.3  298.41  4806.7  296.42  4820.3  294.70  4855.3  291.88  4886.4  290.10
  4892.0  289.34  4913.6  287.36  4934.9  286.18  4944.7  285.23  4950.5  285.17
  4971.9  280.49  4985.5  279.04  4985.7  278.54  4989.2  278.54  4989.5  279.04
  4992.3  279.82  5009.4  279.72  5023.5  280.54  5037.7  280.69  5065.9  282.50
  5125.1  282.39  5179.1  284.01  5287.3  289.10  5348.7  291.89  5348.8  291.89
#Mann=8,-1,0
  4703.7    0.12       0  4892.0    0.07       0  4934.9    0.12       0
  4985.5    0.05       0  4989.5    0.12       0  5125.1    0.07       0
  5287.3    0.12       0  5348.7    0.07       0
Bank Sta=4985.5,4989.5
Exp/Cntr=0.3,0.1

Type RM Length L Ch R = 1,2355,450,450,450
BEGIN DESCRIPTION:
Stream0815 5.0
END DESCRIPTION:
XS GIS Cut Line= 3
      2453025.00     13602925.00      2453325.00     13602625.00
      2453375.01     13602474.98
#Sta/Elev= 30
  4580.0  291.00  4594.1  290.04  4608.3  286.85  4622.4  285.56  4636.6  284.97
  4679.0  281.55  4703.4  280.99  4749.7  280.31  4763.8  283.01  4778.0  279.23
  4792.1  277.31  4848.7  276.74  4877.0  278.23  4891.1  278.30  4947.7  276.92
  4961.8  276.10  4976.0  274.57  4990.1  273.99  5000.7  271.46  5006.9  271.46
  5012.8  267.44  5013.1  266.94  5016.6  266.94  5016.8  267.44  5025.3  273.77
  5057.0  280.46  5109.7  284.08  5120.2  285.50  5141.3  285.65  5162.4  286.95
#Mann=4,-1,0
  4580.0    0.12       0  4703.4    0.07       0  5012.8    0.05       0
  5016.8    0.07       0
Bank Sta=5012.8,5016.8
Exp/Cntr=0.3,0.1

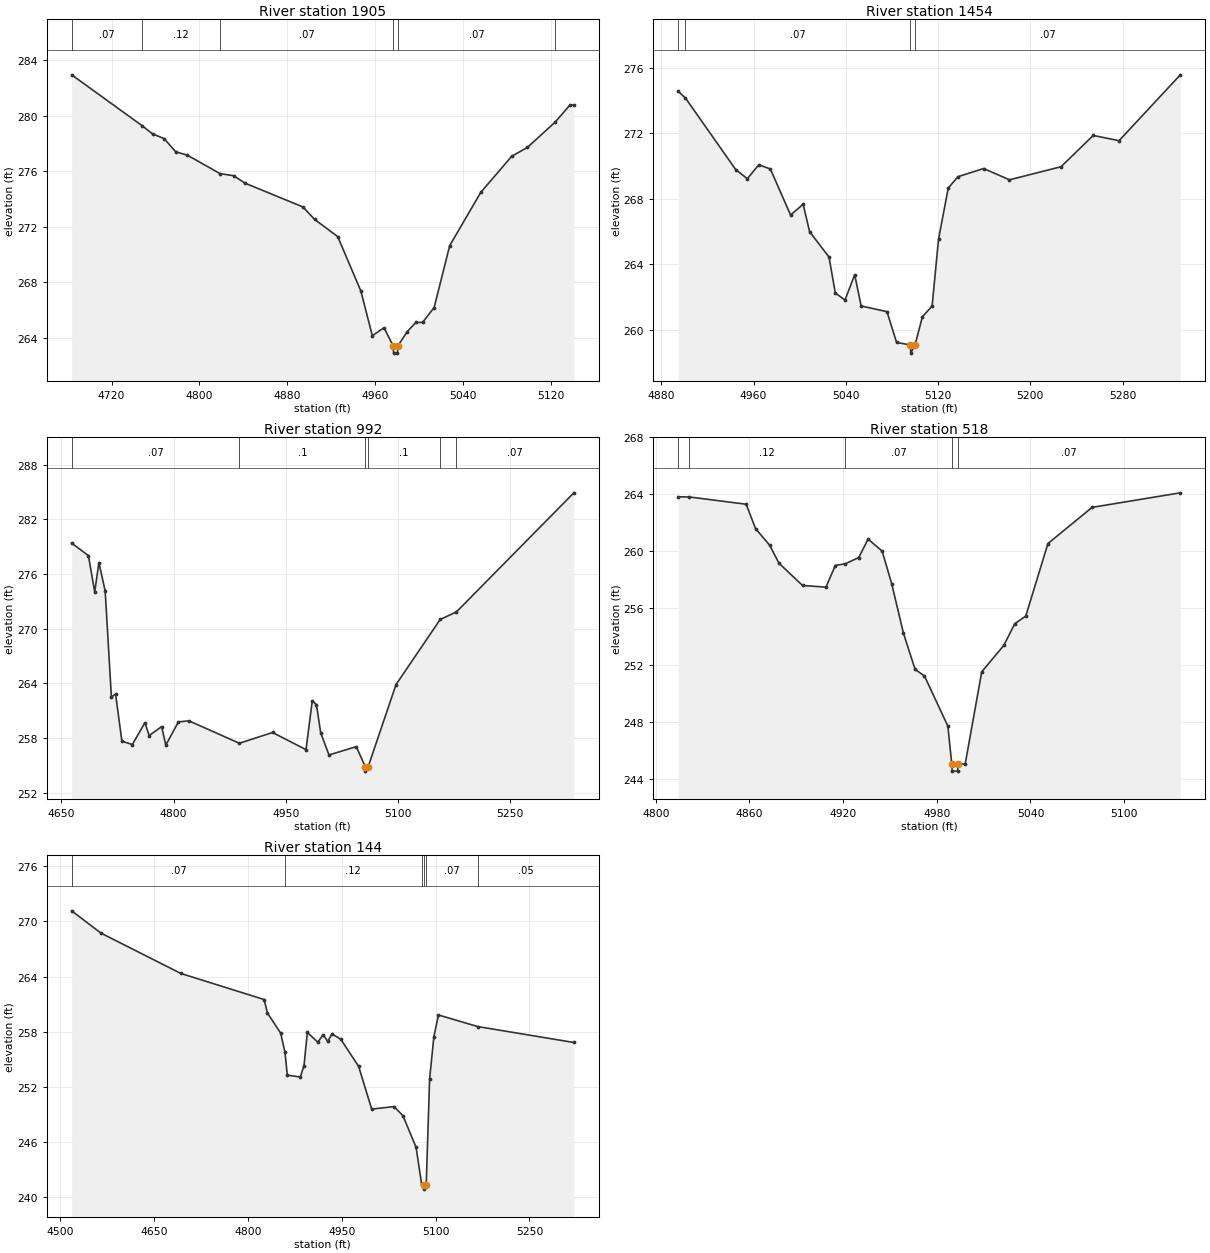
Type RM Length L Ch R = 1,1905,451,451,451
BEGIN DESCRIPTION:
Stream0815 4.0
END DESCRIPTION:
XS GIS Cut Line= 3
      2453275.04     13603074.99      2453575.00     13602975.00
      2453674.99     13602875.01
#Sta/Elev= 30
  4683.6  282.94  4748.0  279.27  4757.3  278.69  4767.9  278.35  4778.4  277.40
  4789.0  277.16  4818.8  275.83  4831.1  275.68  4841.7  275.14  4894.4  273.43
  4904.9  272.54  4926.0  271.30  4947.1  267.39  4957.6  264.16  4968.2  264.74
  4976.7  263.41  4977.0  262.91  4980.5  262.91  4980.7  263.41  4989.2  264.44
  4997.2  265.12  5003.3  265.12  5013.9  266.19  5028.1  270.65  5056.4  274.48
  5084.6  277.08  5098.8  277.71  5124.1  279.53  5137.7  280.77  5141.2  280.77
#Mann=6,-1,0
  4683.6    0.07       0  4748.0    0.12       0  4818.8    0.07       0
  4976.7    0.05       0  4980.7    0.07       0  5124.1   0.035       0
Bank Sta=4976.7,4980.7
Exp/Cntr=0.3,0.1

Type RM Length L Ch R = 1,1454,462,462,462
BEGIN DESCRIPTION:
Stream0815 3.0
END DESCRIPTION:
XS GIS Cut Line= 3
      2453625.00     13603375.00      2453725.00     13603375.00
      2453874.99     13603075.01
#Sta/Elev= 30
  4894.6  274.57  4901.0  274.15  4944.6  269.78  4954.6  269.23  4964.6  270.08
  4974.6  269.82  4992.1  267.01  5003.0  267.67  5008.6  265.99  5025.4  264.45
  5030.9  262.25  5039.3  261.82  5047.7  263.37  5053.3  261.46  5075.7  261.11
  5084.0  259.23  5096.0  259.08  5096.3  258.58  5100.0  259.08  5106.4  260.80
  5114.8  261.45  5120.4  265.54  5128.8  268.66  5137.2  269.35  5159.5  269.85
  5181.9  269.16  5226.6  269.96  5254.5  271.87  5276.9  271.55  5330.0  275.57
#Mann=4,-1,0
  4894.6    0.12       0  4901.0    0.07       0  5096.0    0.05       0
  5100.0    0.07       0
Bank Sta=5096,5100
Exp/Cntr=0.3,0.1

Type RM Length L Ch R = 1,992,474,474,474
BEGIN DESCRIPTION:
Stream0815 2.0
END DESCRIPTION:
XS GIS Cut Line= 3
      2453874.98     13603675.04      2454025.00     13603375.00
      2454175.02     13603074.97
#Sta/Elev= 30
  4663.9  279.40  4686.3  278.03  4694.7  274.05  4700.3  277.25  4708.7  274.15
  4717.0  262.51  4722.6  262.84  4731.0  257.67  4745.0  257.30  4761.8  259.70
  4767.4  258.28  4784.1  259.27  4789.7  257.24  4806.5  259.78  4820.5  259.90
  4888.0  257.44  4932.3  258.62  4977.0  256.74  4985.4  262.11  4991.0  261.67
  4996.6  258.59  5007.7  256.15  5044.1  257.07  5056.1  254.88  5056.3  254.38
  5060.1  254.88  5097.2  263.87  5156.2  271.02  5177.9  271.85  5334.8  284.92
#Mann=6,-1,0
  4663.9    0.07       0  4888.0     0.1       0  5056.1    0.05       0
  5060.1     0.1       0  5156.2    0.12       0  5177.9    0.07       0
Bank Sta=5056.1,5060.1
Exp/Cntr=0.3,0.1

Type RM Length L Ch R = 1,518,374,374,374
BEGIN DESCRIPTION:
Stream0815 1.0
END DESCRIPTION:
XS GIS Cut Line= 3
      2454274.96     13603625.03      2454425.00     13603525.00
      2454524.97     13603425.03
#Sta/Elev= 30
  4814.3  263.82  4821.4  263.81  4857.9  263.30  4863.9  261.59  4872.9  260.43
  4878.9  259.16  4894.0  257.60  4909.0  257.48  4915.0  259.00  4921.4  259.12
  4930.0  259.56  4936.0  260.85  4945.0  260.01  4951.1  257.73  4958.6  254.27
  4966.1  251.71  4972.1  251.25  4987.1  247.73  4989.6  245.07  4989.9  244.57
  4993.4  244.57  4993.6  245.07  4998.2  245.07  5008.8  251.54  5022.9  253.39
  5030.0  254.92  5037.0  255.45  5051.2  260.54  5079.5  263.08  5136.0  264.10
#Mann=5,-1,0
  4814.3    0.07       0  4821.4    0.12       0  4921.4    0.07       0
  4989.6    0.05       0  4993.6    0.07       0
Bank Sta=4989.6,4993.6
Exp/Cntr=0.3,0.1

Type RM Length L Ch R = 1,144,0,0,0
BEGIN DESCRIPTION:
XS7769
END DESCRIPTION:
XS GIS Cut Line= 3
      2454207.38     13603955.27      2454583.37     13603832.78
      2454885.55     13603559.45
#Sta/Elev= 30
  4518.0  271.15  4565.1  268.72  4692.7  264.34  4825.7  261.51  4831.0  260.05
  4852.1  257.86  4859.1  255.77  4862.8  253.29  4883.6  253.09  4889.5  254.32
  4894.8  257.93  4911.7  256.87  4920.0  257.68  4927.4  256.96  4934.2  257.78
  4948.4  257.18  4976.8  254.24  4997.7  249.60  5033.5  249.87  5047.7  248.88
  5068.7  245.44  5077.4  241.50  5080.9  241.40  5081.1  240.90  5084.9  241.40
  5090.3  252.86  5097.1  257.45  5104.4  259.83  5167.2  258.57  5320.9  256.84
#Mann=6,-1,0
  4518.0    0.07       0  4859.1    0.12       0  5077.4    0.07       0
  5080.9    0.05       0  5084.9    0.07       0  5167.2    0.05       0
Bank Sta=5080.9,5084.9
Exp/Cntr=0.3,0.1

Chan Stop Cuts=-1