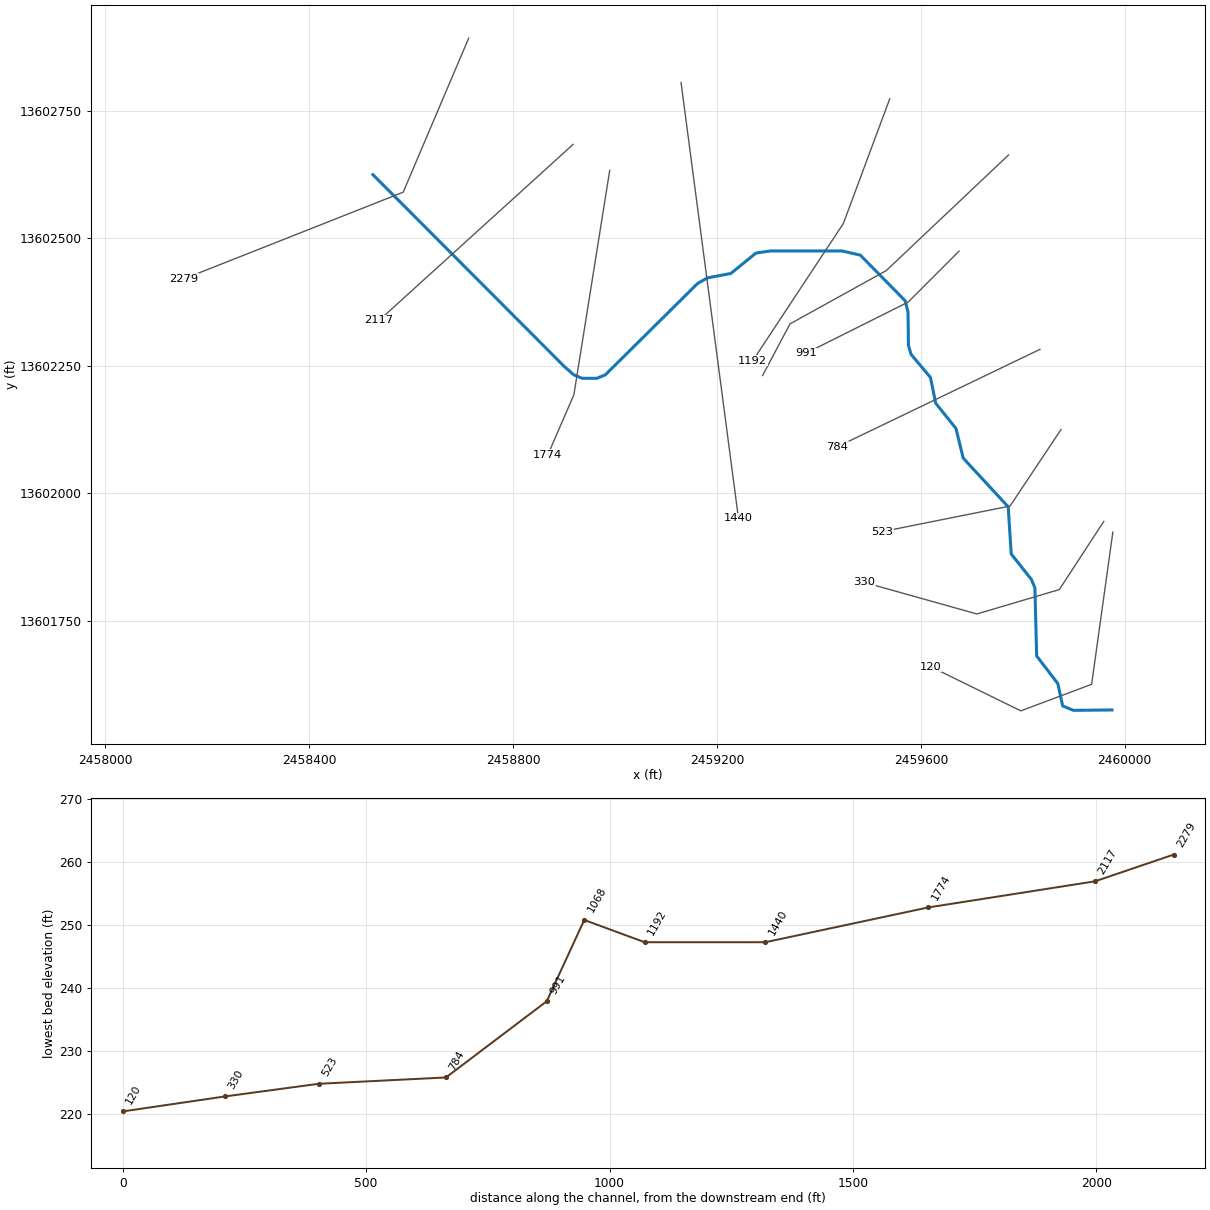
--- Stream0816.prj (project) ---

Proj Title=Stream0816 Base Level Engineering
Current Plan=p01
Default Exp/Contr=0.3,0.1
English Units
Geom File=g01
Flow File=f01
Plan File=p01
BEGIN DESCRIPTION:
Stream0816
END DESCRIPTION:

--- Stream0816.p01 (plan) ---

Plan Title=Multiple Run
Short Identifier=Multiple
Geom File=g01
Flow File=f01
Subcritical Flow
K Sum by GR= 0
Std Step Tol= 0.01
Critical Tol= 0.01
Num of Std Step Trials= 20
Max Error Tol= 0.3
Flow Tol Ratio= 0.001
Split Flow NTrial= 30
Split Flow Tol= 0.02
Split Flow Ratio= 0.02
Log Output Level= 0
Friction Slope Method= 1
Unsteady Friction Slope Method= 2
Unsteady Bridges Friction Slope Method= 1
Parabolic Critical Depth
Global Vel Dist=  1 , 1 , 1
Global Log Level= 0
CheckData=True
Encroach Param= -1, 0, 0, 0
BEGIN DESCRIPTION:
Multiple Run
END DESCRIPTION:

--- Stream0816.f01 (steady flow) ---

Flow Title=Multiple
Number of Profiles=7
Profile Names=10-year,25-year,50-year,1pct_min,100-year,1pct_plu,500-year
River Rch & RM= Stream0816,Reach-1,2279
     243     372     483     306     610    1217     959
Boundary for River Rch & Prof#=Stream0816,Reach-1,1
Up Type=0
Dn Type=3
Dn Slope=0.005
Boundary for River Rch & Prof#=Stream0816,Reach-1,2
Up Type=0
Dn Type=3
Dn Slope=0.005
Boundary for River Rch & Prof#=Stream0816,Reach-1,3
Up Type=0
Dn Type=3
Dn Slope=0.005
Boundary for River Rch & Prof#=Stream0816,Reach-1,4
Up Type=0
Dn Type=3
Dn Slope=0.005
Boundary for River Rch & Prof#=Stream0816,Reach-1,5
Up Type=0
Dn Type=3
Dn Slope=0.005
Boundary for River Rch & Prof#=Stream0816,Reach-1,6
Up Type=0
Dn Type=3
Dn Slope=0.005
Boundary for River Rch & Prof#=Stream0816,Reach-1,7
Up Type=0
Dn Type=3
Dn Slope=0.005

--- Stream0816.g01 (geometry) ---

Geom Title=Existing Conditions

River Reach=Stream0816,Reach-1
Reach XY= 30
      2458525.00     13602625.00      2458901.53     13602247.70
      2458918.95     13602232.46      2458935.64     13602225.55
      2458964.36     13602225.55      2458981.05     13602232.46
      2459161.78     13602411.38      2459181.03     13602422.50
      2459227.17     13602431.14      2459276.55     13602471.25
      2459304.85     13602475.37      2459445.18     13602475.44
      2459481.21     13602467.20      2459569.48     13602377.44
      2459574.88     13602354.95      2459575.65     13602290.27
      2459580.77     13602272.68      2459618.88     13602227.18
      2459629.16     13602176.72      2459668.90     13602127.19
      2459683.16     13602068.95      2459771.38     13601973.50
      2459777.36     13601880.98      2459816.86     13601831.06
      2459823.77     13601814.49      2459827.23     13601680.91
      2459868.74     13601626.81      2459878.27     13601582.97
      2459899.42     13601574.27      2459975.00     13601575.00

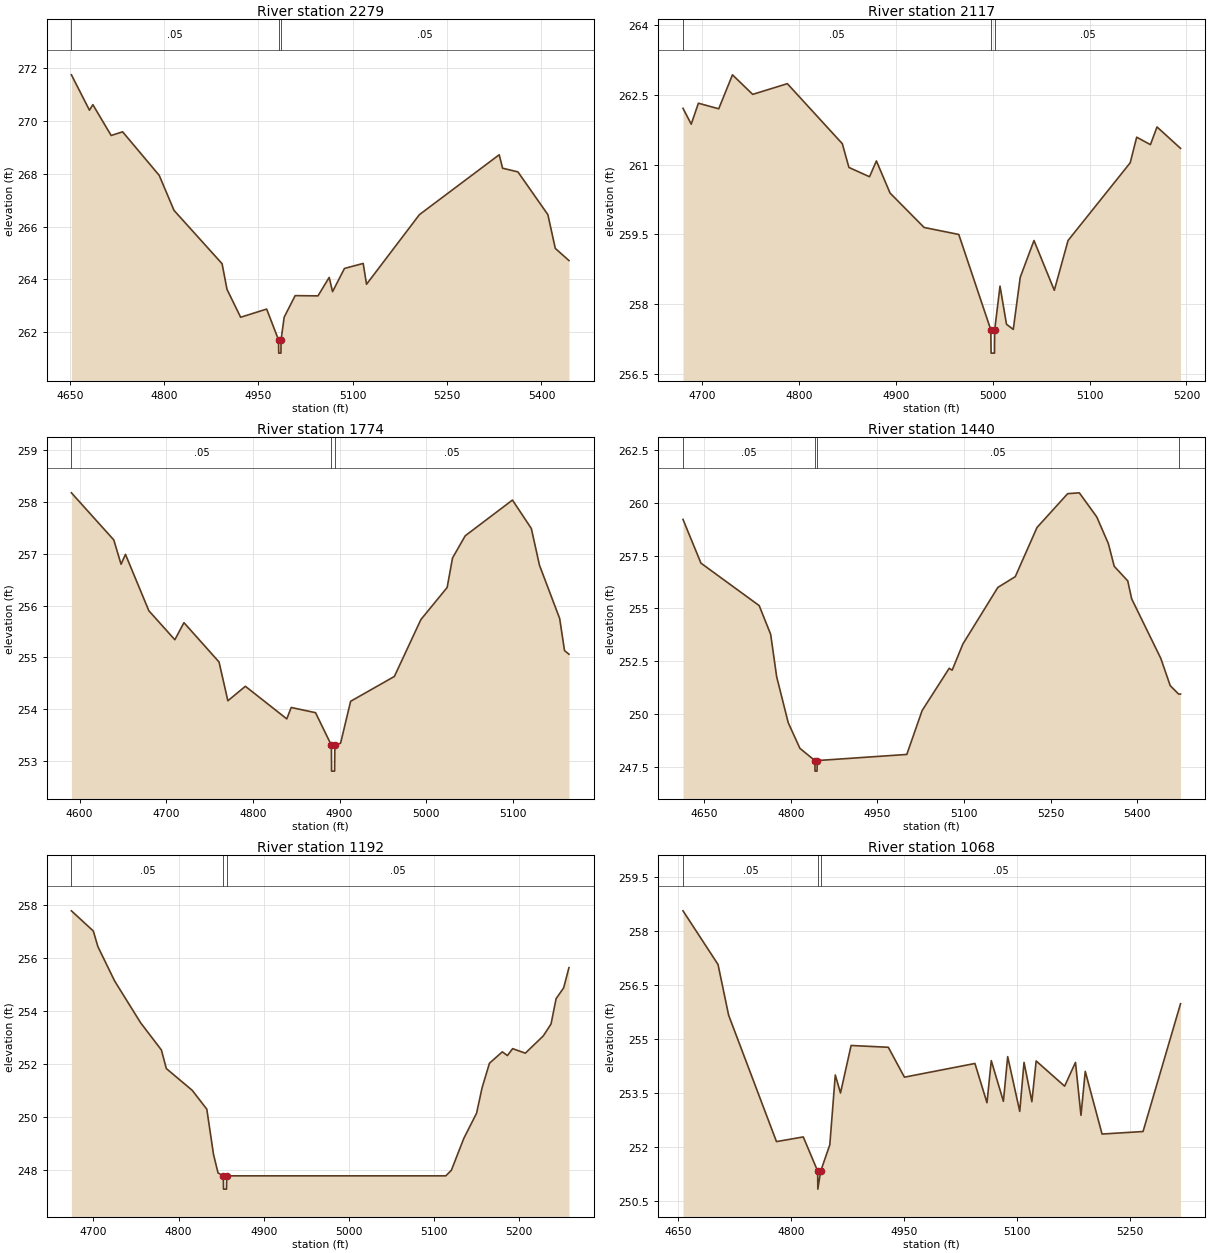
Type RM Length L Ch R = 1,2279,162,162,162
BEGIN DESCRIPTION:
XS7775
END DESCRIPTION:
XS GIS Cut Line= 3
      2458712.83     13602892.67      2458584.38     13602590.63
      2458153.80     13602420.48
#Sta/Elev= 30
  4652.5  271.75  4681.2  270.41  4686.6  270.62  4715.7  269.45  4733.9  269.59
  4792.1  267.94  4815.7  266.61  4892.1  264.59  4899.9  263.62  4921.6  262.56
  4963.0  262.87  4981.9  261.70  4982.2  261.20  4985.7  261.20  4985.9  261.70
  4990.8  262.56  5008.3  263.38  5044.6  263.37  5062.4  264.07  5067.8  263.53
  5086.7  264.41  5116.5  264.60  5121.8  263.81  5205.9  266.45  5332.8  268.72
  5338.2  268.21  5362.6  268.07  5410.2  266.45  5422.0  265.17  5443.7  264.71
#Mann=3,-1,0
  4652.5    0.05       0  4981.9    0.05       0  4985.9    0.05       0
Bank Sta=4981.9,4985.9
Exp/Cntr=0.3,0.1

Type RM Length L Ch R = 1,2117,343,343,343
BEGIN DESCRIPTION:
XS7774
END DESCRIPTION:
XS GIS Cut Line= 2
      2458917.74     13602684.40      2458537.02     13602339.07
#Sta/Elev= 30
  4679.9  262.21  4688.4  261.87  4695.8  262.32  4716.8  262.20  4731.0  262.93
  4751.9  262.51  4787.7  262.74  4844.5  261.45  4851.3  260.94  4872.6  260.74
  4879.7  261.08  4893.8  260.39  4929.0  259.65  4964.8  259.50  4997.9  257.45
  4998.2  256.95  5001.7  256.95  5001.9  257.45  5007.4  258.39  5014.1  257.57
  5021.1  257.46  5028.3  258.58  5042.5  259.37  5063.5  258.30  5077.7  259.37
  5141.9  261.04  5148.6  261.59  5162.8  261.43  5169.6  261.81  5193.9  261.35
#Mann=3,-1,0
  4679.9    0.05       0  4997.9    0.05       0  5001.9    0.05       0
Bank Sta=4997.9,5001.9
Exp/Cntr=0.3,0.1

Type RM Length L Ch R = 1,1774,334,334,334
BEGIN DESCRIPTION:
H21098
END DESCRIPTION:
XS GIS Cut Line= 3
      2458989.58     13602633.30      2458919.27     13602193.23
      2458868.05     13602075.22
#Sta/Elev= 30
  4590.5  258.18  4639.4  257.27  4647.8  256.80  4652.9  256.99  4679.9  255.90
  4709.9  255.34  4720.4  255.67  4760.9  254.91  4771.1  254.16  4791.3  254.44
  4839.1  253.81  4844.2  254.03  4872.3  253.93  4890.6  253.30  4890.8  252.80
  4894.3  252.80  4894.6  253.30  4901.2  253.34  4912.8  254.15  4963.3  254.63
  4993.9  255.73  5024.2  256.35  5030.4  256.92  5045.1  257.35  5099.6  258.04
  5121.4  257.49  5130.8  256.78  5154.1  255.75  5159.7  255.13  5164.8  255.06
#Mann=3,-1,0
  4590.5    0.05       0  4890.6    0.05       0  4894.6    0.05       0
Bank Sta=4890.6,4894.6
Exp/Cntr=0.3,0.1

Type RM Length L Ch R = 1,1440,248,248,248
BEGIN DESCRIPTION:
XS7773
END DESCRIPTION:
XS GIS Cut Line= 2
      2459129.52     13602805.88      2459242.18     13601951.07
#Sta/Elev= 30
  4613.0  259.21  4644.1  257.14  4745.0  255.13  4764.9  253.77  4775.3  251.76
  4795.4  249.58  4815.6  248.37  4841.5  247.79  4841.8  247.29  4845.3  247.29
  4845.5  247.79  5000.8  248.08  5027.4  250.16  5074.3  252.16  5079.4  252.07
  5098.0  253.31  5158.6  255.99  5188.8  256.50  5226.5  258.83  5279.6  260.43
  5299.8  260.47  5330.0  259.33  5350.2  258.06  5360.3  256.99  5383.7  256.30
  5390.5  255.45  5441.0  252.63  5457.3  251.34  5471.8  250.94  5475.2  250.94
#Mann=4,-1,0
  4613.0    0.05       0  4841.5    0.05       0  4845.5    0.05       0
  5471.8    0.07       0
Bank Sta=4841.5,4845.5
Exp/Cntr=0.3,0.1

Type RM Length L Ch R = 1,1192,124,124,124
BEGIN DESCRIPTION:
XS7772
END DESCRIPTION:
XS GIS Cut Line= 3
      2459539.05     13602773.94      2459447.92     13602529.17
      2459270.10     13602259.86
#Sta/Elev= 30
  4674.3  257.77  4700.0  257.01  4705.4  256.42  4725.0  255.13  4755.4  253.56
  4779.9  252.53  4785.7  251.83  4816.1  251.01  4833.2  250.30  4841.1  248.59
  4846.4  247.90  4852.6  247.79  4852.8  247.29  4856.3  247.29  4856.6  247.79
  5113.7  247.79  5120.2  248.00  5134.8  249.20  5149.8  250.15  5156.2  251.10
  5164.9  252.03  5180.0  252.46  5186.0  252.32  5192.1  252.58  5207.0  252.41
  5228.1  253.06  5237.2  253.51  5243.1  254.46  5252.0  254.87  5258.2  255.63
#Mann=3,-1,0
  4674.3    0.05       0  4852.6    0.05       0  4856.6    0.05       0
Bank Sta=4852.6,4856.6
Exp/Cntr=0.3,0.1

Type RM Length L Ch R = 1,1068,77,77,77
BEGIN DESCRIPTION:
XS7772a
END DESCRIPTION:
XS GIS Cut Line= 4
      2459772.00     13602663.58      2459532.06     13602436.79
      2459343.33     13602332.32      2459289.50     13602231.01
#Sta/Elev= 30
  4656.5  258.55  4703.0  257.06  4717.1  255.65  4780.6  252.14  4816.2  252.27
  4835.3  251.32  4835.5  250.82  4839.3  251.32  4851.4  252.05  4858.7  253.99
  4865.6  253.49  4879.7  254.81  4929.1  254.76  4950.5  253.93  5044.1  254.31
  5060.1  253.22  5065.8  254.39  5081.9  253.26  5087.6  254.50  5103.6  252.98
  5109.3  254.34  5119.7  253.25  5125.4  254.38  5163.2  253.68  5177.6  254.34
  5184.9  252.87  5190.6  254.09  5212.9  252.35  5267.3  252.42  5317.1  255.97
#Mann=3,-1,0
  4656.5    0.05       0  4835.3    0.05       0  4839.3    0.05       0
Bank Sta=4835.3,4839.3
Exp/Cntr=0.3,0.1

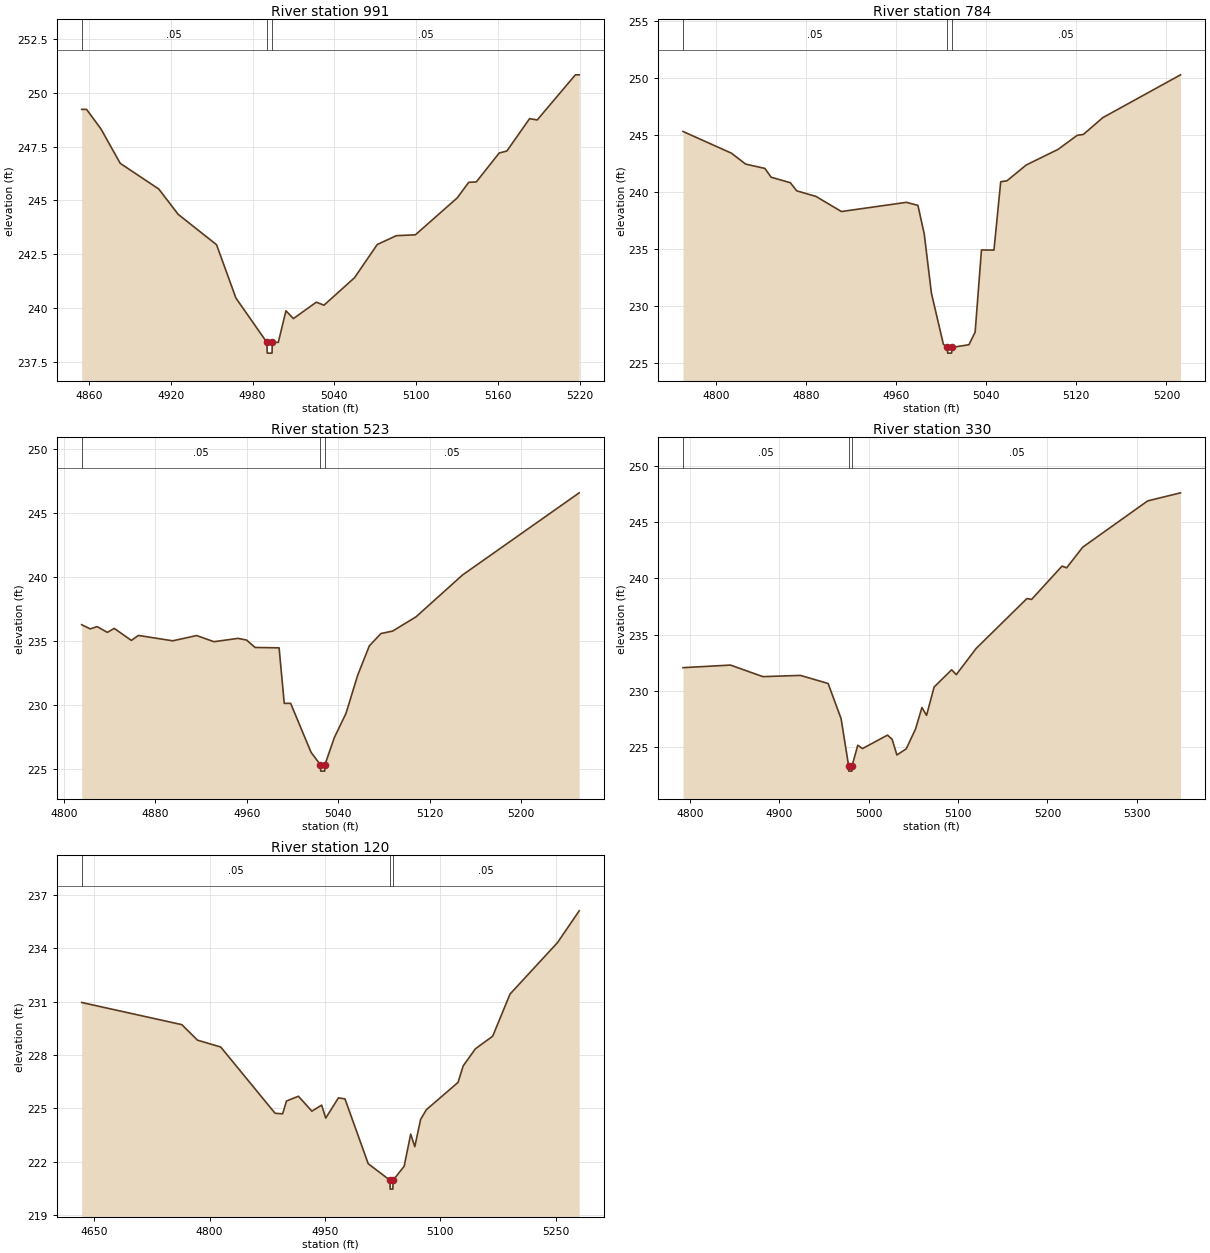
Type RM Length L Ch R = 1,991,207,207,207
BEGIN DESCRIPTION:
Stream0816 2.0
END DESCRIPTION:
XS GIS Cut Line= 3
      2459675.03     13602475.03      2459575.00     13602375.00
      2459374.98     13602274.99
#Sta/Elev= 30
  4854.6  249.22  4858.2  249.22  4868.8  248.31  4882.9  246.72  4911.2  245.53
  4925.4  244.36  4953.6  242.95  4967.8  240.48  4990.5  238.43  4990.8  237.93
  4994.3  237.93  4994.5  238.43  4998.9  238.43  5004.5  239.89  5010.0  239.53
  5026.8  240.29  5032.4  240.15  5054.8  241.42  5071.5  242.96  5085.5  243.37
  5099.5  243.41  5130.2  245.12  5138.6  245.84  5144.2  245.86  5161.0  247.20
  5166.6  247.29  5183.3  248.79  5188.9  248.73  5216.9  250.82  5219.7  250.82
#Mann=3,-1,0
  4854.6    0.05       0  4990.5    0.05       0  4994.5    0.05       0
Bank Sta=4990.5,4994.5
Exp/Cntr=0.3,0.1

Type RM Length L Ch R = 1,784,261,261,261
BEGIN DESCRIPTION:
H21097
END DESCRIPTION:
XS GIS Cut Line= 2
      2459833.72     13602282.34      2459435.70     13602091.06
#Sta/Elev= 30
  4770.9  245.33  4813.9  243.42  4826.5  242.46  4843.6  242.08  4849.1  241.31
  4866.2  240.82  4871.8  240.11  4888.9  239.62  4911.5  238.29  4969.2  239.10
  4979.4  238.83  4985.0  236.33  4991.4  231.11  5002.0  226.62  5005.6  226.34
  5005.8  225.84  5009.3  225.84  5009.6  226.34  5024.7  226.58  5030.2  227.69
  5035.8  234.91  5046.9  234.90  5052.9  240.91  5058.4  240.99  5075.5  242.38
  5103.7  243.75  5120.8  244.99  5126.3  245.07  5143.4  246.54  5212.5  250.31
#Mann=3,-1,0
  4770.9    0.05       0  5005.6    0.05       0  5009.6    0.05       0
Bank Sta=5005.6,5009.6
Exp/Cntr=0.3,0.1

Type RM Length L Ch R = 1,523,193,193,193
BEGIN DESCRIPTION:
Stream0816 1.0
END DESCRIPTION:
XS GIS Cut Line= 3
      2459874.99     13602124.98      2459775.00     13601975.00
      2459525.00     13601925.00
#Sta/Elev= 30
  4815.7  236.29  4823.2  235.96  4829.2  236.14  4838.2  235.69  4844.2  236.00
  4859.2  235.06  4865.3  235.45  4895.3  235.03  4916.3  235.44  4931.4  234.96
  4952.4  235.22  4959.9  235.09  4967.4  234.51  4988.4  234.48  4992.9  230.14
  4998.5  230.14  5016.3  226.32  5024.5  225.34  5024.8  224.84  5028.3  224.84
  5028.5  225.34  5036.7  227.46  5046.9  229.35  5057.1  232.33  5067.3  234.63
  5077.5  235.60  5087.7  235.79  5108.1  236.90  5148.9  240.18  5250.9  246.60
#Mann=3,-1,0
  4815.7    0.05       0  5024.5    0.05       0  5028.5    0.05       0
Bank Sta=5024.5,5028.5
Exp/Cntr=0.3,0.1

Type RM Length L Ch R = 1,330,210,210,210
BEGIN DESCRIPTION:
H21096
END DESCRIPTION:
XS GIS Cut Line= 4
      2459958.89     13601944.78      2459871.68     13601811.14
      2459709.93     13601763.32      2459489.56     13601825.08
#Sta/Elev= 30
  4792.0  232.05  4845.2  232.28  4881.4  231.25  4923.5  231.36  4954.5  230.64
  4969.0  227.51  4977.4  223.33  4977.6  222.83  4981.1  222.83  4981.4  223.33
  4987.7  225.14  4993.0  224.84  5021.0  226.04  5026.2  225.66  5031.5  224.27
  5042.0  224.82  5052.4  226.59  5059.5  228.50  5064.7  227.80  5073.2  230.33
  5092.8  231.86  5098.0  231.43  5120.2  233.76  5177.1  238.21  5182.3  238.13
  5216.4  241.10  5221.6  240.95  5239.6  242.79  5312.3  246.91  5349.1  247.63
#Mann=3,-1,0
  4792.0    0.05       0  4977.4    0.05       0  4981.4    0.05       0
Bank Sta=4977.4,4981.4
Exp/Cntr=0.3,0.1

Type RM Length L Ch R = 1,120,0,0,0
BEGIN DESCRIPTION:
XS7771
END DESCRIPTION:
XS GIS Cut Line= 4
      2459976.73     13601923.93      2459935.07     13601625.35
      2459796.18     13601573.26      2459619.66     13601659.80
#Sta/Elev= 30
  4633.9  230.96  4764.1  229.71  4784.3  228.84  4814.6  228.45  4885.2  224.72
  4895.0  224.69  4900.0  225.41  4915.5  225.68  4933.0  224.84  4945.7  225.18
  4951.0  224.45  4967.5  225.59  4976.0  225.53  5006.2  221.88  5034.5  220.95
  5034.7  220.45  5038.2  220.45  5038.5  220.95  5052.9  221.74  5061.4  223.55
  5066.7  222.84  5074.3  224.38  5081.7  224.92  5122.9  226.46  5129.6  227.39
  5145.4  228.35  5167.9  229.06  5190.4  231.43  5252.1  234.33  5280.3  236.12
#Mann=3,-1,0
  4633.9    0.05       0  5034.5    0.05       0  5038.5    0.05       0
Bank Sta=5034.5,5038.5
Exp/Cntr=0.3,0.1

Chan Stop Cuts=-1