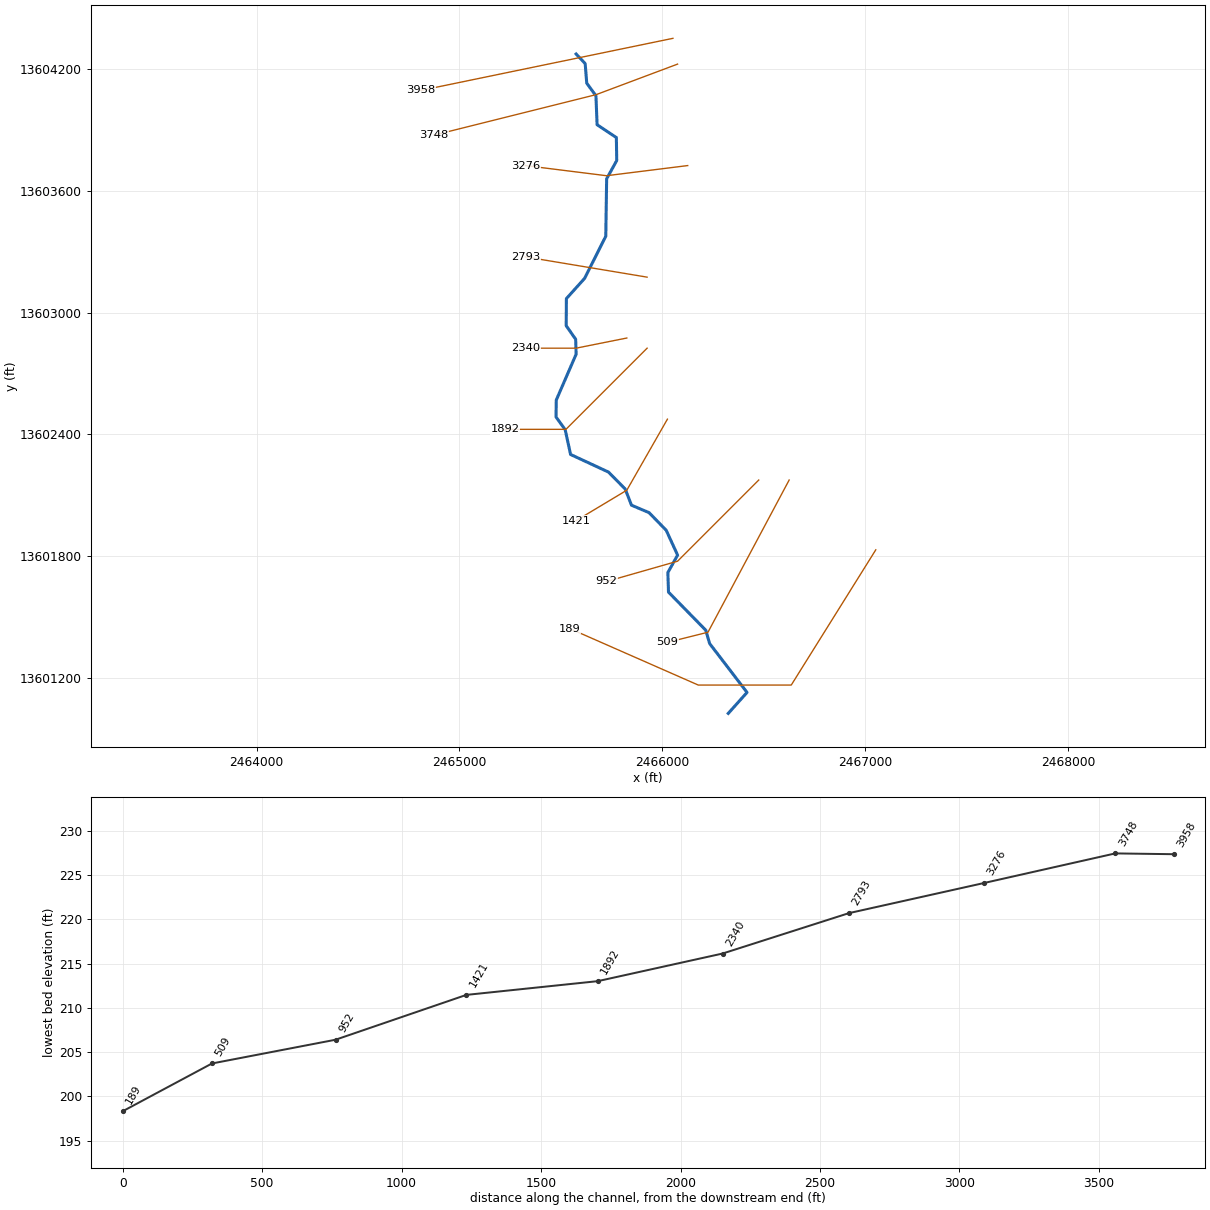
--- Stream0818.prj (project) ---

Proj Title=Stream0818 Base Level Engineering
Current Plan=p01
Default Exp/Contr=0.3,0.1
English Units
Geom File=g01
Flow File=f01
Plan File=p01
BEGIN DESCRIPTION:
Stream0818
END DESCRIPTION:

--- Stream0818.p01 (plan) ---

Plan Title=Multiple Run
Short Identifier=Multiple
Geom File=g01
Flow File=f01
Subcritical Flow
K Sum by GR= 0
Std Step Tol= 0.01
Critical Tol= 0.01
Num of Std Step Trials= 20
Max Error Tol= 0.3
Flow Tol Ratio= 0.001
Split Flow NTrial= 30
Split Flow Tol= 0.02
Split Flow Ratio= 0.02
Log Output Level= 0
Friction Slope Method= 1
Unsteady Friction Slope Method= 2
Unsteady Bridges Friction Slope Method= 1
Parabolic Critical Depth
Global Vel Dist=  1 , 1 , 1
Global Log Level= 0
CheckData=True
Encroach Param= -1, 0, 0, 0
BEGIN DESCRIPTION:
Multiple Run
END DESCRIPTION:

--- Stream0818.f01 (steady flow) ---

Flow Title=Multiple
Number of Profiles=7
Profile Names=10-year,25-year,50-year,1pct_min,100-year,1pct_plu,500-year
River Rch & RM= Stream0818,Reach-1,3958
     930    1541    2110    1398    2789    5565    4831
Boundary for River Rch & Prof#=Stream0818,Reach-1,1
Up Type=0
Dn Type=3
Dn Slope=0.005
Boundary for River Rch & Prof#=Stream0818,Reach-1,2
Up Type=0
Dn Type=3
Dn Slope=0.005
Boundary for River Rch & Prof#=Stream0818,Reach-1,3
Up Type=0
Dn Type=3
Dn Slope=0.005
Boundary for River Rch & Prof#=Stream0818,Reach-1,4
Up Type=0
Dn Type=3
Dn Slope=0.005
Boundary for River Rch & Prof#=Stream0818,Reach-1,5
Up Type=0
Dn Type=3
Dn Slope=0.005
Boundary for River Rch & Prof#=Stream0818,Reach-1,6
Up Type=0
Dn Type=3
Dn Slope=0.005
Boundary for River Rch & Prof#=Stream0818,Reach-1,7
Up Type=0
Dn Type=3
Dn Slope=0.005

--- Stream0818.g01 (geometry) ---

Geom Title=Existing Conditions

River Reach=Stream0818,Reach-1
Reach XY= 30
      2465575.00     13604275.00      2465619.78     13604227.55
      2465627.32     13604130.96      2465672.73     13604069.06
      2465678.49     13603926.27      2465773.37     13603863.16
      2465775.24     13603749.95      2465725.52     13603659.78
      2465721.25     13603376.55      2465616.84     13603168.95
      2465527.05     13603069.14      2465526.21     13602935.51
      2465572.83     13602869.02      2465575.10     13602795.10
      2465477.17     13602569.03      2465476.10     13602485.55
      2465521.14     13602423.40      2465547.72     13602301.10
      2465734.70     13602214.24      2465816.84     13602131.05
      2465847.86     13602051.16      2465934.68     13602014.22
      2466019.18     13601927.31      2466075.29     13601804.83
      2466027.19     13601719.03      2466030.40     13601622.57
      2466214.22     13601434.68      2466233.18     13601368.96
      2466417.48     13601128.33      2466325.00     13601025.00

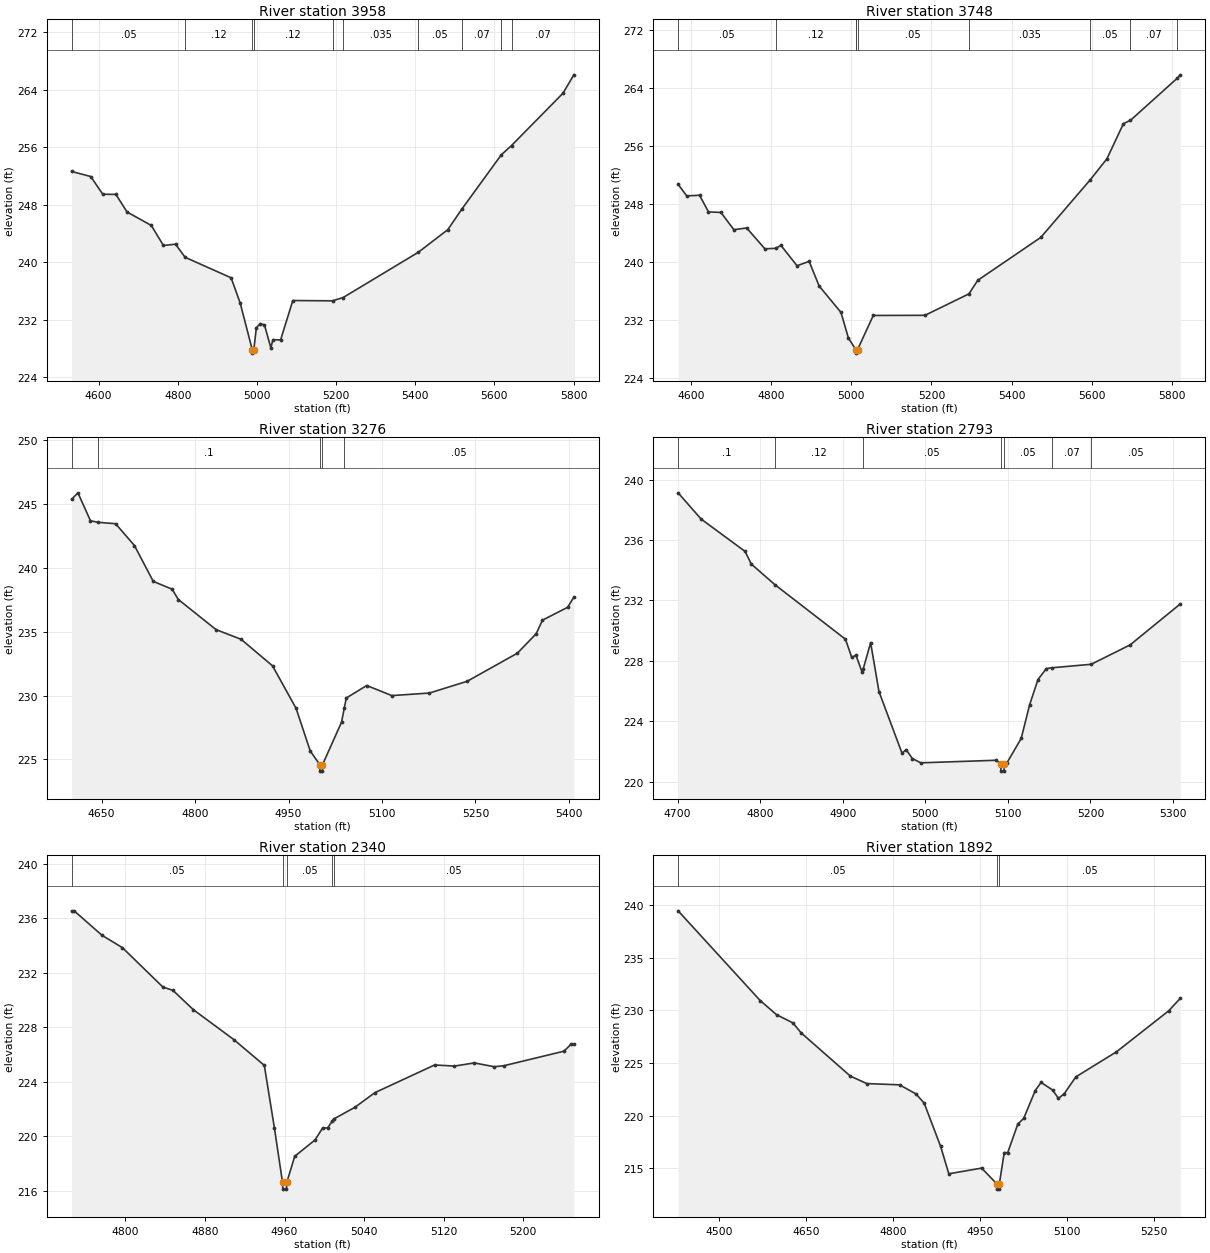
Type RM Length L Ch R = 1,3958,210,210,210
BEGIN DESCRIPTION:
XS7777
END DESCRIPTION:
XS GIS Cut Line= 2
      2466052.11     13604352.09      2464809.48     13604095.23
#Sta/Elev= 30
  4531.8  252.62  4579.9  251.92  4610.5  249.45  4643.6  249.43  4671.8  246.98
  4733.1  245.11  4763.7  242.32  4794.3  242.50  4818.4  240.68  4934.8  237.82
  4957.7  234.30  4988.0  227.84  4988.3  227.34  4992.1  227.84  4998.6  230.89
  5008.8  231.46  5019.0  231.26  5035.2  228.07  5040.3  229.21  5059.8  229.18
  5090.6  234.66  5190.9  234.62  5217.9  235.08  5407.6  241.37  5482.2  244.52
  5517.5  247.37  5617.3  254.93  5643.2  256.23  5773.3  263.51  5800.7  266.07
#Mann=10,-1,0
  4531.8    0.05       0  4818.4    0.12       0  4988.0    0.05       0
  4992.1    0.12       0  5190.9    0.05       0  5217.9   0.035       0
  5407.6    0.05       0  5517.5    0.07       0  5617.3   0.035       0
  5643.2    0.07       0
Bank Sta=4988,4992.1
Exp/Cntr=0.3,0.1

Type RM Length L Ch R = 1,3748,472,472,472
BEGIN DESCRIPTION:
Stream0818 8.0
END DESCRIPTION:
XS GIS Cut Line= 3
      2466075.01     13604225.00      2465675.00     13604075.00
      2464875.03     13603875.01
#Sta/Elev= 30
  4568.6  250.74  4590.0  249.14  4622.0  249.22  4644.3  246.93  4675.4  246.85
  4707.5  244.47  4739.5  244.71  4784.9  241.83  4812.0  241.90  4824.9  242.31
  4865.0  239.49  4895.2  240.10  4920.2  236.69  4974.5  233.06  4993.1  229.51
  5011.0  227.96  5011.8  227.93  5012.1  227.43  5016.0  227.93  5055.1  232.63
  5183.9  232.65  5293.5  235.61  5315.4  237.48  5472.5  243.40  5595.5  251.33
  5637.5  254.26  5678.7  259.12  5696.2  259.57  5812.7  265.38  5820.4  265.85
#Mann=9,-1,0
  4568.6    0.05       0  4812.0    0.12       0  5011.0    0.05       0
  5011.8    0.05       0  5016.0    0.05       0  5293.5   0.035       0
  5595.5    0.05       0  5696.2    0.07       0  5812.7   0.035       0
Bank Sta=5011.8,5016
Exp/Cntr=0.3,0.1

Type RM Length L Ch R = 1,3276,483,483,483
BEGIN DESCRIPTION:
Stream0818 7.0
END DESCRIPTION:
XS GIS Cut Line= 3
      2466125.00     13603725.00      2465725.00     13603675.00
      2465325.03     13603725.00
#Sta/Elev= 30
  4601.8  245.39  4611.9  245.89  4632.0  243.70  4644.2  243.58  4672.3  243.47
  4702.6  241.76  4732.8  238.95  4763.0  238.34  4773.1  237.53  4833.6  235.17
  4873.9  234.41  4924.3  232.33  4962.1  229.00  4984.8  225.66  5000.3  224.58
  5000.5  224.08  5004.2  224.08  5004.5  224.58  5035.1  227.92  5039.6  229.04
  5042.7  229.81  5075.5  230.79  5115.8  230.00  5176.2  230.20  5236.7  231.12
  5317.3  233.32  5347.6  234.85  5357.6  235.91  5398.0  236.92  5408.0  237.71
#Mann=5,-1,0
  4601.8    0.05       0  4644.2     0.1       0  5000.3    0.05       0
  5004.5     0.1       0  5039.6    0.05       0
Bank Sta=5000.3,5004.5
Exp/Cntr=0.3,0.1

Type RM Length L Ch R = 1,2793,453,453,453
BEGIN DESCRIPTION:
Stream0818 6.0
END DESCRIPTION:
XS GIS Cut Line= 3
      2465924.98     13603175.00      2465625.00     13603225.00
      2465324.96     13603275.01
#Sta/Elev= 30
  4700.6  239.13  4728.5  237.39  4781.7  235.25  4789.3  234.41  4817.7  233.05
  4903.3  229.43  4910.9  228.23  4916.0  228.37  4923.6  227.23  4924.8  227.46
  4933.8  229.20  4943.9  225.96  4971.8  221.88  4976.8  222.11  4984.4  221.52
  4994.6  221.24  5085.8  221.41  5091.3  221.19  5091.6  220.69  5095.3  220.69
  5095.6  221.19  5098.5  221.20  5116.2  222.86  5126.4  225.09  5136.5  226.76
  5146.7  227.49  5153.8  227.54  5201.0  227.77  5248.0  229.05  5308.9  231.77
#Mann=7,-1,0
  4700.6     0.1       0  4817.7    0.12       0  4924.8    0.05       0
  5091.3    0.05       0  5095.6    0.05       0  5153.8    0.07       0
  5201.0    0.05       0
Bank Sta=5091.3,5095.6
Exp/Cntr=0.3,0.1

Type RM Length L Ch R = 1,2340,448,448,448
BEGIN DESCRIPTION:
Stream0818 5.0
END DESCRIPTION:
XS GIS Cut Line= 3
      2465824.96     13602874.99      2465575.00     13602825.00
      2465325.01     13602825.00
#Sta/Elev= 30
  4745.9  236.55  4748.4  236.55  4776.5  234.75  4796.9  233.85  4837.6  230.96
  4847.8  230.71  4868.2  229.30  4909.0  227.10  4939.6  225.21  4949.8  220.60
  4957.9  216.63  4958.2  216.13  4961.9  216.13  4962.2  216.63  4970.2  218.54
  4990.6  219.74  4998.3  220.62  5003.3  220.62  5007.7  221.10  5009.3  221.27
  5030.8  222.14  5050.8  223.21  5110.8  225.24  5130.8  225.16  5150.8  225.39
  5170.8  225.11  5180.8  225.19  5240.8  226.25  5248.3  226.78  5250.8  226.78
#Mann=5,-1,0
  4745.9    0.05       0  4957.9    0.05       0  4962.2    0.05       0
  5007.7    0.07       0  5009.3    0.05       0
Bank Sta=4957.9,4962.2
Exp/Cntr=0.3,0.1

Type RM Length L Ch R = 1,1892,471,471,471
BEGIN DESCRIPTION:
Stream0818 4.0
END DESCRIPTION:
XS GIS Cut Line= 3
      2465924.97     13602824.97      2465525.00     13602425.00
      2465225.04     13602425.00
#Sta/Elev= 30
  4429.7  239.48  4571.1  230.95  4599.4  229.60  4627.6  228.82  4641.8  227.87
  4726.6  223.76  4754.9  223.05  4811.5  222.93  4839.8  222.06  4853.9  221.18
  4882.2  217.07  4896.3  214.47  4952.9  215.01  4979.0  213.51  4979.3  213.01
  4983.1  213.01  4983.4  213.51  4991.8  216.48  4997.8  216.48  5015.3  219.21
  5025.3  219.73  5045.3  222.39  5055.3  223.16  5075.3  222.43  5085.3  221.64
  5095.3  222.09  5115.3  223.69  5185.3  226.07  5275.3  229.97  5295.3  231.16
#Mann=3,-1,0
  4429.7    0.05       0  4979.0    0.05       0  4983.4    0.05       0
Bank Sta=4979,4983.4
Exp/Cntr=0.3,0.1

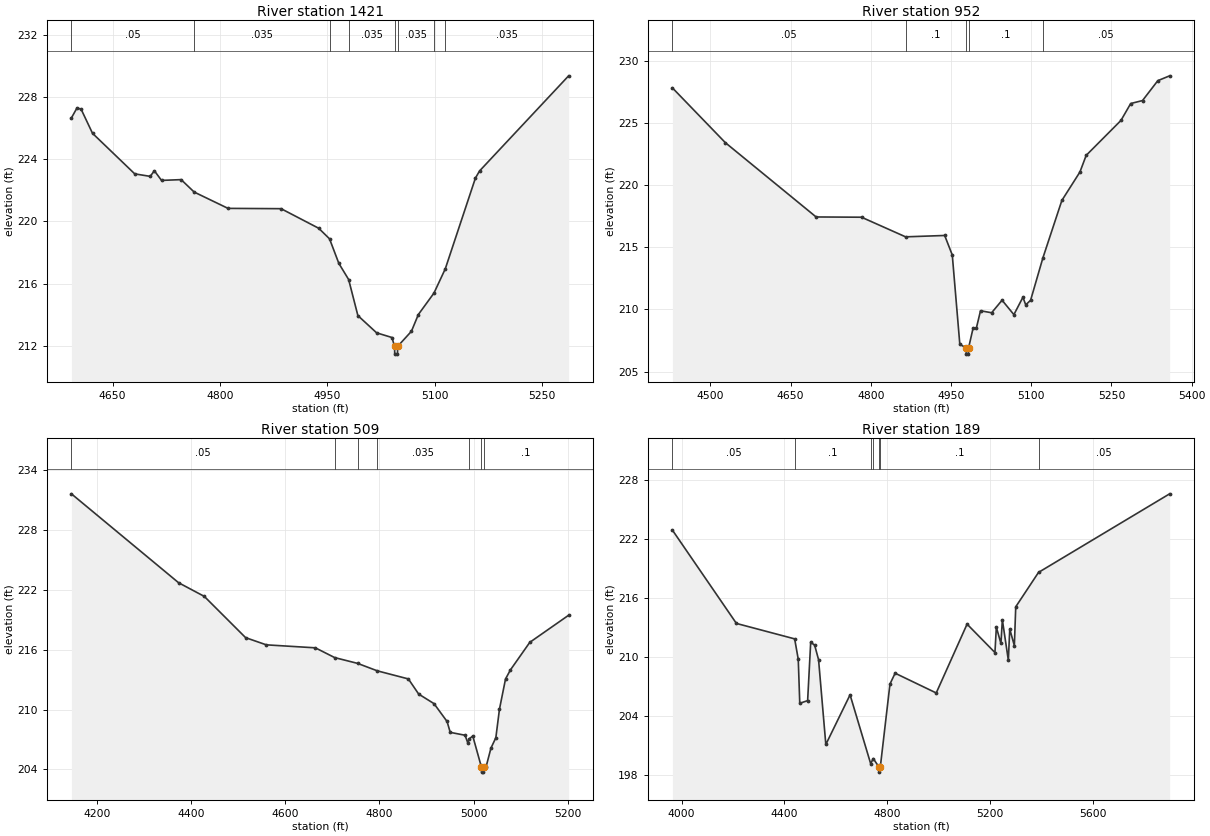
Type RM Length L Ch R = 1,1421,469,469,469
BEGIN DESCRIPTION:
Stream0818 3.0
END DESCRIPTION:
XS GIS Cut Line= 3
      2466024.99     13602474.98      2465825.00     13602125.00
      2465575.03     13601975.02
#Sta/Elev= 30
  4592.5  226.66  4600.4  227.31  4606.1  227.22  4622.0  225.67  4681.0  223.06
  4702.6  222.90  4708.4  223.26  4718.4  222.64  4745.8  222.69  4764.0  221.89
  4811.3  220.84  4885.4  220.82  4938.0  219.56  4953.1  218.88  4966.1  217.30
  4979.8  216.26  4992.7  213.94  5018.9  212.83  5040.3  212.53  5043.9  211.96
  5044.2  211.46  5048.0  211.46  5048.3  211.96  5067.5  212.93  5077.2  214.01
  5099.0  215.39  5114.8  216.95  5156.9  222.79  5162.7  223.25  5287.1  229.37
#Mann=8,-1,0
  4592.5    0.05       0  4764.0   0.035       0  4953.1     0.1       0
  4979.8   0.035       0  5043.9   0.035       0  5048.3   0.035       0
  5099.0    0.05       0  5114.8   0.035       0
Bank Sta=5043.9,5048.3
Exp/Cntr=0.3,0.1

Type RM Length L Ch R = 1,952,443,443,443
BEGIN DESCRIPTION:
Stream0818 2.0
END DESCRIPTION:
XS GIS Cut Line= 3
      2466475.02     13602175.02      2466075.00     13601775.00
      2465725.01     13601675.00
#Sta/Elev= 30
  4429.1  227.83  4528.1  223.42  4697.8  217.44  4782.7  217.42  4865.1  215.84
  4938.2  215.95  4952.4  214.38  4966.5  207.19  4978.4  206.90  4978.7  206.40
  4982.6  206.40  4982.9  206.90  4991.3  208.49  4997.4  208.49  5005.2  209.89
  5026.0  209.73  5045.5  210.74  5067.6  209.58  5084.5  210.98  5089.7  210.37
  5098.8  210.73  5121.8  214.14  5157.3  218.77  5191.1  221.06  5202.8  222.40
  5267.8  225.21  5286.0  226.57  5308.1  226.81  5336.7  228.41  5358.8  228.80
#Mann=5,-1,0
  4429.1    0.05       0  4865.1     0.1       0  4978.4    0.05       0
  4982.9     0.1       0  5121.8    0.05       0
Bank Sta=4978.4,4982.9
Exp/Cntr=0.3,0.1

Type RM Length L Ch R = 1,509,320,320,320
BEGIN DESCRIPTION:
Stream0818 1.0
END DESCRIPTION:
XS GIS Cut Line= 3
      2466625.01     13602175.01      2466225.00     13601425.00
      2466024.97     13601374.99
#Sta/Elev= 30
  4145.6  231.64  4373.3  222.72  4427.9  221.35  4515.7  217.21  4559.6  216.49
  4663.8  216.19  4704.9  215.21  4753.5  214.63  4795.5  213.88  4861.4  213.07
  4883.3  211.55  4915.9  210.59  4943.6  208.80  4950.3  207.71  4981.8  207.42
  4987.5  206.67  4990.6  207.06  4998.2  207.34  5016.6  204.22  5016.9  203.72
  5020.8  203.72  5021.1  204.22  5026.5  204.26  5036.8  206.13  5047.2  207.17
  5054.9  210.04  5067.8  213.07  5078.1  213.97  5119.3  216.74  5201.8  219.46
#Mann=7,-1,0
  4145.6    0.05       0  4704.9   0.035       0  4753.5     0.1       0
  4795.5   0.035       0  4990.6     0.1       0  5016.6    0.05       0
  5021.1     0.1       0
Bank Sta=5016.6,5021.1
Exp/Cntr=0.3,0.1

Type RM Length L Ch R = 1,189,0,0,0
BEGIN DESCRIPTION:
XS7776
END DESCRIPTION:
XS GIS Cut Line= 4
      2467052.07     13601831.23      2466635.42     13601164.58
      2466177.08     13601164.58      2465545.12     13601442.37
#Sta/Elev= 30
  3964.4  222.94  4213.5  213.45  4440.1  211.88  4454.1  209.81  4460.0  205.33
  4490.6  205.60  4502.5  211.53  4517.8  211.25  4533.1  209.77  4561.4  201.14
  4655.7  206.19  4735.9  199.19  4745.9  199.71  4768.7  198.83  4769.0  198.33
  4773.3  198.83  4811.0  207.29  4831.0  208.39  4991.0  206.38  5111.0  213.38
  5219.5  210.49  5224.9  213.07  5242.8  211.41  5248.3  213.82  5271.6  209.71
  5277.1  212.88  5295.0  211.19  5300.4  215.14  5389.0  218.64  5899.2  226.63
#Mann=7,-1,0
  3964.4    0.05       0  4440.1     0.1       0  4735.9   0.035       0
  4745.9     0.1       0  4768.7    0.05       0  4773.3     0.1       0
  5389.0    0.05       0
Bank Sta=4768.7,4773.3
Exp/Cntr=0.3,0.1

Chan Stop Cuts=-1