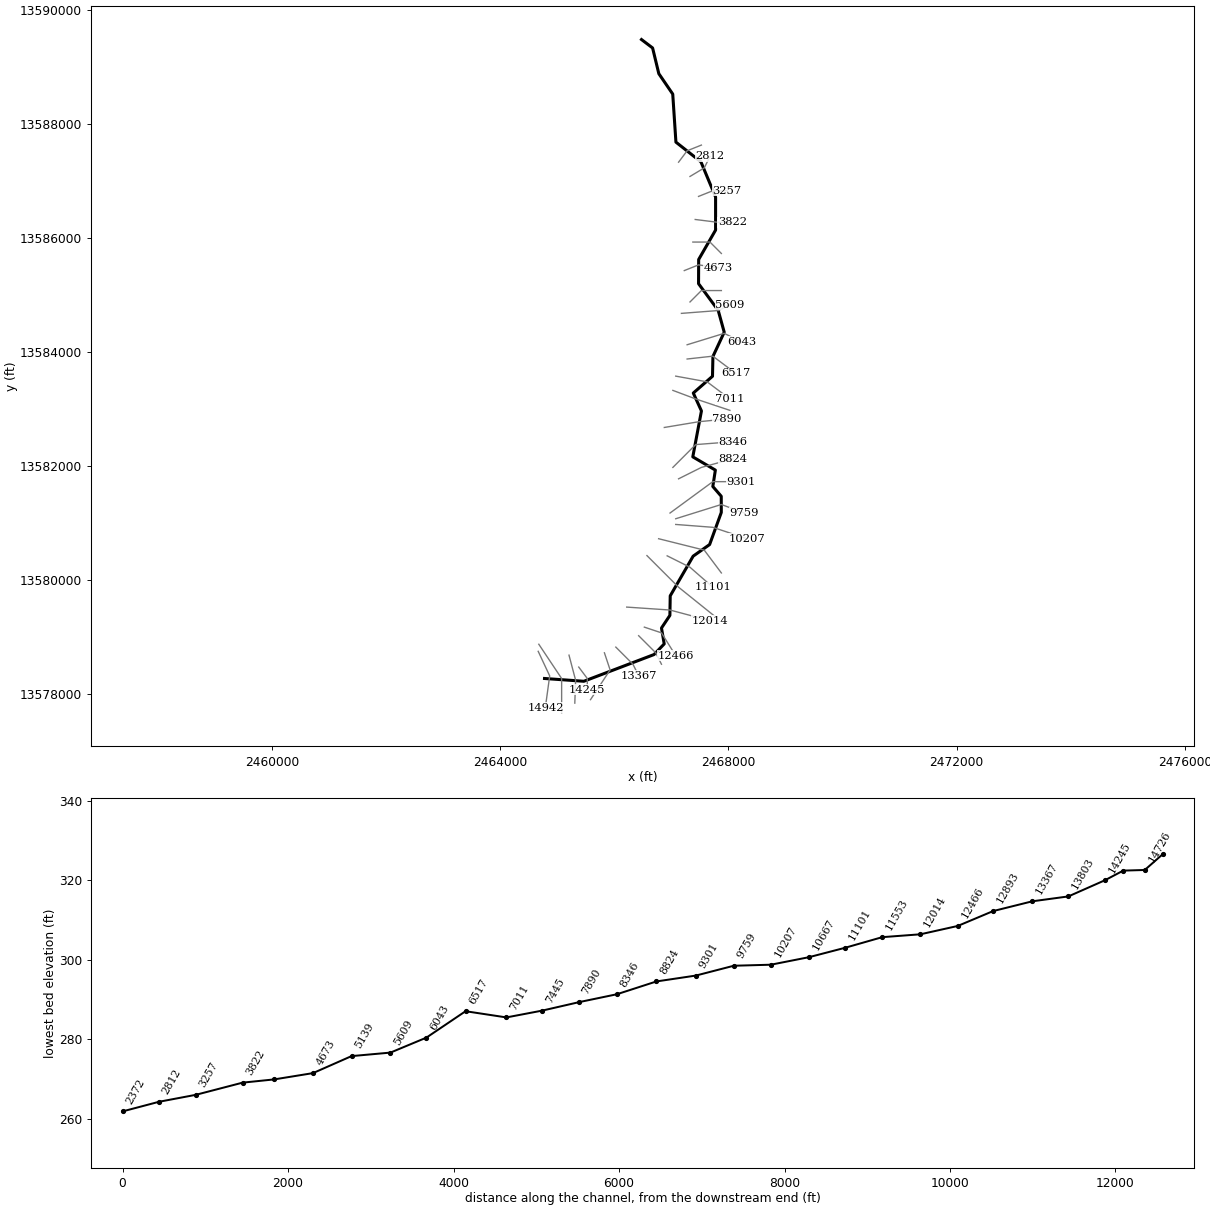
--- Stream0819.prj (project) ---

Proj Title=Stream0819 Base Level Engineering
Current Plan=p01
Default Exp/Contr=0.3,0.1
English Units
Geom File=g01
Flow File=f01
Plan File=p01
BEGIN DESCRIPTION:
Stream0819
END DESCRIPTION:

--- Stream0819.p01 (plan) ---

Plan Title=Multiple Run
Short Identifier=Multiple
Geom File=g01
Flow File=f01
Subcritical Flow
K Sum by GR= 0
Std Step Tol= 0.01
Critical Tol= 0.01
Num of Std Step Trials= 20
Max Error Tol= 0.3
Flow Tol Ratio= 0.001
Split Flow NTrial= 30
Split Flow Tol= 0.02
Split Flow Ratio= 0.02
Log Output Level= 0
Friction Slope Method= 1
Unsteady Friction Slope Method= 2
Unsteady Bridges Friction Slope Method= 1
Parabolic Critical Depth
Global Vel Dist=  1 , 1 , 1
Global Log Level= 0
CheckData=True
Encroach Param= -1, 0, 0, 0
BEGIN DESCRIPTION:
Multiple Run
END DESCRIPTION:

--- Stream0819.f01 (steady flow) ---

Flow Title=Multiple
Number of Profiles=7
Profile Names=10-year,25-year,50-year,1pct_min,100-year,1pct_plu,500-year
River Rch & RM= Stream0819,Reach-1,14942
     343     534     701     447     892    1780    1429
River Rch & RM= Stream0819,Reach-1,13367
     677    1097    1477     964    1923    3838    3230
River Rch & RM= Stream0819,Reach-1,10667
     962    1580    2148    1412    2816    5619    4799
Boundary for River Rch & Prof#=Stream0819,Reach-1,1
Up Type=0
Dn Type=3
Dn Slope=0.005
Boundary for River Rch & Prof#=Stream0819,Reach-1,2
Up Type=0
Dn Type=3
Dn Slope=0.005
Boundary for River Rch & Prof#=Stream0819,Reach-1,3
Up Type=0
Dn Type=3
Dn Slope=0.005
Boundary for River Rch & Prof#=Stream0819,Reach-1,4
Up Type=0
Dn Type=3
Dn Slope=0.005
Boundary for River Rch & Prof#=Stream0819,Reach-1,5
Up Type=0
Dn Type=3
Dn Slope=0.005
Boundary for River Rch & Prof#=Stream0819,Reach-1,6
Up Type=0
Dn Type=3
Dn Slope=0.005
Boundary for River Rch & Prof#=Stream0819,Reach-1,7
Up Type=0
Dn Type=3
Dn Slope=0.005

--- Stream0819.g01 (geometry) ---

Geom Title=Existing Conditions

River Reach=Stream0819,Reach-1
Reach XY= 30
      2464775.00     13578275.00      2465464.50     13578226.20
      2466695.09     13578694.78      2466873.04     13578880.89
      2466825.37     13579159.83      2466972.76     13579380.93
      2466978.54     13579723.54      2467380.59     13580419.39
      2467669.18     13580622.69      2467873.80     13581185.50
      2467872.94     13581469.15      2467725.37     13581640.16
      2467769.72     13581927.71      2467374.23     13582159.91
      2467525.78     13582964.95      2467382.77     13583278.41
      2467719.55     13583572.53      2467727.06     13583919.15
      2467925.10     13584345.10      2467819.53     13584727.45
      2467475.07     13585195.03      2467477.06     13585619.14
      2467773.80     13586135.50      2467773.78     13586714.50
      2467516.86     13587331.06      2467078.53     13587676.45
      2467022.67     13588519.03      2466778.68     13588876.59
      2466669.54     13589327.46      2466475.00     13589475.00

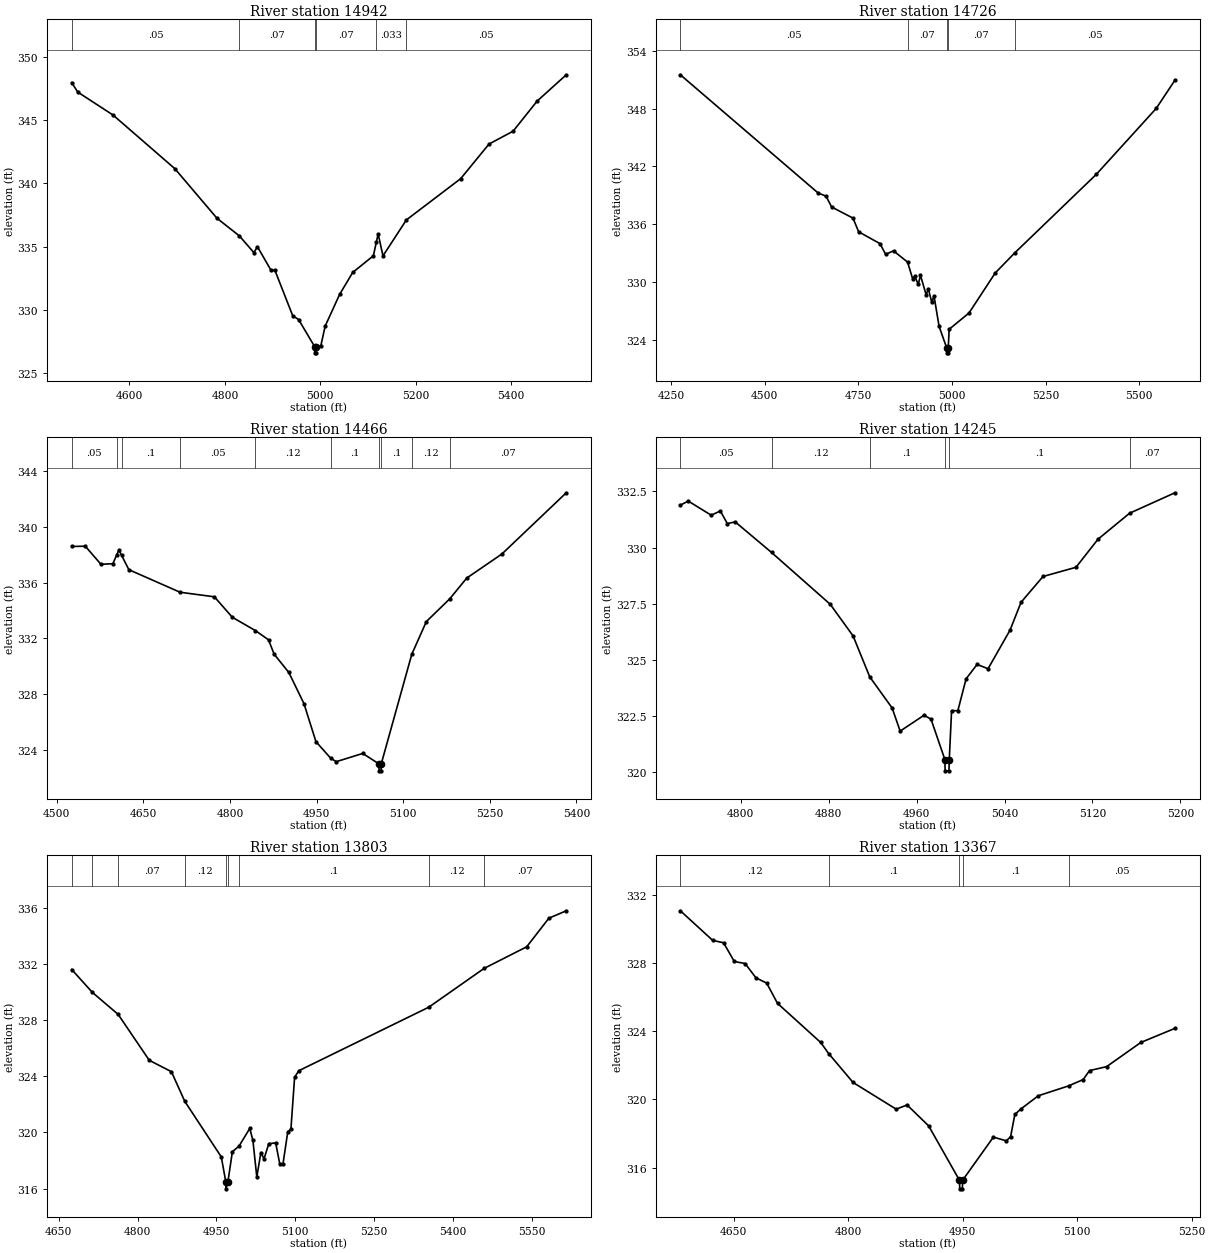
Type RM Length L Ch R = 1,14942,216,216,216
BEGIN DESCRIPTION:
XS7779
END DESCRIPTION:
XS GIS Cut Line= 3
      2464664.35     13578750.72      2464865.74     13578320.18
      2464789.35     13577764.62
#Sta/Elev= 30
  4479.1  347.99  4491.7  347.24  4565.7  345.42  4695.2  341.17  4783.5  337.24
  4830.2  335.85  4860.8  334.52  4868.2  334.99  4896.5  333.13  4904.9  333.11
  4942.2  329.51  4954.4  329.22  4987.9  327.08  4988.2  326.58  4991.7  326.58
  4991.9  327.08  5000.8  327.10  5010.1  328.70  5040.4  331.21  5067.8  332.95
  5111.1  334.27  5117.3  335.35  5121.1  336.01  5131.2  334.26  5180.2  337.11
  5294.0  340.38  5353.3  343.12  5403.8  344.14  5454.3  346.53  5515.2  348.61
#Mann=6,-1,0
  4479.1    0.05       0  4830.2    0.07       0  4987.9    0.05       0
  4991.9    0.07       0  5117.3   0.033       0  5180.2    0.05       0
Bank Sta=4987.9,4991.9
Exp/Cntr=0.3,0.1

Type RM Length L Ch R = 1,14726,260,260,260
BEGIN DESCRIPTION:
Stream0819 32.0
END DESCRIPTION:
XS GIS Cut Line= 3
      2464674.99     13578875.02      2465075.00     13578275.00
      2465075.00     13577675.03
#Sta/Elev= 30
  4274.3  351.53  4642.4  339.24  4663.4  338.92  4678.4  337.79  4735.5  336.63
  4750.6  335.21  4807.6  333.98  4822.7  332.87  4843.7  333.23  4881.3  332.06
  4894.8  330.33  4900.8  330.59  4909.8  329.74  4915.8  330.69  4930.8  328.67
  4936.8  329.26  4945.9  327.89  4951.9  328.56  4965.4  325.39  4985.9  323.13
  4986.2  322.63  4989.7  322.63  4989.9  323.13  4992.4  325.08  5045.4  326.77
  5115.4  330.93  5167.1  333.00  5385.4  341.18  5545.4  348.03  5595.4  350.96
#Mann=5,-1,0
  4274.3    0.05       0  4881.3    0.07       0  4985.9    0.05       0
  4989.9    0.07       0  5167.1    0.05       0
Bank Sta=4985.9,4989.9
Exp/Cntr=0.3,0.1

Type RM Length L Ch R = 1,14466,221,221,221
BEGIN DESCRIPTION:
H21099
END DESCRIPTION:
XS GIS Cut Line= 3
      2465204.33     13578683.97      2465320.10     13578244.51
      2465305.92     13577842.81
#Sta/Elev= 30
  4526.0  338.60  4549.5  338.62  4576.6  337.32  4597.3  337.36  4603.9  337.99
  4607.7  338.35  4612.4  337.96  4625.0  336.93  4713.6  335.31  4773.1  334.98
  4804.1  333.51  4844.2  332.55  4866.8  331.89  4876.5  330.86  4902.0  329.54
  4928.2  327.30  4948.9  324.57  4974.4  323.38  4984.2  323.13  5030.0  323.72
  5058.0  322.97  5058.3  322.47  5061.8  322.47  5062.0  322.97  5114.9  330.85
  5140.1  333.20  5180.5  334.83  5210.1  336.33  5271.0  338.06  5382.4  342.46
#Mann=10,-1,0
  4526.0    0.05       0  4603.9    0.07       0  4612.4     0.1       0
  4713.6    0.05       0  4844.2    0.12       0  4974.4     0.1       0
  5058.0    0.05       0  5062.0     0.1       0  5114.9    0.12       0
  5180.5    0.07       0
Bank Sta=5058,5062
Exp/Cntr=0.3,0.1

Type RM Length L Ch R = 1,14245,442,442,442
BEGIN DESCRIPTION:
Stream0819 31.0
END DESCRIPTION:
XS GIS Cut Line= 3
      2465375.03     13578474.97      2465525.00     13578275.00
      2465525.00     13578074.96
#Sta/Elev= 30
  4745.0  331.89  4752.2  332.07  4773.1  331.44  4781.4  331.63  4787.7  331.07
  4795.0  331.14  4828.0  329.78  4881.4  327.47  4902.2  326.06  4917.3  324.24
  4937.7  322.85  4945.0  321.82  4966.8  322.53  4973.1  322.35  4985.7  320.55
  4985.9  320.05  4989.4  320.05  4989.7  320.55  4991.8  322.73  4997.5  322.73
  5005.0  324.15  5015.0  324.79  5025.0  324.60  5045.0  326.32  5055.0  327.56
  5075.0  328.71  5105.0  329.12  5125.0  330.37  5153.8  331.53  5195.0  332.44
#Mann=6,-1,0
  4745.0    0.05       0  4828.0    0.12       0  4917.3     0.1       0
  4985.7    0.05       0  4989.7     0.1       0  5153.8    0.07       0
Bank Sta=4985.7,4989.7
Exp/Cntr=0.3,0.1

Type RM Length L Ch R = 1,13803,436,436,436
BEGIN DESCRIPTION:
Stream0819 30.0
END DESCRIPTION:
XS GIS Cut Line= 3
      2465825.00     13578725.01      2465925.00     13578425.00
      2465580.99     13577903.48
#Sta/Elev= 30
  4674.8  331.63  4714.0  330.00  4763.1  328.43  4822.4  325.15  4864.5  324.34
  4890.0  322.22  4959.4  318.26  4968.0  316.48  4968.2  315.98  4972.0  316.48
  4980.5  318.63  4993.2  319.03  5013.6  320.29  5019.6  319.43  5027.0  316.82
  5034.7  318.57  5040.7  318.12  5049.8  319.20  5062.9  319.26  5070.8  317.73
  5076.8  317.76  5085.9  320.05  5091.9  320.24  5098.9  323.94  5107.0  324.41
  5354.2  328.94  5459.5  331.71  5540.5  333.25  5582.7  335.29  5615.8  335.82
#Mann=9,-1,0
  4674.8    0.07       0  4714.0    0.12       0  4763.1    0.07       0
  4890.0    0.12       0  4968.0    0.05       0  4972.0    0.12       0
  4993.2     0.1       0  5354.2    0.12       0  5459.5    0.07       0
Bank Sta=4968,4972
Exp/Cntr=0.3,0.1

Type RM Length L Ch R = 1,13367,474,474,474
BEGIN DESCRIPTION:
Stream0819 29.0
END DESCRIPTION:
XS GIS Cut Line= 3
      2466025.00     13578825.00      2466325.00     13578525.00
      2466425.01     13578324.98
#Sta/Elev= 30
  4580.1  331.09  4622.5  329.35  4636.7  329.21  4650.8  328.11  4665.0  327.99
  4679.1  327.15  4693.2  326.84  4707.4  325.65  4764.0  323.35  4774.4  322.70
  4806.4  321.00  4862.9  319.43  4877.1  319.68  4905.4  318.45  4945.8  315.25
  4946.1  314.75  4949.6  314.75  4949.8  315.25  4990.2  317.79  5007.2  317.57
  5012.8  317.82  5018.3  319.12  5026.7  319.46  5049.1  320.22  5088.7  320.80
  5107.8  321.17  5116.2  321.70  5138.5  321.93  5183.3  323.35  5228.0  324.18
#Mann=5,-1,0
  4580.1    0.12       0  4774.4     0.1       0  4945.8    0.05       0
  4949.8     0.1       0  5088.7    0.05       0
Bank Sta=4945.8,4949.8
Exp/Cntr=0.3,0.1

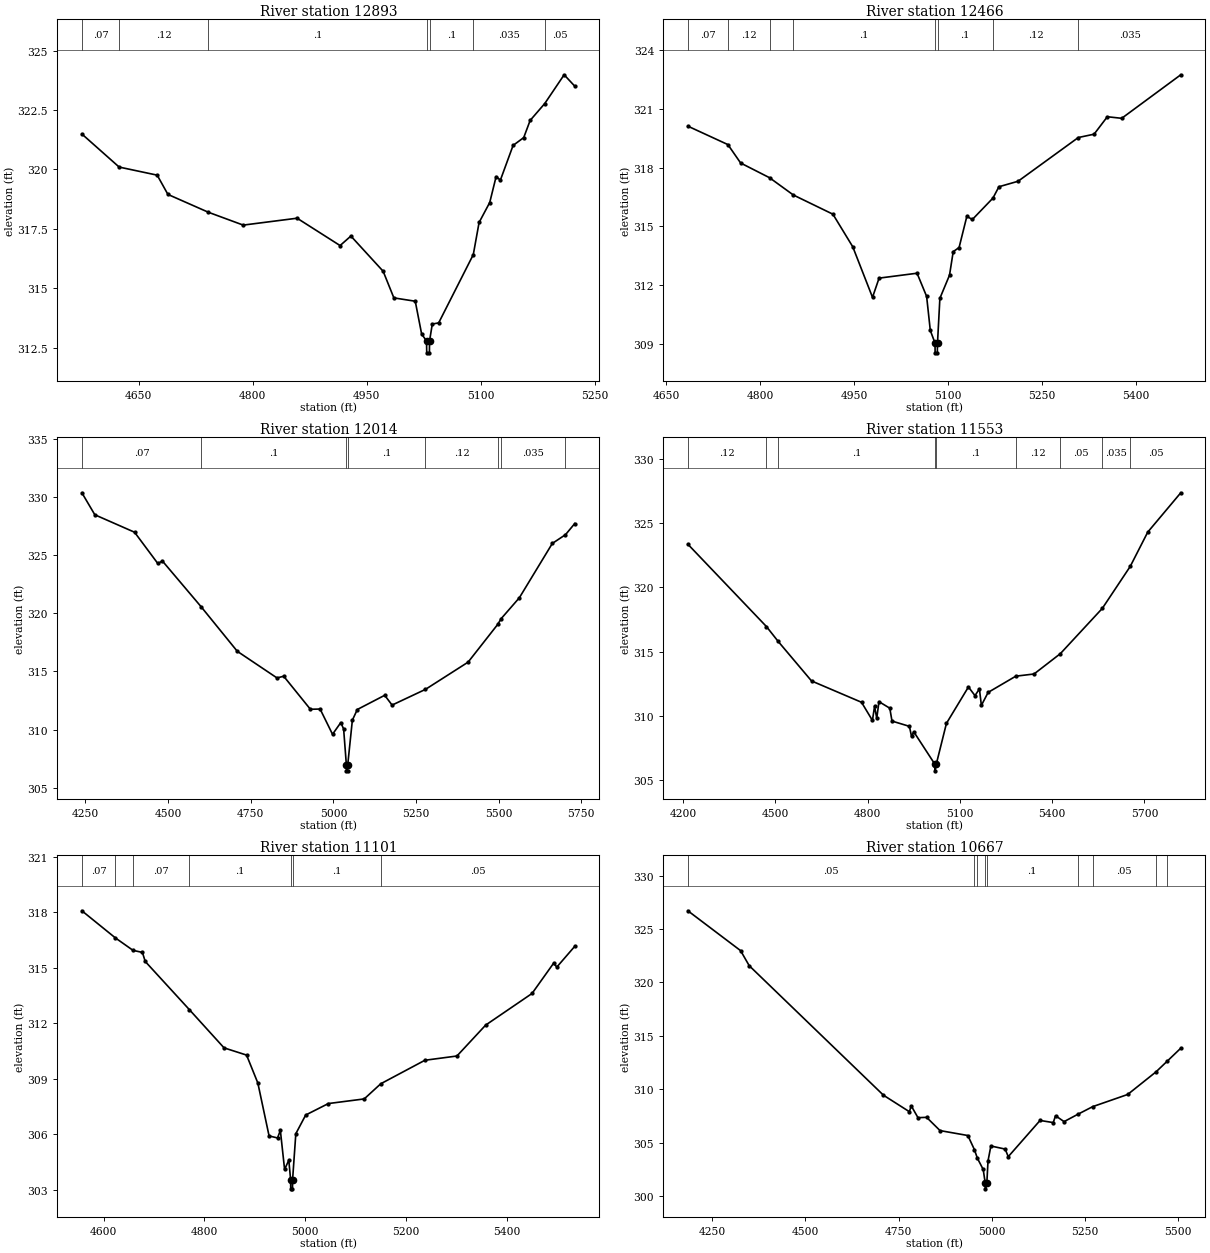
Type RM Length L Ch R = 1,12893,427,427,427
BEGIN DESCRIPTION:
Stream0819 28.0
END DESCRIPTION:
XS GIS Cut Line= 3
      2466424.99     13579025.01      2466725.00     13578725.00
      2466825.01     13578524.98
#Sta/Elev= 30
  4575.5  321.49  4624.5  320.10  4674.5  319.76  4688.6  318.95  4741.8  318.20
  4787.6  317.66  4858.4  317.95  4914.9  316.80  4929.1  317.20  4971.5  315.72
  4985.6  314.60  5013.7  314.46  5022.1  313.08  5028.5  312.79  5028.8  312.29
  5032.3  312.29  5032.5  312.79  5036.1  313.50  5044.5  313.55  5090.0  316.42
  5097.6  317.77  5111.6  318.61  5120.0  319.70  5125.6  319.55  5142.3  321.01
  5156.3  321.34  5164.7  322.06  5183.9  322.77  5209.4  323.98  5223.4  323.50
#Mann=7,-1,0
  4575.5    0.07       0  4624.5    0.12       0  4741.8     0.1       0
  5028.5    0.05       0  5032.5     0.1       0  5090.0   0.035       0
  5183.9    0.05       0
Bank Sta=5028.5,5032.5
Exp/Cntr=0.3,0.1

Type RM Length L Ch R = 1,12466,452,452,452
BEGIN DESCRIPTION:
Stream0819 27.0
END DESCRIPTION:
XS GIS Cut Line= 3
      2466524.96     13579175.01      2466825.00     13579075.00
      2467075.02     13578674.98
#Sta/Elev= 30
  4684.2  320.11  4748.2  319.17  4768.6  318.23  4814.8  317.48  4852.8  316.60
  4916.1  315.62  4947.8  313.96  4979.4  311.38  4989.9  312.36  5050.6  312.61
  5065.9  311.43  5071.8  309.69  5079.3  309.05  5079.5  308.55  5083.0  308.55
  5083.3  309.05  5087.1  311.33  5102.5  312.51  5108.4  313.71  5117.8  313.92
  5130.2  315.51  5139.0  315.35  5171.9  316.44  5181.5  317.02  5212.1  317.30
  5308.4  319.53  5333.6  319.70  5354.8  320.59  5377.8  320.51  5472.2  322.73
#Mann=8,-1,0
  4684.2    0.07       0  4748.2    0.12       0  4814.8    0.07       0
  4852.8     0.1       0  5079.3    0.05       0  5083.3     0.1       0
  5171.9    0.12       0  5308.4   0.035       0
Bank Sta=5079.3,5083.3
Exp/Cntr=0.3,0.1

Type RM Length L Ch R = 1,12014,461,461,461
BEGIN DESCRIPTION:
Stream0819 26.0
END DESCRIPTION:
XS GIS Cut Line= 3
      2466215.92     13579526.43      2466975.00     13579475.00
      2467680.58     13579286.29
#Sta/Elev= 30
  4239.1  330.34  4278.3  328.45  4398.5  326.95  4468.7  324.27  4483.0  324.47
  4599.8  320.55  4709.3  316.72  4829.5  314.43  4849.6  314.58  4930.4  311.74
  4959.8  311.76  4997.4  309.59  5022.5  310.60  5031.0  310.04  5039.3  306.95
  5039.6  306.45  5043.1  306.45  5043.3  306.95  5057.4  310.80  5072.4  311.72
  5155.2  312.94  5177.6  312.10  5278.6  313.45  5407.6  315.79  5497.1  319.03
  5507.7  319.53  5562.6  321.32  5662.4  325.99  5702.2  326.74  5730.3  327.70
#Mann=8,-1,0
  4239.1    0.07       0  4599.8     0.1       0  5039.3    0.05       0
  5043.3     0.1       0  5278.6    0.12       0  5497.1    0.05       0
  5507.7   0.035       0  5702.2    0.05       0
Bank Sta=5039.3,5043.3
Exp/Cntr=0.3,0.1

Type RM Length L Ch R = 1,11553,452,452,452
BEGIN DESCRIPTION:
Stream0819 25.0
END DESCRIPTION:
XS GIS Cut Line= 3
      2466570.52     13580429.00      2467125.00     13579875.00
      2467763.18     13579362.35
#Sta/Elev= 30
  4215.9  323.35  4471.3  316.95  4509.6  315.79  4617.9  312.72  4780.5  311.06
  4815.9  309.65  4822.9  310.75  4830.0  309.81  4837.1  311.11  4872.4  310.60
  4879.5  309.60  4936.1  309.19  4943.1  308.40  4950.2  308.77  5019.3  306.23
  5019.6  305.73  5023.3  306.23  5056.5  309.42  5128.0  312.25  5149.3  311.58
  5163.7  312.10  5170.1  310.82  5192.1  311.83  5282.0  313.09  5341.3  313.26
  5426.8  314.84  5563.2  318.36  5653.9  321.62  5710.9  324.29  5818.3  327.35
#Mann=9,-1,0
  4215.9    0.12       0  4471.3    0.07       0  4509.6     0.1       0
  5019.3    0.05       0  5023.3     0.1       0  5282.0    0.12       0
  5426.8    0.05       0  5563.2   0.035       0  5653.9    0.05       0
Bank Sta=5019.3,5023.3
Exp/Cntr=0.3,0.1

Type RM Length L Ch R = 1,11101,434,434,434
BEGIN DESCRIPTION:
Stream0819 24.0
END DESCRIPTION:
XS GIS Cut Line= 3
      2466925.02     13580424.99      2467325.00     13580225.00
      2467725.00     13579875.00
#Sta/Elev= 30
  4556.6  318.07  4623.3  316.60  4658.2  315.93  4676.8  315.82  4682.4  315.33
  4769.9  312.73  4838.9  310.66  4883.6  310.27  4906.0  308.76  4928.3  305.90
  4945.1  305.79  4950.7  306.20  4959.1  304.09  4967.5  304.59  4971.0  303.54
  4971.3  303.04  4974.8  303.04  4975.0  303.54  4981.4  306.02  5001.0  307.03
  5046.0  307.65  5117.2  307.90  5150.1  308.72  5237.7  309.99  5301.3  310.22
  5358.3  311.89  5450.4  313.60  5493.1  315.23  5499.7  315.03  5535.3  316.15
#Mann=7,-1,0
  4556.6    0.07       0  4623.3    0.12       0  4658.2    0.07       0
  4769.9     0.1       0  4971.0    0.05       0  4975.0     0.1       0
  5150.1    0.05       0
Bank Sta=4971,4975
Exp/Cntr=0.3,0.1

Type RM Length L Ch R = 1,10667,460,460,460
BEGIN DESCRIPTION:
Stream0819 23.0
END DESCRIPTION:
XS GIS Cut Line= 3
      2466775.03     13580724.99      2467575.00     13580525.00
      2467875.01     13580124.99
#Sta/Elev= 30
  4183.9  326.71  4325.6  322.98  4348.8  321.57  4709.6  309.45  4779.1  307.91
  4784.3  308.45  4802.3  307.35  4825.5  307.38  4861.6  306.14  4936.3  305.68
  4953.8  304.37  4962.0  303.55  4977.6  302.50  4983.2  301.19  4983.5  300.69
  4987.3  301.19  4990.5  303.30  4998.2  304.70  5036.6  304.41  5044.9  303.70
  5130.4  307.09  5165.8  306.89  5172.0  307.53  5194.9  306.98  5231.6  307.66
  5271.7  308.38  5365.8  309.52  5442.1  311.64  5472.8  312.66  5508.5  313.85
#Mann=9,-1,0
  4183.9    0.05       0  4953.8    0.07       0  4962.0     0.1       0
  4983.2    0.05       0  4987.3     0.1       0  5231.6    0.12       0
  5271.7    0.05       0  5442.1    0.12       0  5472.8   0.035       0
Bank Sta=4983.2,4987.3
Exp/Cntr=0.3,0.1

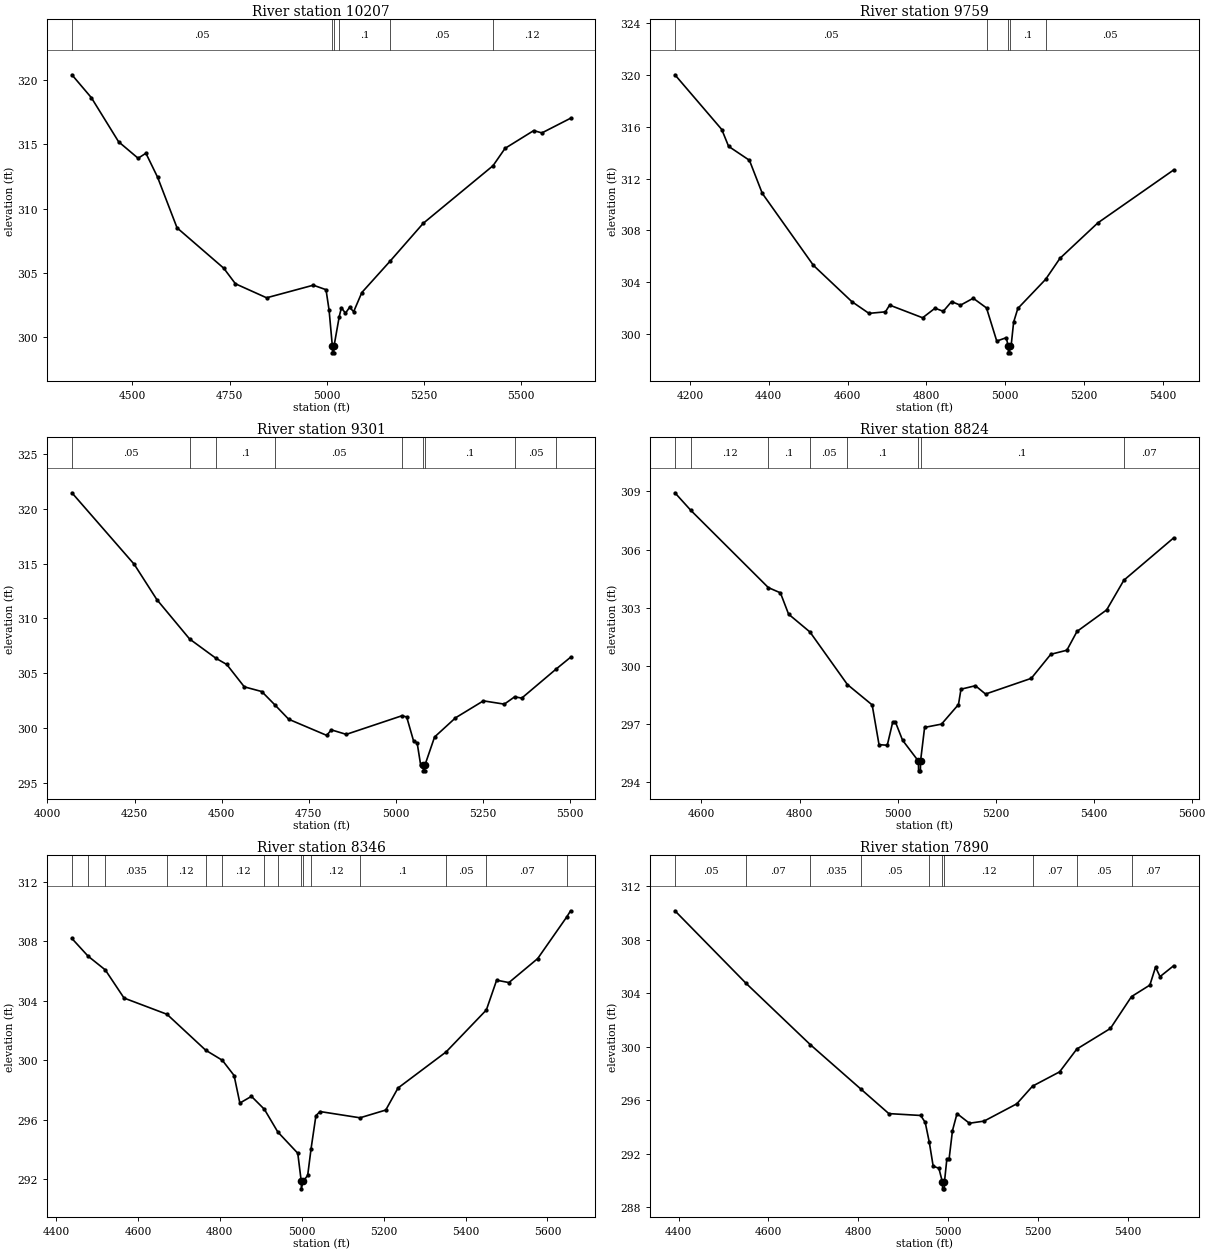
Type RM Length L Ch R = 1,10207,448,448,448
BEGIN DESCRIPTION:
Stream0819 22.0
END DESCRIPTION:
XS GIS Cut Line= 3
      2467075.01     13580975.00      2467725.00     13580925.00
      2468325.03     13580724.99
#Sta/Elev= 30
  4344.0  320.42  4394.1  318.64  4464.3  315.21  4514.5  313.93  4534.6  314.32
  4564.6  312.46  4614.8  308.52  4735.1  305.38  4765.2  304.17  4845.5  303.08
  4965.8  304.06  4998.5  303.71  5006.4  302.13  5014.9  299.30  5015.2  298.80
  5018.8  298.80  5019.0  299.30  5032.6  301.62  5038.1  302.31  5048.6  301.88
  5059.2  302.34  5069.7  302.00  5090.8  303.49  5163.6  305.93  5248.9  308.87
  5428.7  313.35  5459.7  314.70  5533.5  316.08  5554.6  315.90  5628.4  317.04
#Mann=6,-1,0
  4344.0    0.05       0  5014.9    0.05       0  5019.0    0.05       0
  5032.6     0.1       0  5163.6    0.05       0  5428.7    0.12       0
Bank Sta=5014.9,5019
Exp/Cntr=0.3,0.1

Type RM Length L Ch R = 1,9759,458,458,458
BEGIN DESCRIPTION:
Stream0819 21.0
END DESCRIPTION:
XS GIS Cut Line= 3
      2467074.99     13581075.00      2467875.00     13581325.00
      2468275.04     13581174.99
#Sta/Elev= 30
  4161.8  320.03  4280.7  315.80  4298.0  314.50  4350.9  313.42  4383.4  310.87
  4513.3  305.30  4610.7  302.50  4654.2  301.59  4696.1  301.71  4706.6  302.23
  4790.4  301.25  4821.9  301.99  4842.8  301.75  4863.8  302.50  4886.3  302.22
  4918.8  302.76  4952.5  302.01  4978.5  299.45  5002.6  299.71  5007.7  299.04
  5007.9  298.54  5011.5  298.54  5011.8  299.04  5015.1  299.12  5021.3  300.91
  5032.0  301.97  5102.5  304.22  5138.8  305.84  5234.9  308.58  5427.2  312.67
#Mann=5,-1,0
  4161.8    0.05       0  4952.5     0.1       0  5007.7    0.05       0
  5011.8     0.1       0  5102.5    0.05       0
Bank Sta=5007.7,5011.8
Exp/Cntr=0.3,0.1

Type RM Length L Ch R = 1,9301,477,477,477
BEGIN DESCRIPTION:
Stream0819 20.0
END DESCRIPTION:
XS GIS Cut Line= 3
      2466974.97     13581174.98      2467725.00     13581725.00
      2468225.01     13581725.00
#Sta/Elev= 30
  4070.5  321.46  4249.2  314.93  4314.0  311.71  4408.0  308.11  4483.5  306.35
  4514.7  305.78  4564.9  303.74  4615.0  303.31  4653.3  302.07  4692.3  300.78
  4801.1  299.31  4814.6  299.81  4857.4  299.40  5017.0  301.10  5030.6  300.99
  5050.6  298.77  5060.6  298.63  5070.6  296.62  5078.5  296.57  5078.8  296.07
  5082.4  296.07  5082.7  296.57  5110.6  299.16  5170.6  300.91  5250.6  302.46
  5310.6  302.16  5340.3  302.83  5360.6  302.71  5459.8  305.38  5500.6  306.44
#Mann=9,-1,0
  4070.5    0.05       0  4408.0    0.12       0  4483.5     0.1       0
  4653.3    0.05       0  5017.0     0.1       0  5078.5    0.05       0
  5082.7     0.1       0  5340.3    0.05       0  5459.8    0.07       0
Bank Sta=5078.5,5082.7
Exp/Cntr=0.3,0.1

Type RM Length L Ch R = 1,8824,478,478,478
BEGIN DESCRIPTION:
Stream0819 19.0
END DESCRIPTION:
XS GIS Cut Line= 3
      2467125.04     13581775.02      2467525.00     13581975.00
      2468075.05     13582125.01
#Sta/Elev= 30
  4545.8  308.93  4578.0  308.03  4736.4  304.04  4761.0  303.77  4777.7  302.67
  4821.3  301.75  4897.7  299.04  4948.2  297.99  4962.2  295.94  4979.0  295.91
  4990.2  297.11  4995.6  297.11  5010.2  296.17  5042.6  295.09  5042.9  294.59
  5046.6  294.59  5046.9  295.09  5055.2  296.83  5089.7  297.00  5124.3  298.01
  5129.4  298.80  5158.8  298.98  5179.5  298.55  5272.8  299.36  5312.6  300.60
  5345.4  300.81  5366.1  301.78  5426.6  302.89  5461.7  304.42  5563.1  306.60
#Mann=8,-1,0
  4545.8   0.035       0  4578.0    0.12       0  4736.4     0.1       0
  4821.3    0.05       0  4897.7     0.1       0  5042.6    0.05       0
  5046.9     0.1       0  5461.7    0.07       0
Bank Sta=5042.6,5046.9
Exp/Cntr=0.3,0.1

Type RM Length L Ch R = 1,8346,456,456,456
BEGIN DESCRIPTION:
Stream0819 18.0
END DESCRIPTION:
XS GIS Cut Line= 3
      2467025.01     13581975.01      2467425.00     13582375.00
      2468075.01     13582425.00
#Sta/Elev= 30
  4438.8  308.18  4478.4  306.99  4520.3  306.07  4566.1  304.18  4671.0  303.09
  4765.4  300.68  4806.2  300.00  4834.8  298.98  4848.9  297.13  4877.2  297.58
  4908.8  296.71  4941.5  295.19  4990.3  293.76  4998.8  291.87  4999.1  291.37
  5003.1  291.87  5014.5  292.27  5022.8  294.07  5034.6  296.28  5044.6  296.56
  5142.3  296.14  5205.1  296.66  5235.1  298.14  5352.4  300.56  5450.8  303.38
  5475.9  305.38  5505.9  305.22  5576.1  306.83  5647.7  309.65  5656.4  310.04
#Mann=15,-1,0
  4438.8   0.035       0  4478.4    0.12       0  4520.3   0.035       0
  4671.0    0.12       0  4765.4    0.05       0  4806.2    0.12       0
  4908.8    0.05       0  4941.5     0.1       0  4998.8    0.05       0
  5003.1     0.1       0  5022.8    0.12       0  5142.3     0.1       0
  5352.4    0.05       0  5450.8    0.07       0  5647.7    0.12       0
Bank Sta=4998.8,5003.1
Exp/Cntr=0.3,0.1

Type RM Length L Ch R = 1,7890,445,445,445
BEGIN DESCRIPTION:
Stream0819 17.0
END DESCRIPTION:
XS GIS Cut Line= 3
      2466874.99     13582675.00      2467475.00     13582775.00
      2467975.02     13582825.00
#Sta/Elev= 30
  4391.7  310.16  4550.2  304.74  4693.3  300.16  4806.0  296.84  4868.2  295.01
  4939.2  294.87  4949.3  294.35  4958.3  292.88  4967.0  291.08  4979.7  290.93
  4987.6  289.89  4987.9  289.39  4991.8  289.39  4992.1  289.89  4997.5  291.63
  5002.5  291.63  5010.0  293.74  5020.1  295.01  5047.7  294.29  5080.4  294.45
  5153.2  295.74  5188.3  297.06  5248.7  298.13  5286.9  299.83  5361.8  301.37
  5408.8  303.75  5449.7  304.61  5462.3  305.95  5472.3  305.24  5502.5  306.05
#Mann=10,-1,0
  4391.7    0.05       0  4550.2    0.07       0  4693.3   0.035       0
  4806.0    0.05       0  4958.3    0.12       0  4987.6    0.05       0
  4992.1    0.12       0  5188.3    0.07       0  5286.9    0.05       0
  5408.8    0.07       0
Bank Sta=4987.6,4992.1
Exp/Cntr=0.3,0.1

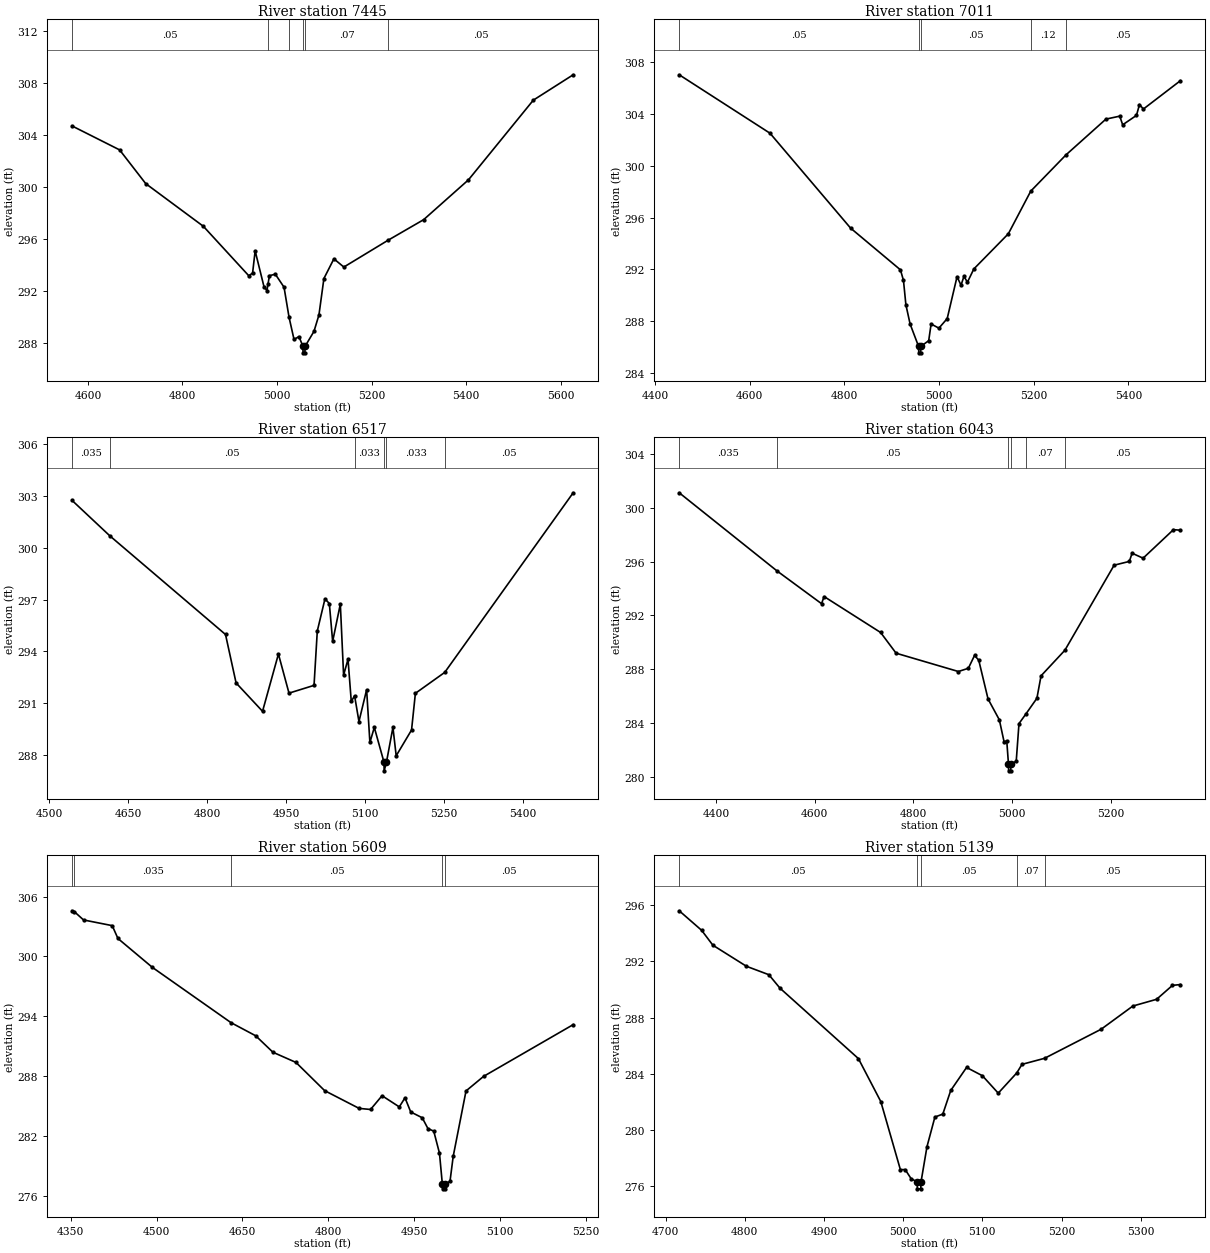
Type RM Length L Ch R = 1,7445,434,434,434
BEGIN DESCRIPTION:
Stream0819 16.0
END DESCRIPTION:
XS GIS Cut Line= 3
      2467024.98     13583325.01      2467425.00     13583175.00
      2468025.02     13582974.99
#Sta/Elev= 30
  4566.5  304.69  4667.1  302.85  4722.3  300.26  4844.2  296.98  4940.3  293.18
  4948.3  293.39  4953.7  295.09  4972.4  292.34  4978.6  292.04  4980.8  292.52
  4983.9  293.19  4996.4  293.30  5014.8  292.30  5025.4  289.99  5035.9  288.29
  5046.4  288.51  5054.7  287.76  5055.0  287.26  5058.9  287.26  5059.3  287.76
  5078.1  288.91  5088.6  290.17  5099.1  292.97  5120.2  294.48  5141.3  293.85
  5234.8  295.91  5310.0  297.49  5404.8  300.55  5541.9  306.67  5626.2  308.62
#Mann=6,-1,0
  4566.5    0.05       0  4980.8    0.12       0  5025.4    0.07       0
  5054.7    0.05       0  5059.3    0.07       0  5234.8    0.05       0
Bank Sta=5054.7,5059.3
Exp/Cntr=0.3,0.1

Type RM Length L Ch R = 1,7011,494,494,494
BEGIN DESCRIPTION:
Stream0819 15.0
END DESCRIPTION:
XS GIS Cut Line= 3
      2467075.00     13583575.00      2467625.00     13583475.00
      2468024.99     13583175.01
#Sta/Elev= 30
  4450.8  307.05  4642.6  302.53  4812.9  295.19  4918.3  291.96  4924.7  291.14
  4929.8  289.26  4938.7  287.77  4956.6  286.04  4957.0  285.54  4961.0  285.54
  4961.3  286.04  4978.0  286.48  4983.1  287.77  4999.6  287.45  5017.1  288.19
  5037.9  291.43  5046.3  290.77  5052.5  291.46  5059.8  291.00  5073.4  292.03
  5146.3  294.75  5193.7  298.05  5268.3  300.86  5352.5  303.62  5381.7  303.85
  5387.9  303.18  5417.1  303.91  5423.4  304.75  5431.7  304.40  5509.8  306.59
#Mann=5,-1,0
  4450.8    0.05       0  4956.6    0.05       0  4961.3    0.05       0
  5193.7    0.12       0  5268.3    0.05       0
Bank Sta=4956.6,4961.3
Exp/Cntr=0.3,0.1

Type RM Length L Ch R = 1,6517,474,474,474
BEGIN DESCRIPTION:
Stream0819 14.0
END DESCRIPTION:
XS GIS Cut Line= 3
      2467274.99     13583875.00      2467725.00     13583925.00
      2468125.02     13583624.99
#Sta/Elev= 30
  4543.2  302.73  4615.1  300.68  4835.0  294.98  4855.1  292.18  4905.4  290.54
  4935.6  293.85  4955.7  291.59  5003.3  292.04  5009.5  295.18  5024.1  297.04
  5032.4  296.77  5038.7  294.58  5053.3  296.74  5059.5  292.63  5067.9  293.55
  5074.1  291.11  5080.4  291.44  5088.7  289.95  5103.3  291.79  5109.5  288.74
  5117.9  289.61  5136.3  287.60  5136.6  287.10  5141.0  287.60  5153.3  289.61
  5159.5  287.97  5188.7  289.46  5196.0  291.58  5251.8  292.79  5496.0  303.17
#Mann=6,-1,0
  4543.2   0.035       0  4615.1    0.05       0  5080.4   0.033       0
  5136.3    0.05       0  5141.0   0.033       0  5251.8    0.05       0
Bank Sta=5136.3,5141
Exp/Cntr=0.3,0.1

Type RM Length L Ch R = 1,6043,434,434,434
BEGIN DESCRIPTION:
Stream0819 13.0
END DESCRIPTION:
XS GIS Cut Line= 3
      2467274.98     13584124.99      2467925.00     13584325.00
      2468224.99     13584175.00
#Sta/Elev= 30
  4325.5  301.11  4523.8  295.30  4613.9  292.87  4619.1  293.40  4733.6  290.73
  4765.0  289.19  4891.2  287.83  4911.4  288.07  4923.9  289.02  4932.4  288.68
  4951.3  285.79  4974.2  284.24  4984.0  282.57  4989.2  282.69  4992.7  280.95
  4993.0  280.45  4997.2  280.45  4997.6  280.95  5008.4  281.16  5014.0  283.96
  5027.5  284.65  5050.3  285.84  5058.7  287.51  5107.0  289.41  5206.8  295.73
  5237.6  296.01  5243.2  296.62  5265.5  296.25  5327.0  298.37  5341.0  298.33
#Mann=6,-1,0
  4325.5   0.035       0  4523.8    0.05       0  4992.7    0.05       0
  4997.6    0.05       0  5027.5    0.07       0  5107.0    0.05       0
Bank Sta=4992.7,4997.6
Exp/Cntr=0.3,0.1

Type RM Length L Ch R = 1,5609,470,470,470
BEGIN DESCRIPTION:
Stream0819 12.0
END DESCRIPTION:
XS GIS Cut Line= 3
      2467175.00     13584675.00      2467825.00     13584725.00
      2468024.98     13584824.99
#Sta/Elev= 30
  4352.2  304.58  4356.2  304.49  4372.3  303.66  4422.4  303.09  4432.4  301.80
  4492.6  298.90  4629.9  293.36  4673.1  292.04  4703.2  290.39  4743.4  289.37
  4793.5  286.54  4853.7  284.76  4873.7  284.65  4893.8  286.03  4923.9  284.91
  4933.9  285.82  4943.9  284.40  4964.0  283.82  4974.0  282.73  4984.1  282.48
  4994.1  280.27  4999.1  277.19  4999.5  276.69  5003.7  276.69  5004.1  277.19
  5012.5  277.44  5018.1  279.95  5040.5  286.51  5071.2  287.97  5227.7  293.16
#Mann=5,-1,0
  4352.2    0.05       0  4356.2   0.035       0  4629.9    0.05       0
  4999.1    0.05       0  5004.1    0.05       0
Bank Sta=4999.1,5004.1
Exp/Cntr=0.3,0.1

Type RM Length L Ch R = 1,5139,466,466,466
BEGIN DESCRIPTION:
Stream0819 11.0
END DESCRIPTION:
XS GIS Cut Line= 3
      2467324.98     13584874.98      2467525.00     13585075.00
      2467875.03     13585075.00
#Sta/Elev= 30
  4717.2  295.60  4745.5  294.21  4759.7  293.15  4802.1  291.65  4830.4  291.05
  4844.5  290.09  4943.5  285.08  4971.8  282.02  4996.5  277.18  5002.6  277.18
  5010.1  276.53  5017.6  276.31  5018.0  275.81  5022.2  275.81  5022.6  276.31
  5030.1  278.81  5040.1  280.92  5050.1  281.13  5060.1  282.81  5080.1  284.45
  5100.1  283.86  5120.1  282.62  5143.5  284.06  5150.1  284.67  5178.6  285.10
  5250.1  287.17  5290.1  288.82  5320.1  289.30  5340.1  290.29  5350.1  290.35
#Mann=5,-1,0
  4717.2    0.05       0  5017.6    0.05       0  5022.6    0.05       0
  5143.5    0.07       0  5178.6    0.05       0
Bank Sta=5017.6,5022.6
Exp/Cntr=0.3,0.1

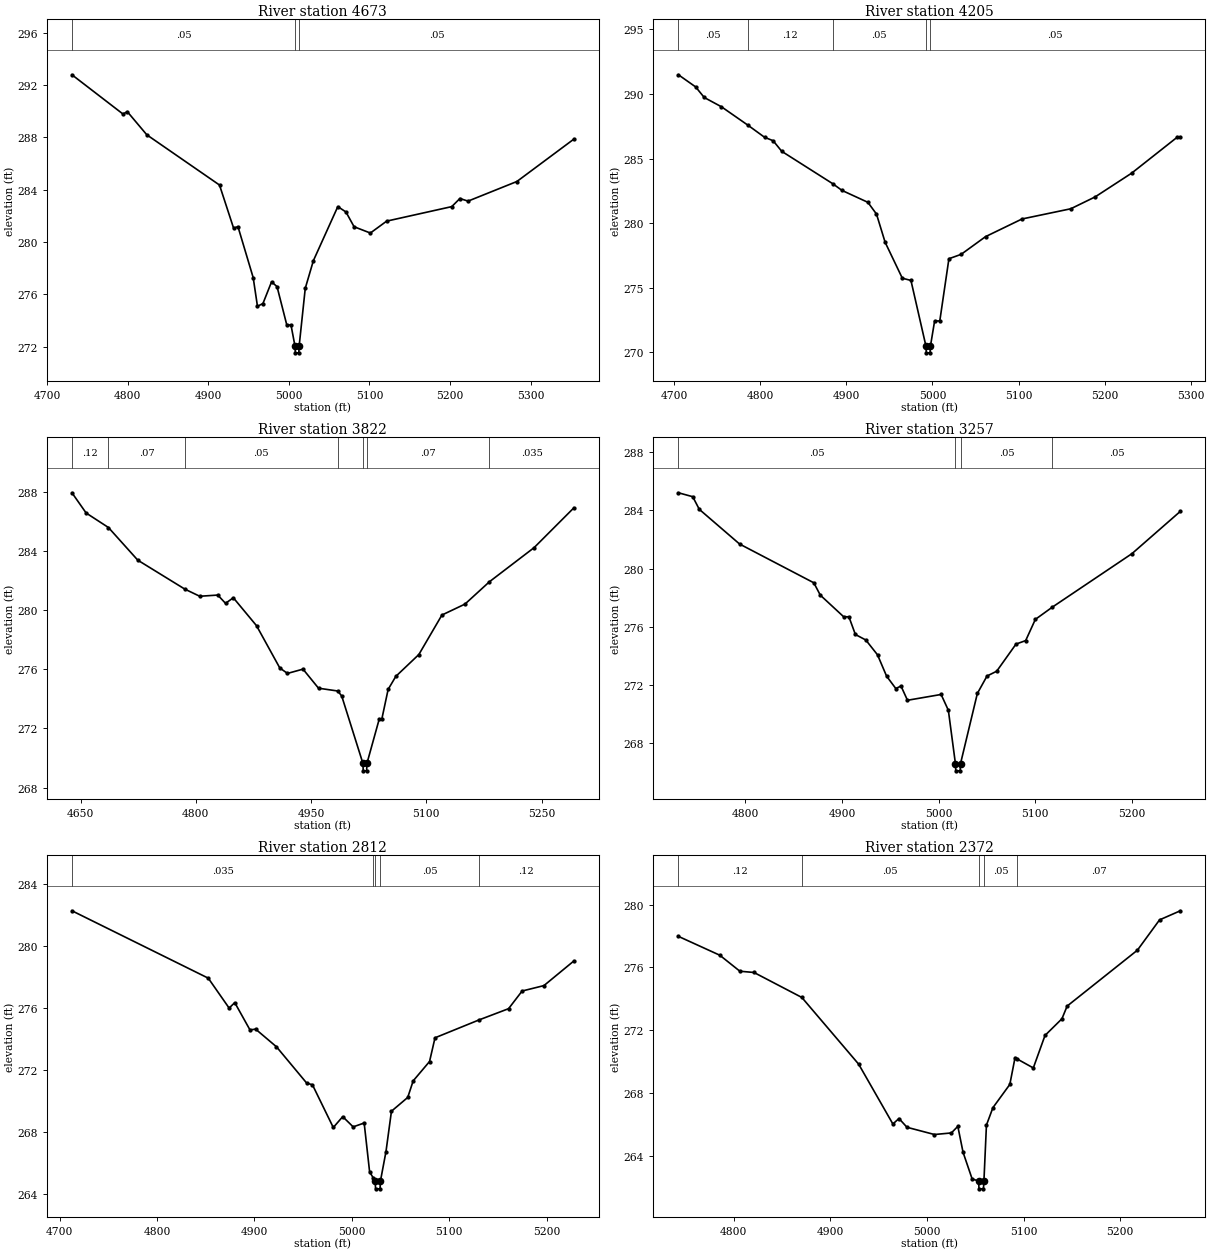
Type RM Length L Ch R = 1,4673,468,468,468
BEGIN DESCRIPTION:
Stream0819 10.0
END DESCRIPTION:
XS GIS Cut Line= 3
      2467224.98     13585424.99      2467475.00     13585525.00
      2467824.96     13585475.01
#Sta/Elev= 30
  4730.8  292.79  4794.1  289.79  4799.5  289.97  4823.7  288.20  4913.9  284.36
  4931.4  281.06  4936.8  281.18  4955.7  277.28  4961.0  275.09  4967.8  275.30
  4978.5  276.96  4985.3  276.59  4997.4  273.66  5002.6  273.66  5007.6  272.03
  5008.0  271.53  5012.3  271.53  5012.7  272.03  5020.3  276.46  5030.4  278.58
  5060.7  282.71  5070.8  282.30  5080.9  281.17  5101.1  280.69  5121.3  281.60
  5202.1  282.71  5212.2  283.33  5222.3  283.13  5282.9  284.63  5353.6  287.87
#Mann=3,-1,0
  4730.8    0.05       0  5007.6    0.05       0  5012.7    0.05       0
Bank Sta=5007.6,5012.7
Exp/Cntr=0.3,0.1

Type RM Length L Ch R = 1,4205,383,383,383
BEGIN DESCRIPTION:
Stream0819 9.0
END DESCRIPTION:
XS GIS Cut Line= 3
      2467374.99     13585925.00      2467675.00     13585925.00
      2467874.97     13585725.03
#Sta/Elev= 30
  4705.0  291.49  4725.0  290.55  4735.0  289.73  4755.0  289.01  4785.8  287.58
  4805.0  286.65  4815.0  286.38  4825.0  285.56  4884.0  283.06  4895.0  282.53
  4925.0  281.61  4935.0  280.70  4945.0  278.52  4965.0  275.73  4975.0  275.56
  4992.5  270.45  4992.8  269.95  4997.2  269.95  4997.6  270.45  5002.5  272.42
  5008.5  272.42  5019.1  277.24  5033.3  277.58  5061.6  278.95  5104.0  280.32
  5160.6  281.11  5188.9  282.03  5231.3  283.87  5284.3  286.66  5287.8  286.66
#Mann=5,-1,0
  4705.0    0.05       0  4785.8    0.12       0  4884.0    0.05       0
  4992.5    0.05       0  4997.6    0.05       0
Bank Sta=4992.5,4997.6
Exp/Cntr=0.3,0.1

Type RM Length L Ch R = 1,3822,565,565,565
BEGIN DESCRIPTION:
Stream0819 8.0
END DESCRIPTION:
XS GIS Cut Line= 3
      2467416.62     13586320.84      2467816.67     13586270.83
      2468066.71     13586270.83
#Sta/Elev= 30
  4638.8  287.94  4657.3  286.57  4686.3  285.59  4724.5  283.38  4785.8  281.42
  4805.1  280.94  4828.6  281.02  4838.7  280.46  4848.8  280.84  4879.0  278.95
  4909.3  276.09  4919.3  275.72  4939.5  276.01  4959.7  274.72  4984.8  274.53
  4989.9  274.19  5017.5  269.63  5017.9  269.13  5022.3  269.13  5022.7  269.63
  5038.6  272.61  5042.0  272.61  5050.3  274.64  5060.3  275.52  5090.3  277.00
  5120.3  279.67  5150.3  280.41  5182.1  281.92  5240.3  284.23  5292.0  286.92
#Mann=7,-1,0
  4638.8    0.12       0  4686.3    0.07       0  4785.8    0.05       0
  4984.8    0.07       0  5017.5    0.05       0  5022.7    0.07       0
  5182.1   0.035       0
Bank Sta=5017.5,5022.7
Exp/Cntr=0.3,0.1

Type RM Length L Ch R = 1,3257,445,445,445
BEGIN DESCRIPTION:
Stream0819 7.0
END DESCRIPTION:
XS GIS Cut Line= 3
      2467474.96     13586724.99      2467725.00     13586825.00
      2467975.00     13586825.00
#Sta/Elev= 30
  4730.7  285.22  4745.5  284.95  4752.3  284.08  4794.0  281.69  4870.8  279.02
  4877.5  278.17  4901.7  276.68  4907.1  276.68  4913.8  275.46  4924.6  275.08
  4936.7  274.06  4946.1  272.59  4955.6  271.74  4961.0  271.91  4967.7  270.93
  5002.5  271.33  5010.0  270.24  5017.3  266.57  5017.7  266.07  5022.2  266.07
  5022.6  266.57  5040.0  271.40  5050.0  272.60  5060.0  272.93  5080.0  274.80
  5090.0  275.04  5100.0  276.50  5117.7  277.35  5200.0  281.03  5250.0  283.94
#Mann=4,-1,0
  4730.7    0.05       0  5017.3    0.05       0  5022.6    0.05       0
  5117.7    0.05       0
Bank Sta=5017.3,5022.6
Exp/Cntr=0.3,0.1

Type RM Length L Ch R = 1,2812,440,440,440
BEGIN DESCRIPTION:
Stream0819 6.0
END DESCRIPTION:
XS GIS Cut Line= 3
      2467325.02     13587075.01      2467575.00     13587225.00
      2467674.99     13587424.97
#Sta/Elev= 30
  4712.7  282.27  4852.6  277.92  4874.0  275.99  4879.8  276.34  4895.4  274.58
  4901.2  274.63  4922.6  273.49  4953.7  271.14  4959.5  271.04  4980.9  268.28
  4990.6  268.98  5001.3  268.32  5012.6  268.57  5018.2  265.41  5022.0  265.02
  5023.9  264.82  5024.3  264.32  5028.9  264.32  5029.3  264.82  5035.0  266.73
  5040.6  269.33  5057.3  270.22  5062.9  271.29  5079.7  272.54  5085.3  274.07
  5130.3  275.22  5160.8  275.95  5174.7  277.09  5197.1  277.44  5227.8  279.03
#Mann=5,-1,0
  4712.7   0.035       0  5022.0    0.05       0  5023.9   0.035       0
  5029.3    0.05       0  5130.3    0.12       0
Bank Sta=5023.9,5029.3
Exp/Cntr=0.3,0.1

Type RM Length L Ch R = 1,2372,459,459,459
BEGIN DESCRIPTION:
Stream0819 5.0
END DESCRIPTION:
XS GIS Cut Line= 3
      2467124.97     13587324.96      2467275.00     13587525.00
      2467525.00     13587625.00
#Sta/Elev= 30
  4742.9  277.98  4785.7  276.78  4806.5  275.76  4821.1  275.68  4870.6  274.09
  4929.4  269.84  4964.8  266.03  4971.1  266.38  4979.4  265.82  5007.8  265.36
  5025.3  265.46  5032.0  265.88  5037.4  264.23  5046.8  262.53  5053.5  262.40
  5053.9  261.90  5058.5  261.90  5059.0  262.40  5061.6  265.96  5068.3  267.07
  5085.8  268.55  5091.2  270.26  5093.7  270.16  5110.1  269.60  5122.2  271.67
  5139.7  272.73  5145.1  273.54  5217.8  277.10  5240.7  279.03  5262.2  279.61
#Mann=5,-1,0
  4742.9    0.12       0  4870.6    0.05       0  5053.5    0.05       0
  5059.0    0.05       0  5093.7    0.07       0
Bank Sta=5053.5,5059
Exp/Cntr=0.3,0.1