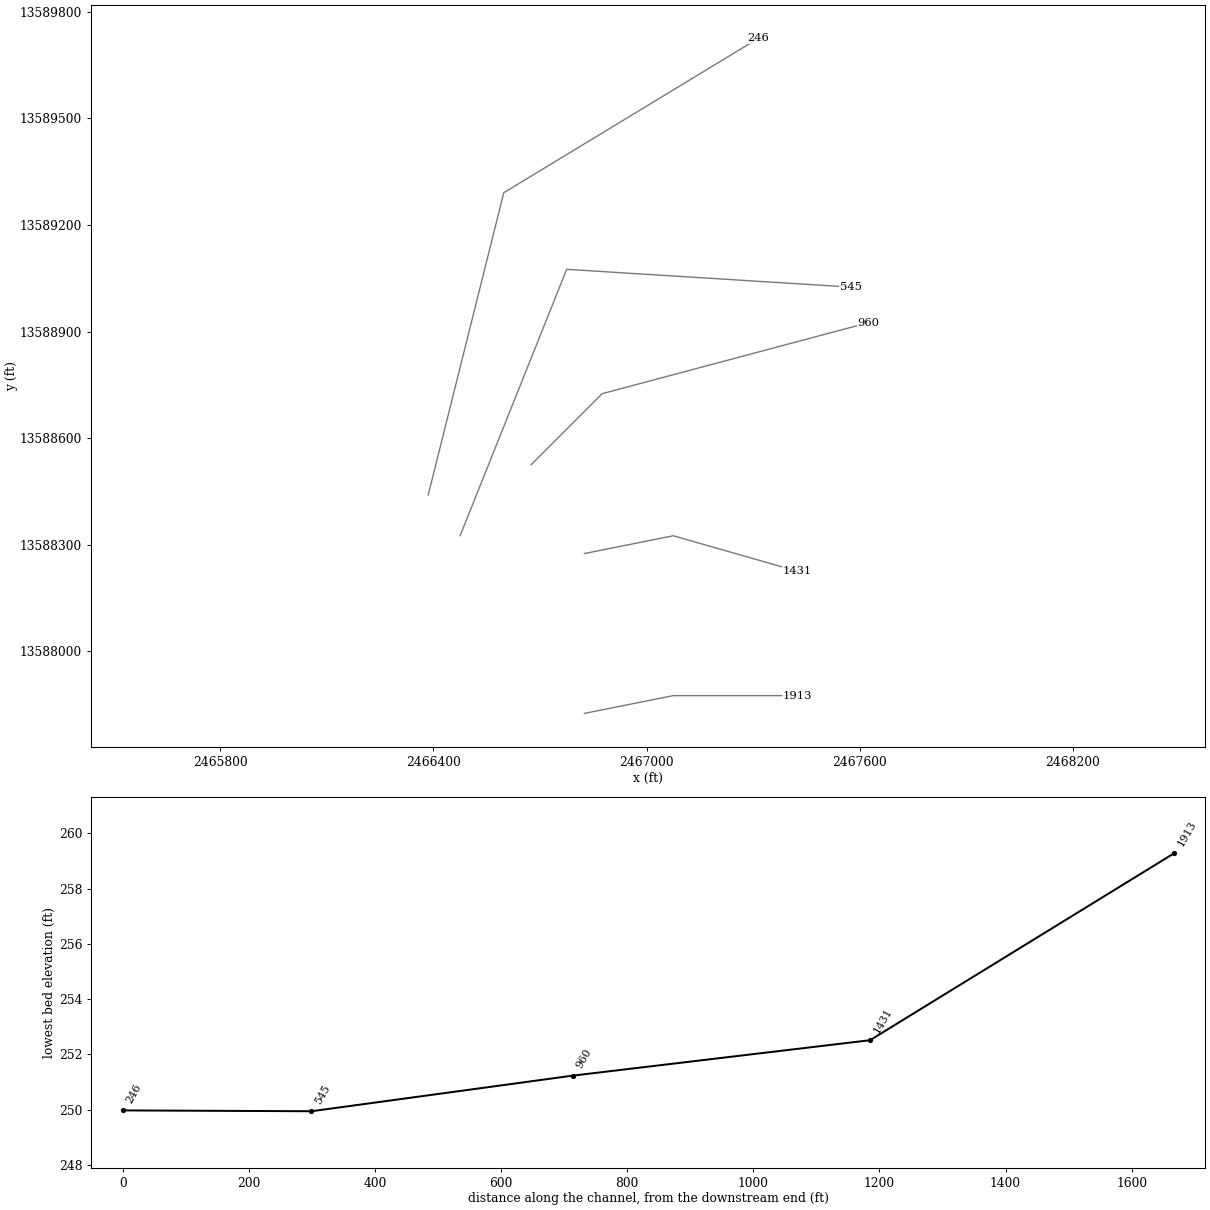
HEC-RAS study Stream0819.prj: Stream0819 Base Level Engineering

--- Stream0819.g01 (geometry) --- (continued)

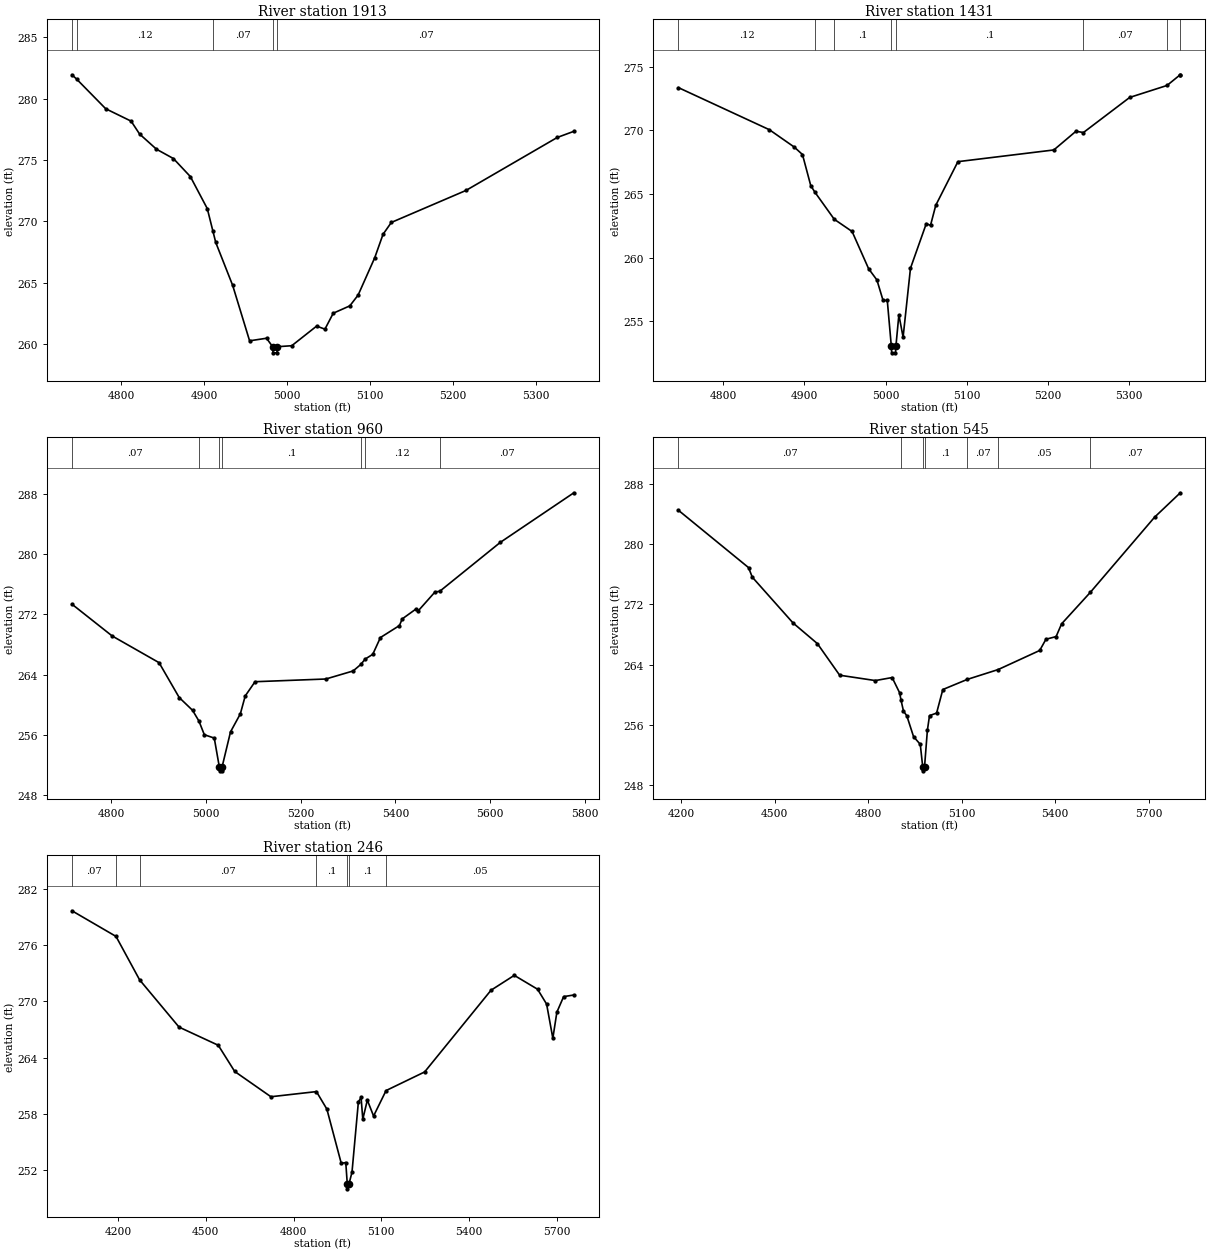
Type RM Length L Ch R = 1,1913,482,482,482
BEGIN DESCRIPTION:
Stream0819 4.0
END DESCRIPTION:
XS GIS Cut Line= 3
      2466825.05     13587825.01      2467075.00     13587875.00
      2467425.00     13587875.00
#Sta/Elev= 30
  4740.5  281.94  4746.1  281.59  4781.2  279.17  4811.8  278.16  4822.0  277.11
  4842.4  275.87  4862.8  275.11  4883.2  273.64  4903.6  271.03  4910.4  269.19
  4913.8  268.27  4934.2  264.77  4954.6  260.25  4975.0  260.46  4982.4  259.77
  4982.9  259.27  4987.6  259.27  4988.0  259.77  5005.4  259.85  5035.4  261.45
  5045.4  261.20  5055.4  262.50  5075.4  263.10  5085.4  263.98  5105.4  267.02
  5115.4  268.93  5125.4  269.90  5215.4  272.51  5325.4  276.83  5345.4  277.33
#Mann=5,-1,0
  4740.5    0.07       0  4746.1    0.12       0  4910.4    0.07       0
  4982.4    0.05       0  4988.0    0.07       0
Bank Sta=4982.4,4988
Exp/Cntr=0.3,0.1

Type RM Length L Ch R = 1,1431,471,471,471
BEGIN DESCRIPTION:
Stream0819 3.0
END DESCRIPTION:
XS GIS Cut Line= 3
      2466824.95     13588274.99      2467075.00     13588325.00
      2467425.00     13588225.00
#Sta/Elev= 30
  4744.6  273.36  4856.8  270.05  4887.4  268.69  4897.6  268.10  4907.8  265.66
  4912.7  265.16  4936.8  263.01  4958.8  262.05  4979.2  259.12  4989.4  258.24
  4997.0  256.63  5002.2  256.63  5007.2  253.01  5007.6  252.51  5012.3  252.51
  5012.8  253.01  5016.5  255.50  5021.7  253.74  5030.8  259.16  5050.3  262.67
  5055.5  262.53  5062.0  264.11  5089.3  267.54  5207.6  268.46  5234.9  269.93
  5244.1  269.83  5301.2  272.59  5347.2  273.53  5363.4  274.37  5363.6  274.37
#Mann=8,-1,0
  4744.6    0.12       0  4912.7   0.035       0  4936.8     0.1       0
  5007.2    0.05       0  5012.8     0.1       0  5244.1    0.07       0
  5347.2    0.12       0  5363.4    0.07       0
Bank Sta=5007.2,5012.8
Exp/Cntr=0.3,0.1

Type RM Length L Ch R = 1,960,415,415,415
BEGIN DESCRIPTION:
Stream0819 2.0
END DESCRIPTION:
XS GIS Cut Line= 3
      2466675.01     13588525.01      2466875.00     13588725.00
      2467624.97     13588924.99
#Sta/Elev= 30
  4717.4  273.37  4802.2  269.15  4901.2  265.60  4943.7  260.97  4971.9  259.27
  4985.3  257.85  4996.7  256.03  5017.7  255.58  5028.4  251.73  5028.9  251.23
  5033.6  251.23  5034.1  251.73  5052.0  256.41  5072.7  258.80  5083.0  261.18
  5103.7  263.07  5253.1  263.43  5310.7  264.50  5326.8  265.36  5335.9  266.07
  5352.1  266.71  5368.3  268.94  5408.4  270.53  5414.2  271.41  5443.3  272.73
  5448.5  272.52  5483.4  274.99  5493.4  275.08  5621.2  281.58  5776.4  288.17
#Mann=7,-1,0
  4717.4    0.07       0  4985.3     0.1       0  5028.4    0.05       0
  5034.1     0.1       0  5326.8    0.07       0  5335.9    0.12       0
  5493.4    0.07       0
Bank Sta=5028.4,5034.1
Exp/Cntr=0.3,0.1

Type RM Length L Ch R = 1,545,299,299,299
BEGIN DESCRIPTION:
Stream0819 1.0
END DESCRIPTION:
XS GIS Cut Line= 3
      2466475.00     13588325.01      2466775.00     13589075.00
      2467574.98     13589025.00
#Sta/Elev= 30
  4191.7  284.49  4416.5  276.89  4428.6  275.62  4559.2  269.55  4637.3  266.81
  4708.7  262.62  4823.1  261.91  4877.0  262.31  4901.2  260.27  4905.2  259.36
  4913.3  257.87  4924.1  257.23  4945.6  254.48  4967.2  253.45  4975.1  250.44
  4975.5  249.94  4980.8  250.44  4990.0  255.32  4996.8  257.26  5019.5  257.60
  5039.5  260.72  5118.3  262.07  5217.0  263.37  5350.1  265.90  5370.2  267.39
  5402.7  267.74  5420.3  269.43  5512.1  273.59  5718.4  283.57  5801.0  286.81
#Mann=7,-1,0
  4191.7    0.07       0  4905.2     0.1       0  4975.1    0.05       0
  4980.8     0.1       0  5118.3    0.07       0  5217.0    0.05       0
  5512.1    0.07       0
Bank Sta=4975.1,4980.8
Exp/Cntr=0.3,0.1

Type RM Length L Ch R = 1,246,0,0,0
BEGIN DESCRIPTION:
XS7778
END DESCRIPTION:
XS GIS Cut Line= 3
      2466385.23     13588439.89      2466597.92     13589290.65
      2467314.58     13589725.27
#Sta/Elev= 30
  4042.9  279.68  4193.5  276.94  4274.1  272.30  4408.9  267.25  4542.9  265.31
  4599.1  262.51  4722.8  259.81  4878.3  260.36  4914.0  258.49  4963.2  252.69
  4978.6  252.78  4983.8  250.47  4984.2  249.97  4989.5  250.47  4999.9  251.76
  5021.7  259.26  5030.9  259.73  5036.8  257.41  5052.3  259.45  5073.6  257.75
  5116.3  260.47  5248.1  262.46  5474.9  271.19  5554.4  272.78  5633.9  271.30
  5664.9  269.71  5686.2  266.06  5700.0  268.85  5723.1  270.51  5758.0  270.68
#Mann=7,-1,0
  4042.9    0.07       0  4193.5    0.12       0  4274.1    0.07       0
  4878.3     0.1       0  4983.8    0.05       0  4989.5     0.1       0
  5116.3    0.05       0
Bank Sta=4983.8,4989.5
Exp/Cntr=0.3,0.1

Chan Stop Cuts=-1