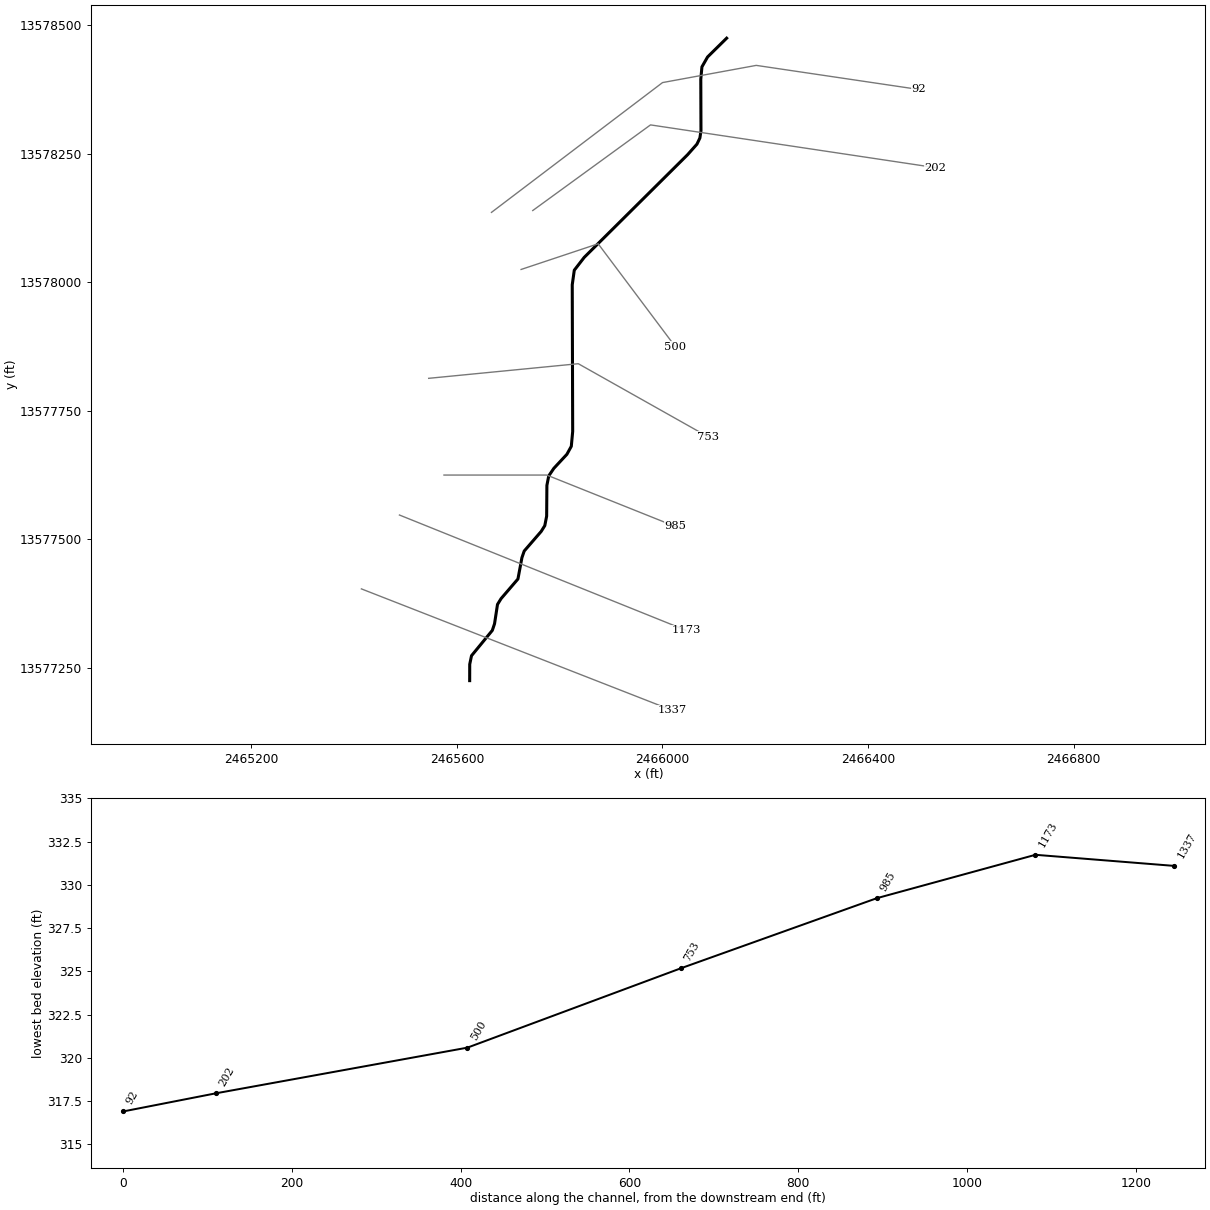
--- Stream0820.prj (project) ---

Proj Title=Stream0820 Base Level Engineering
Current Plan=p01
Default Exp/Contr=0.3,0.1
English Units
Geom File=g01
Flow File=f01
Plan File=p01
BEGIN DESCRIPTION:
Stream0820
END DESCRIPTION:

--- Stream0820.p01 (plan) ---

Plan Title=Multiple Run
Short Identifier=Multiple
Geom File=g01
Flow File=f01
Subcritical Flow
K Sum by GR= 0
Std Step Tol= 0.01
Critical Tol= 0.01
Num of Std Step Trials= 20
Max Error Tol= 0.3
Flow Tol Ratio= 0.001
Split Flow NTrial= 30
Split Flow Tol= 0.02
Split Flow Ratio= 0.02
Log Output Level= 0
Friction Slope Method= 1
Unsteady Friction Slope Method= 2
Unsteady Bridges Friction Slope Method= 1
Parabolic Critical Depth
Global Vel Dist=  1 , 1 , 1
Global Log Level= 0
CheckData=True
Encroach Param= -1, 0, 0, 0
BEGIN DESCRIPTION:
Multiple Run
END DESCRIPTION:

--- Stream0820.f01 (steady flow) ---

Flow Title=Multiple
Number of Profiles=7
Profile Names=10-year,25-year,50-year,1pct_min,100-year,1pct_plu,500-year
River Rch & RM= Stream0820,Reach-1,1337
     225     340     437     274     547    1091     844
River Rch & RM= Stream0820,Reach-1,92
     677    1097    1477     964    1923    3838    3230
Boundary for River Rch & Prof#=Stream0820,Reach-1,1
Up Type=0
Dn Type=3
Dn Slope=0.005
Boundary for River Rch & Prof#=Stream0820,Reach-1,2
Up Type=0
Dn Type=3
Dn Slope=0.005
Boundary for River Rch & Prof#=Stream0820,Reach-1,3
Up Type=0
Dn Type=3
Dn Slope=0.005
Boundary for River Rch & Prof#=Stream0820,Reach-1,4
Up Type=0
Dn Type=3
Dn Slope=0.005
Boundary for River Rch & Prof#=Stream0820,Reach-1,5
Up Type=0
Dn Type=3
Dn Slope=0.005
Boundary for River Rch & Prof#=Stream0820,Reach-1,6
Up Type=0
Dn Type=3
Dn Slope=0.005
Boundary for River Rch & Prof#=Stream0820,Reach-1,7
Up Type=0
Dn Type=3
Dn Slope=0.005

--- Stream0820.g01 (geometry) ---

Geom Title=Existing Conditions

River Reach=Stream0820,Reach-1
Reach XY= 30
      2465625.00     13577225.00      2465625.10     13577256.81
      2465628.60     13577273.51      2465669.05     13577322.75
      2465673.38     13577335.67      2465679.14     13577373.28
      2465686.08     13577384.55      2465718.92     13577422.80
      2465726.67     13577464.31      2465731.12     13577477.18
      2465764.16     13577515.35      2465771.17     13577526.58
      2465774.77     13577545.09      2465775.24     13577604.90
      2465778.86     13577623.40      2465788.83     13577638.13
      2465814.15     13577665.35      2465822.74     13577680.94
      2465825.43     13577709.82      2465824.57     13577995.18
      2465828.54     13578023.54      2465847.86     13578048.53
      2466048.83     13578248.13      2466067.19     13578268.81
      2466072.94     13578280.85      2466075.03     13578294.99
      2466074.68     13578395.13      2466076.91     13578419.21
      2466087.92     13578438.50      2466125.00     13578475.00

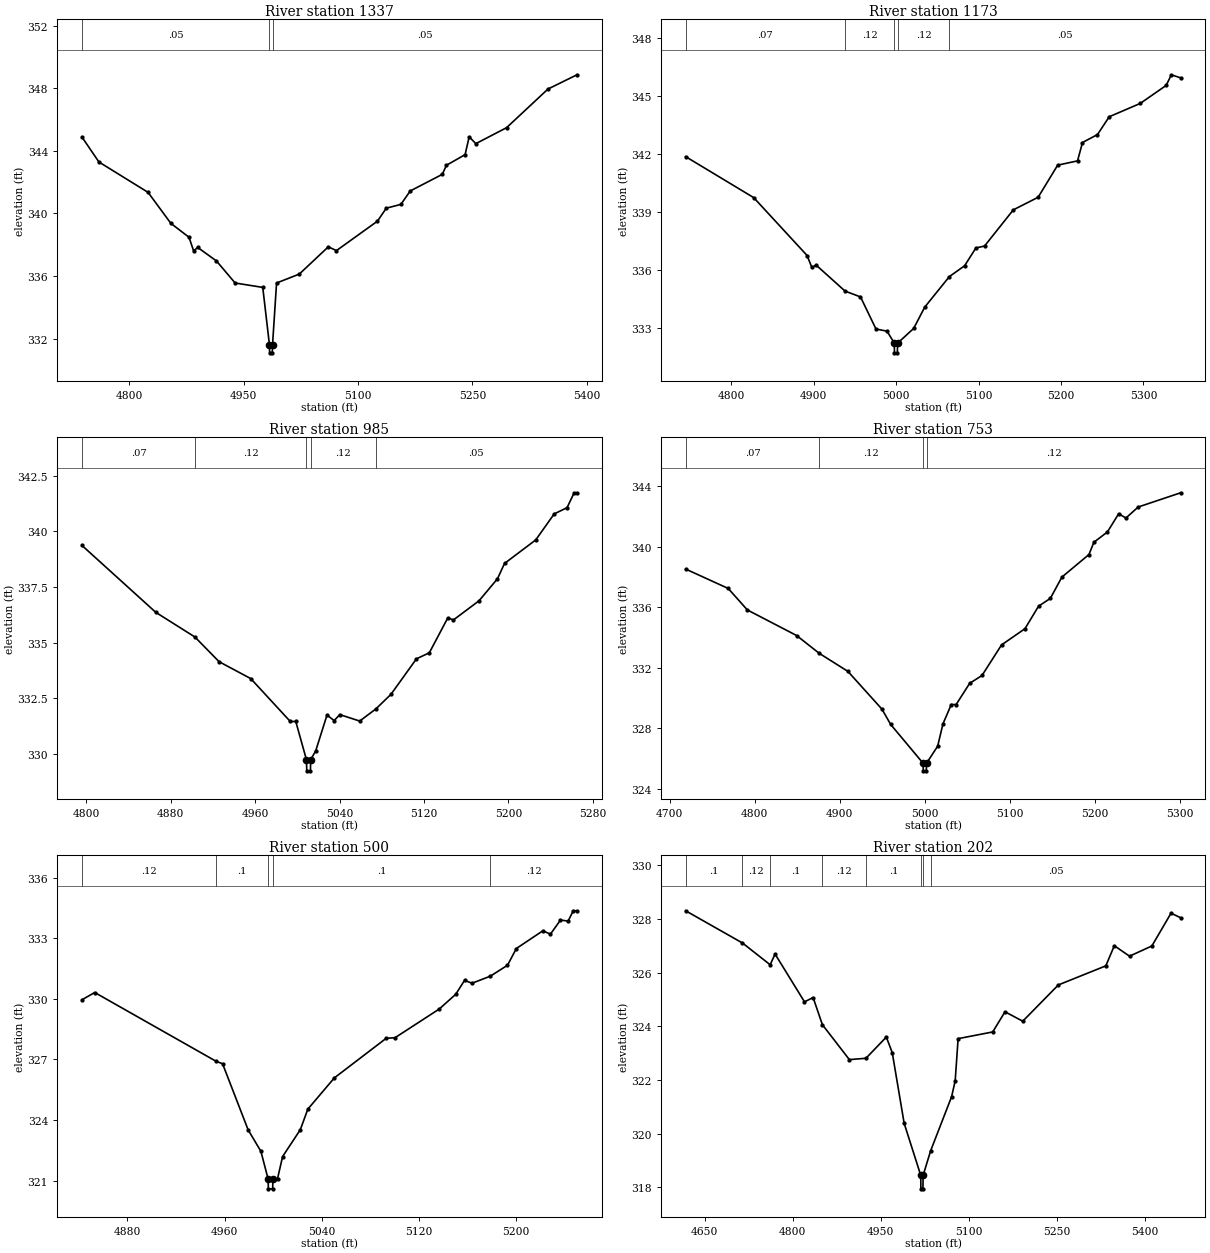
Type RM Length L Ch R = 1,1337,164,164,164
BEGIN DESCRIPTION:
XS7781
END DESCRIPTION:
XS GIS Cut Line= 2
      2465414.33     13577403.52      2466018.53     13577167.39
#Sta/Elev= 30
  4738.3  344.88  4760.5  343.29  4824.9  341.35  4854.8  339.37  4878.6  338.48
  4884.6  337.61  4890.0  337.83  4914.5  336.97  4939.0  335.56  4975.2  335.28
  4984.0  331.60  4984.2  331.10  4987.7  331.10  4988.0  331.60  4993.3  335.56
  5023.1  336.13  5061.1  337.87  5071.8  337.63  5125.5  339.51  5137.1  340.34
  5156.2  340.58  5168.5  341.44  5210.5  342.50  5215.9  343.08  5240.4  343.76
  5245.7  344.90  5254.4  344.46  5294.7  345.48  5349.0  347.95  5387.0  348.86
#Mann=3,-1,0
  4738.3    0.05       0  4984.0    0.05       0  4988.0    0.05       0
Bank Sta=4984,4988
Exp/Cntr=0.3,0.1

Type RM Length L Ch R = 1,1173,188,188,188
BEGIN DESCRIPTION:
H21102
END DESCRIPTION:
XS GIS Cut Line= 2
      2465488.36     13577547.24      2466045.45     13577323.07
#Sta/Elev= 30
  4744.7  341.88  4827.3  339.76  4892.0  336.77  4897.7  336.16  4903.1  336.27
  4938.1  334.93  4956.8  334.63  4975.6  332.97  4989.0  332.86  4997.8  332.24
  4998.0  331.74  5001.5  331.74  5001.8  332.24  5021.3  333.00  5034.7  334.10
  5064.6  335.68  5083.1  336.24  5096.8  337.16  5107.3  337.26  5142.2  339.13
  5172.3  339.78  5196.0  341.44  5220.1  341.66  5226.1  342.61  5244.3  343.02
  5258.5  343.94  5296.2  344.63  5327.6  345.56  5333.9  346.11  5345.2  345.95
#Mann=5,-1,0
  4744.7    0.07       0  4938.1    0.12       0  4997.8    0.05       0
  5001.8    0.12       0  5064.6    0.05       0
Bank Sta=4997.8,5001.8
Exp/Cntr=0.3,0.1

Type RM Length L Ch R = 1,985,232,232,232
BEGIN DESCRIPTION:
Stream0820 2.0
END DESCRIPTION:
XS GIS Cut Line= 3
      2465574.98     13577625.00      2465775.00     13577625.00
      2466025.02     13577524.99
#Sta/Elev= 30
  4795.8  339.37  4865.8  336.36  4902.9  335.25  4925.8  334.14  4955.8  333.38
  4993.3  331.45  4998.5  331.45  5008.6  329.73  5008.9  329.23  5012.4  329.23
  5012.6  329.73  5017.4  330.13  5028.1  331.74  5034.9  331.49  5040.2  331.76
  5059.1  331.47  5074.3  332.01  5088.7  332.67  5112.9  334.27  5125.1  334.54
  5142.6  336.11  5148.0  336.02  5172.2  336.88  5189.7  337.87  5196.4  338.56
  5226.0  339.62  5243.5  340.79  5255.7  341.07  5262.4  341.74  5265.1  341.74
#Mann=5,-1,0
  4795.8    0.07       0  4902.9    0.12       0  5008.6    0.05       0
  5012.6    0.12       0  5074.3    0.05       0
Bank Sta=5008.6,5012.6
Exp/Cntr=0.3,0.1

Type RM Length L Ch R = 1,753,253,253,253
BEGIN DESCRIPTION:
H21101
END DESCRIPTION:
XS GIS Cut Line= 3
      2465545.25     13577813.20      2465836.32     13577841.64
      2466088.46     13577699.70
#Sta/Elev= 30
  4718.9  338.51  4768.9  337.23  4791.4  335.81  4849.3  334.12  4876.0  332.94
  4909.6  331.75  4949.7  329.25  4959.8  328.25  4998.0  325.68  4998.2  325.18
  5001.7  325.18  5002.0  325.68  5015.1  326.81  5021.3  328.28  5031.1  329.56
  5036.8  329.56  5052.7  330.96  5067.2  331.48  5090.2  333.50  5117.7  334.57
  5133.7  336.06  5147.5  336.57  5161.1  337.98  5192.9  339.47  5198.7  340.28
  5214.6  340.96  5227.9  342.17  5236.3  341.88  5250.8  342.61  5300.7  343.55
#Mann=4,-1,0
  4718.9    0.07       0  4876.0    0.12       0  4998.0    0.05       0
  5002.0    0.12       0
Bank Sta=4998,5002
Exp/Cntr=0.3,0.1

Type RM Length L Ch R = 1,500,298,298,298
BEGIN DESCRIPTION:
Stream0820 1.0
END DESCRIPTION:
XS GIS Cut Line= 3
      2465725.04     13578025.01      2465875.00     13578075.00
      2466025.01     13577874.98
#Sta/Elev= 30
  4842.5  329.96  4853.0  330.32  4953.1  326.91  4958.4  326.79  4979.5  323.51
  4990.0  322.45  4995.9  321.09  4996.2  320.59  4999.7  320.59  4999.9  321.09
  5003.7  321.09  5007.9  322.19  5022.5  323.52  5028.7  324.54  5050.6  326.09
  5093.3  328.05  5100.6  328.08  5137.0  329.50  5150.6  330.23  5157.9  330.92
  5164.1  330.78  5179.2  331.13  5193.3  331.67  5200.6  332.50  5222.5  333.38
  5228.7  333.21  5237.0  333.91  5243.3  333.86  5247.5  334.37  5250.6  334.37
#Mann=5,-1,0
  4842.5    0.12       0  4953.1     0.1       0  4995.9    0.05       0
  4999.9     0.1       0  5179.2    0.12       0
Bank Sta=4995.9,4999.9
Exp/Cntr=0.3,0.1

Type RM Length L Ch R = 1,202,110,110,110
BEGIN DESCRIPTION:
XS7780
END DESCRIPTION:
XS GIS Cut Line= 3
      2465747.72     13578139.65      2465976.85     13578306.29
      2466531.23     13578223.13
#Sta/Elev= 30
  4617.7  328.30  4714.6  327.10  4761.8  326.29  4770.1  326.69  4820.3  324.91
  4835.0  325.07  4850.8  324.06  4896.8  322.76  4925.1  322.81  4959.8  323.60
  4969.9  323.02  4990.2  320.39  5018.5  318.45  5018.7  317.95  5022.2  317.95
  5022.5  318.45  5035.4  319.37  5071.1  321.38  5077.2  321.97  5082.2  323.54
  5141.2  323.79  5162.1  324.54  5192.4  324.19  5253.1  325.54  5334.0  326.25
  5348.5  327.00  5374.4  326.61  5412.5  326.99  5445.2  328.21  5461.6  328.04
#Mann=8,-1,0
  4617.7     0.1       0  4714.6    0.12       0  4761.8     0.1       0
  4850.8    0.12       0  4925.1     0.1       0  5018.5    0.05       0
  5022.5     0.1       0  5035.4    0.05       0
Bank Sta=5018.5,5022.5
Exp/Cntr=0.3,0.1

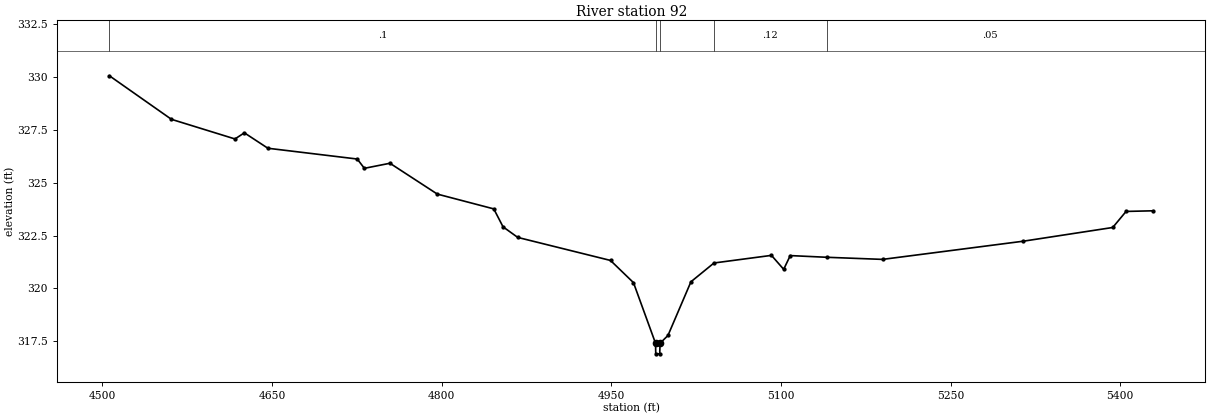
Type RM Length L Ch R = 1,92,0,0,0
BEGIN DESCRIPTION:
H21100
END DESCRIPTION:
XS GIS Cut Line= 4
      2465667.41     13578136.07      2466000.25     13578388.63
      2466182.58     13578422.08      2466498.74     13578375.24
#Sta/Elev= 30
  4506.3  330.06  4561.1  328.00  4617.3  327.07  4625.6  327.36  4646.4  326.63
  4725.4  326.12  4731.7  325.68  4754.3  325.92  4796.2  324.46  4846.1  323.76
  4854.3  322.91  4867.3  322.41  4949.3  321.32  4969.6  320.27  4989.1  317.40
  4989.3  316.90  4992.8  316.90  4993.1  317.40  5000.1  317.77  5020.4  320.31
  5040.8  321.20  5091.6  321.56  5102.4  320.90  5108.2  321.55  5140.4  321.47
  5189.8  321.37  5314.1  322.23  5393.3  322.88  5405.1  323.64  5429.1  323.67
#Mann=5,-1,0
  4506.3     0.1       0  4989.1    0.05       0  4993.1     0.1       0
  5040.8    0.12       0  5140.4    0.05       0
Bank Sta=4989.1,4993.1
Exp/Cntr=0.3,0.1

Chan Stop Cuts=-1