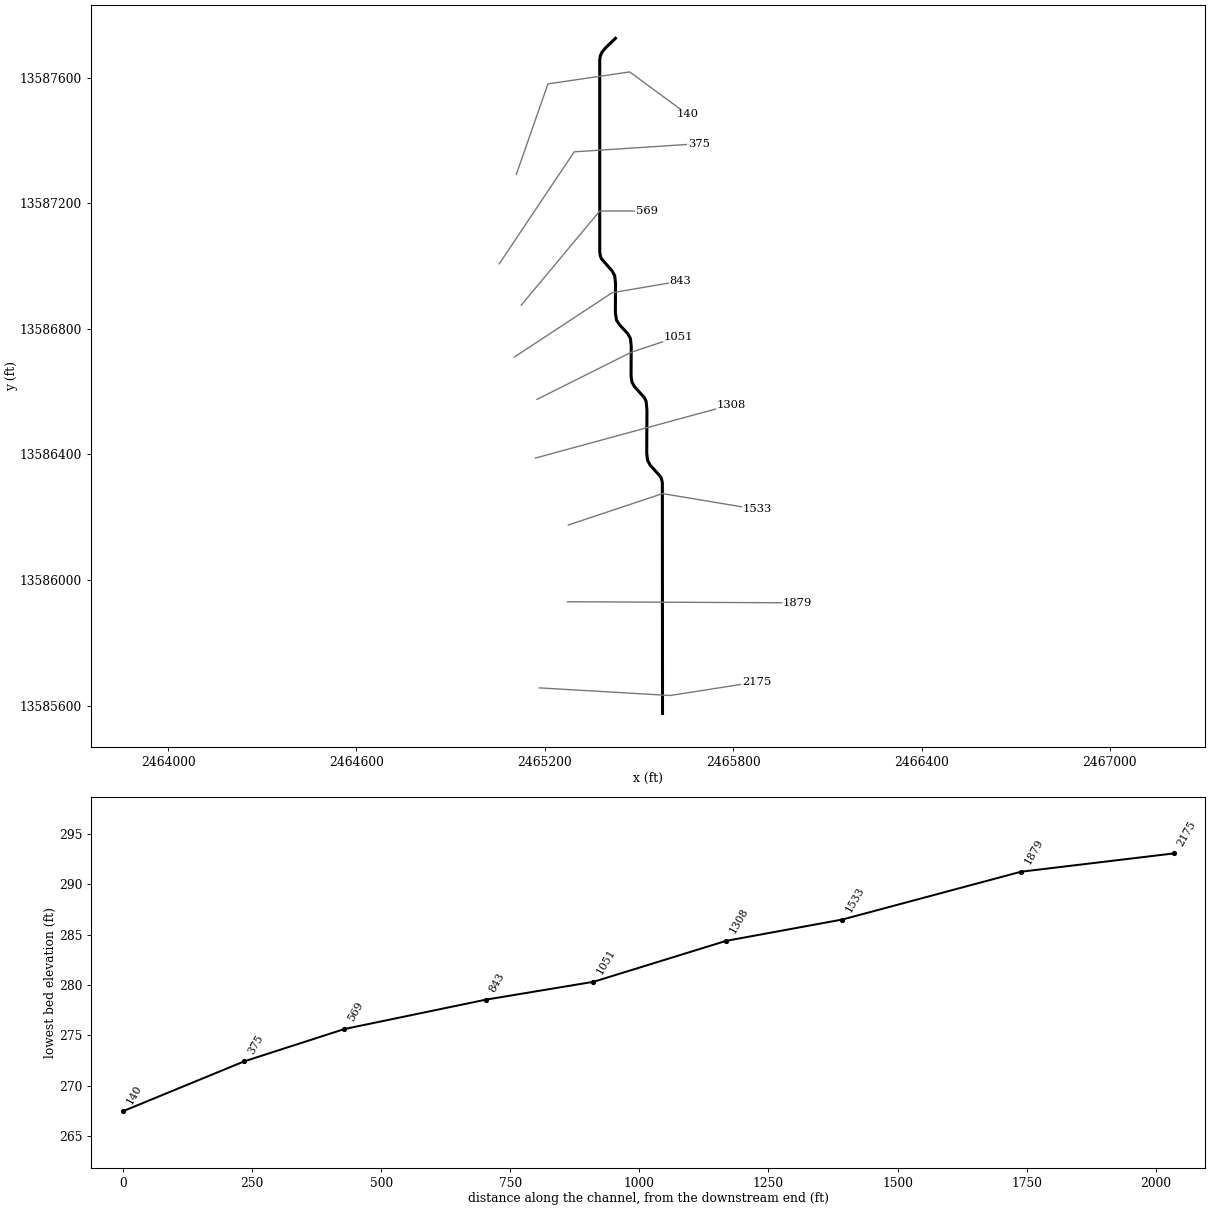
--- Stream0822.prj (project) ---

Proj Title=Stream0822 Base Level Engineering
Current Plan=p01
Default Exp/Contr=0.3,0.1
English Units
Geom File=g01
Flow File=f01
Plan File=p01
BEGIN DESCRIPTION:
Stream0822
END DESCRIPTION:

--- Stream0822.p01 (plan) ---

Plan Title=Multiple Run
Short Identifier=Multiple
Geom File=g01
Flow File=f01
Subcritical Flow
K Sum by GR= 0
Std Step Tol= 0.01
Critical Tol= 0.01
Num of Std Step Trials= 20
Max Error Tol= 0.3
Flow Tol Ratio= 0.001
Split Flow NTrial= 30
Split Flow Tol= 0.02
Split Flow Ratio= 0.02
Log Output Level= 0
Friction Slope Method= 1
Unsteady Friction Slope Method= 2
Unsteady Bridges Friction Slope Method= 1
Parabolic Critical Depth
Global Vel Dist=  1 , 1 , 1
Global Log Level= 0
CheckData=True
Encroach Param= -1, 0, 0, 0
BEGIN DESCRIPTION:
Multiple Run
END DESCRIPTION:

--- Stream0822.f01 (steady flow) ---

Flow Title=Multiple
Number of Profiles=7
Profile Names=10-year,25-year,50-year,1pct_min,100-year,1pct_plu,500-year
River Rch & RM= Stream0822,Reach-1,2175
     301     464     604     383     764    1525    1207
Boundary for River Rch & Prof#=Stream0822,Reach-1,1
Up Type=0
Dn Type=3
Dn Slope=0.005
Boundary for River Rch & Prof#=Stream0822,Reach-1,2
Up Type=0
Dn Type=3
Dn Slope=0.005
Boundary for River Rch & Prof#=Stream0822,Reach-1,3
Up Type=0
Dn Type=3
Dn Slope=0.005
Boundary for River Rch & Prof#=Stream0822,Reach-1,4
Up Type=0
Dn Type=3
Dn Slope=0.005
Boundary for River Rch & Prof#=Stream0822,Reach-1,5
Up Type=0
Dn Type=3
Dn Slope=0.005
Boundary for River Rch & Prof#=Stream0822,Reach-1,6
Up Type=0
Dn Type=3
Dn Slope=0.005
Boundary for River Rch & Prof#=Stream0822,Reach-1,7
Up Type=0
Dn Type=3
Dn Slope=0.005

--- Stream0822.g01 (geometry) ---

Geom Title=Existing Conditions

River Reach=Stream0822,Reach-1
Reach XY= 30
      2465575.00     13585575.00      2465574.48     13586309.78
      2465571.22     13586323.43      2465566.86     13586331.06
      2465535.85     13586365.35      2465527.26     13586380.94
      2465524.65     13586404.85      2465525.43     13586540.18
      2465522.74     13586569.06      2465516.86     13586581.06
      2465485.86     13586615.36      2465477.27     13586630.94
      2465474.82     13586649.93      2465475.32     13586745.13
      2465472.73     13586769.06      2465464.14     13586784.65
      2465438.80     13586811.86      2465428.79     13586826.57
      2465424.82     13586849.93      2465425.32     13586945.13
      2465422.73     13586969.06      2465414.14     13586984.64
      2465380.75     13587022.67      2465377.26     13587030.94
      2465375.07     13587045.03      2465374.98     13587655.01
      2465376.89     13587669.22      2465382.43     13587681.35
      2465394.87     13587696.03      2465425.00     13587725.00

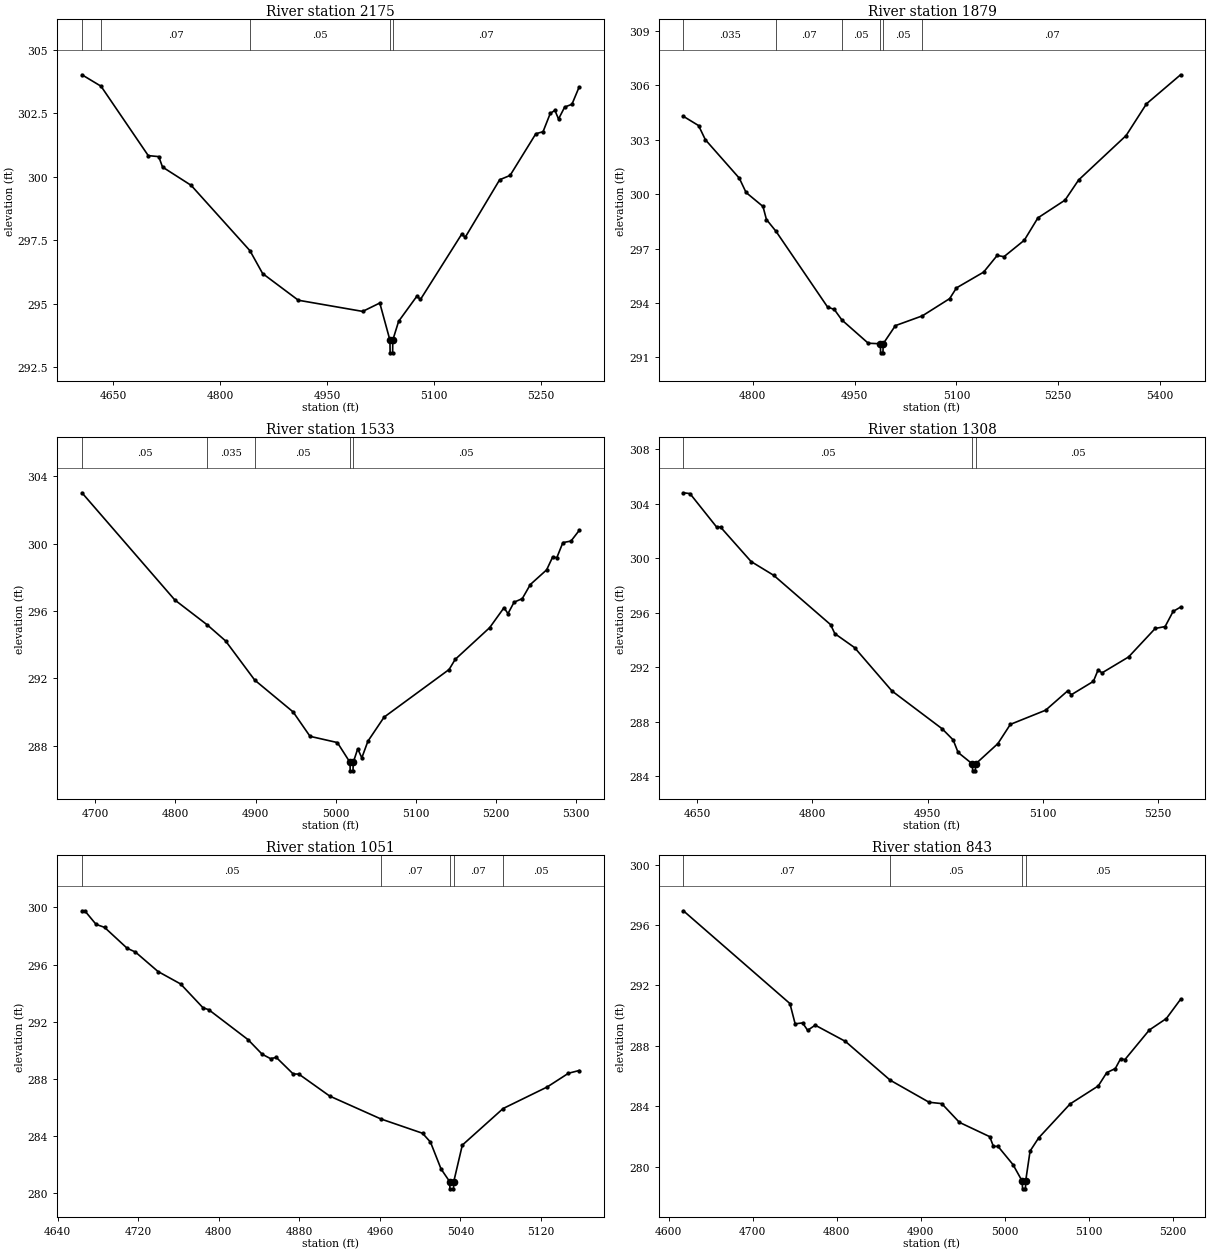
Type RM Length L Ch R = 1,2175,296,296,296
BEGIN DESCRIPTION:
Stream0822 4.0
END DESCRIPTION:
XS GIS Cut Line= 3
      2465182.27     13585656.25      2465598.96     13585631.94
      2465875.02     13585675.00
#Sta/Elev= 30
  4606.6  304.01  4633.3  303.56  4699.5  300.83  4714.2  300.79  4719.5  300.38
  4759.6  299.66  4842.0  297.09  4859.8  296.19  4909.8  295.14  5000.0  294.70
  5024.0  295.03  5038.2  293.57  5038.5  293.07  5042.0  293.07  5042.2  293.57
  5050.4  294.31  5076.0  295.30  5081.0  295.17  5138.8  297.74  5143.8  297.62
  5192.0  299.88  5206.6  300.05  5242.7  301.69  5252.8  301.77  5262.9  302.49
  5269.4  302.61  5274.5  302.27  5283.1  302.74  5293.3  302.85  5303.4  303.53
#Mann=5,-1,0
  4606.6   0.035       0  4633.3    0.07       0  4842.0    0.05       0
  5038.2    0.05       0  5042.2    0.07       0
Bank Sta=5038.2,5042.2
Exp/Cntr=0.3,0.1

Type RM Length L Ch R = 1,1879,346,346,346
BEGIN DESCRIPTION:
XS7783
END DESCRIPTION:
XS GIS Cut Line= 2
      2465272.61     13585930.56      2466005.20     13585927.08
#Sta/Elev= 30
  4697.6  304.29  4720.0  303.78  4730.0  303.00  4780.0  300.88  4790.0  300.09
  4814.9  299.32  4820.0  298.60  4834.1  297.95  4910.0  293.78  4920.0  293.64
  4931.2  293.06  4970.0  291.78  4988.0  291.75  4988.2  291.25  4991.7  291.25
  4992.0  291.75  5010.0  292.75  5049.8  293.29  5090.0  294.24  5100.0  294.83
  5140.0  295.70  5160.0  296.62  5170.0  296.55  5200.0  297.46  5220.0  298.69
  5260.0  299.67  5280.0  300.78  5350.0  303.23  5380.0  304.98  5430.2  306.58
#Mann=6,-1,0
  4697.6   0.035       0  4834.1    0.07       0  4931.2    0.05       0
  4988.0    0.05       0  4992.0    0.05       0  5049.8    0.07       0
Bank Sta=4988,4992
Exp/Cntr=0.3,0.1

Type RM Length L Ch R = 1,1533,225,225,225
BEGIN DESCRIPTION:
Stream0822 3.0
END DESCRIPTION:
XS GIS Cut Line= 3
      2465275.01     13586175.00      2465575.00     13586275.00
      2465875.05     13586224.99
#Sta/Elev= 30
  4683.4  303.02  4799.3  296.65  4839.8  295.17  4862.6  294.22  4899.0  291.89
  4946.9  290.00  4968.0  288.55  5002.1  288.18  5017.9  287.00  5018.1  286.50
  5021.6  286.50  5021.9  287.00  5027.5  287.81  5032.6  287.27  5040.2  288.26
  5060.4  289.69  5141.5  292.52  5149.1  293.12  5192.2  295.01  5210.0  296.19
  5215.0  295.84  5222.6  296.52  5232.8  296.73  5242.9  297.57  5263.2  298.44
  5270.8  299.21  5275.9  299.16  5283.5  300.06  5293.6  300.15  5303.8  300.78
#Mann=5,-1,0
  4683.4    0.05       0  4839.8   0.035       0  4899.0    0.05       0
  5017.9    0.05       0  5021.9    0.05       0
Bank Sta=5017.9,5021.9
Exp/Cntr=0.3,0.1

Type RM Length L Ch R = 1,1308,257,257,257
BEGIN DESCRIPTION:
H21105
END DESCRIPTION:
XS GIS Cut Line= 2
      2465170.07     13586388.19      2465794.40     13586557.94
#Sta/Elev= 30
  4632.1  304.79  4640.7  304.73  4675.3  302.28  4680.5  302.27  4720.3  299.74
  4749.7  298.73  4823.7  295.11  4829.2  294.45  4854.8  293.43  4903.6  290.24
  4968.8  287.47  4983.2  286.65  4989.6  285.73  5008.3  284.88  5008.5  284.38
  5012.0  284.38  5012.3  284.88  5041.4  286.38  5057.6  287.79  5103.5  288.83
  5132.0  290.24  5137.1  289.97  5165.7  290.95  5171.8  291.79  5176.9  291.57
  5211.5  292.74  5246.1  294.83  5259.0  294.97  5269.4  296.08  5279.1  296.40
#Mann=3,-1,0
  4632.1    0.05       0  5008.3    0.05       0  5012.3    0.05       0
Bank Sta=5008.3,5012.3
Exp/Cntr=0.3,0.1

Type RM Length L Ch R = 1,1051,208,208,208
BEGIN DESCRIPTION:
Stream0822 2.0
END DESCRIPTION:
XS GIS Cut Line= 3
      2465174.96     13586574.98      2465475.00     13586725.00
      2465625.03     13586775.01
#Sta/Elev= 30
  4664.2  299.77  4667.0  299.77  4678.2  298.82  4686.6  298.61  4709.0  297.15
  4717.3  296.88  4739.7  295.52  4762.1  294.65  4784.4  292.98  4790.0  292.85
  4829.1  290.75  4843.1  289.73  4851.5  289.42  4857.1  289.51  4873.9  288.35
  4879.5  288.34  4910.2  286.80  4961.0  285.20  5002.3  284.20  5010.2  283.58
  5020.7  281.70  5029.3  280.81  5029.5  280.31  5033.0  280.31  5033.3  280.81
  5041.8  283.37  5082.3  285.93  5126.1  287.44  5147.2  288.40  5157.8  288.59
#Mann=5,-1,0
  4664.2    0.05       0  4961.0    0.07       0  5029.3    0.05       0
  5033.3    0.07       0  5082.3    0.05       0
Bank Sta=5029.3,5033.3
Exp/Cntr=0.3,0.1

Type RM Length L Ch R = 1,843,274,274,274
BEGIN DESCRIPTION:
H21104
END DESCRIPTION:
XS GIS Cut Line= 3
      2465103.82     13586710.40      2465414.58     13586914.70
      2465631.62     13586951.82
#Sta/Elev= 30
  4617.3  296.94  4744.2  290.80  4750.4  289.46  4759.3  289.52  4765.3  289.03
  4774.3  289.37  4810.2  288.30  4863.6  285.73  4909.9  284.27  4925.0  284.18
  4946.0  282.94  4982.2  281.99  4986.5  281.35  4992.0  281.35  5009.9  280.14
  5020.9  279.04  5021.2  278.54  5024.7  278.54  5024.9  279.04  5030.2  281.04
  5040.4  281.91  5077.9  284.16  5111.4  285.35  5121.5  286.23  5131.7  286.50
  5138.0  287.15  5143.1  287.09  5172.2  289.05  5192.5  289.81  5209.4  291.08
#Mann=4,-1,0
  4617.3    0.07       0  4863.6    0.05       0  5020.9    0.05       0
  5024.9    0.05       0
Bank Sta=5020.9,5024.9
Exp/Cntr=0.3,0.1

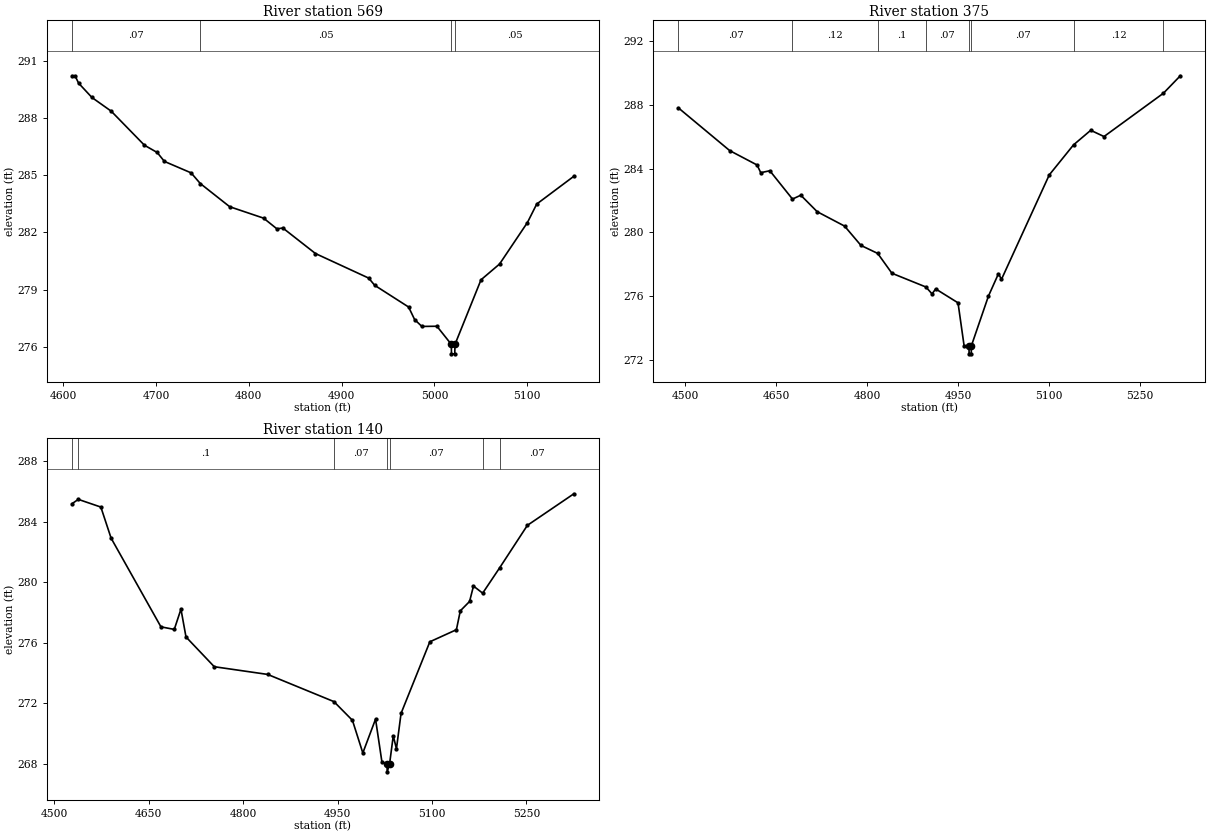
Type RM Length L Ch R = 1,569,194,194,194
BEGIN DESCRIPTION:
Stream0822 1.0
END DESCRIPTION:
XS GIS Cut Line= 3
      2465124.97     13586874.97      2465375.00     13587175.00
      2465525.05     13587175.00
#Sta/Elev= 30
  4609.5  290.23  4612.8  290.23  4616.7  289.84  4631.0  289.09  4651.8  288.37
  4687.6  286.58  4701.3  286.20  4709.1  285.73  4737.8  285.13  4747.7  284.57
  4779.4  283.35  4815.9  282.75  4830.2  282.19  4836.7  282.23  4871.8  280.89
  4929.1  279.60  4935.6  279.22  4972.1  278.08  4978.6  277.42  4986.4  277.06
  5002.6  277.07  5018.1  276.12  5018.3  275.62  5021.8  275.62  5022.1  276.12
  5050.1  279.51  5070.1  280.34  5100.1  282.52  5110.1  283.49  5150.1  284.95
#Mann=4,-1,0
  4609.5    0.07       0  4747.7    0.05       0  5018.1    0.05       0
  5022.1    0.05       0
Bank Sta=5018.1,5022.1
Exp/Cntr=0.3,0.1

Type RM Length L Ch R = 1,375,235,235,235
BEGIN DESCRIPTION:
H21103
END DESCRIPTION:
XS GIS Cut Line= 3
      2465054.96     13587006.79      2465293.74     13587363.53
      2465690.42     13587389.40
#Sta/Elev= 30
  4489.3  287.79  4573.8  285.12  4618.9  284.22  4624.9  283.74  4639.9  283.86
  4677.2  282.09  4690.9  282.33  4717.9  281.30  4763.0  280.40  4790.0  279.19
  4817.6  278.69  4841.0  277.45  4897.0  276.59  4907.1  276.16  4913.1  276.47
  4949.9  275.60  4959.9  272.92  4967.9  272.91  4968.2  272.41  4971.7  272.41
  4971.9  272.91  5000.0  276.02  5016.5  277.42  5021.5  277.07  5100.2  283.60
  5140.2  285.48  5168.5  286.39  5190.4  286.00  5288.3  288.71  5316.1  289.80
#Mann=8,-1,0
  4489.3    0.07       0  4677.2    0.12       0  4817.6     0.1       0
  4897.0    0.07       0  4967.9    0.05       0  4971.9    0.07       0
  5140.2    0.12       0  5288.3    0.07       0
Bank Sta=4967.9,4971.9
Exp/Cntr=0.3,0.1

Type RM Length L Ch R = 1,140,0,0,0
BEGIN DESCRIPTION:
XS7782
END DESCRIPTION:
XS GIS Cut Line= 4
      2465109.36     13587291.63      2465210.07     13587579.86
      2465470.49     13587618.06      2465654.51     13587482.64
#Sta/Elev= 30
  4528.2  285.20  4538.3  285.49  4574.1  284.98  4590.4  282.92  4669.5  277.05
  4690.7  276.88  4701.3  278.22  4709.3  276.38  4754.2  274.41  4839.0  273.90
  4944.2  272.10  4973.6  270.86  4990.1  268.70  5010.3  270.94  5020.4  268.11
  5028.5  267.95  5028.8  267.45  5032.5  267.95  5038.4  269.83  5043.5  268.98
  5050.8  271.32  5096.5  276.06  5138.7  276.86  5144.9  278.11  5159.6  278.73
  5165.8  279.75  5180.4  279.28  5207.4  280.96  5251.4  283.77  5325.2  285.86
#Mann=7,-1,0
  4528.2    0.12       0  4538.3     0.1       0  4944.2    0.07       0
  5028.5    0.05       0  5032.5    0.07       0  5180.4    0.12       0
  5207.4    0.07       0
Bank Sta=5028.5,5032.5
Exp/Cntr=0.3,0.1

Chan Stop Cuts=-1