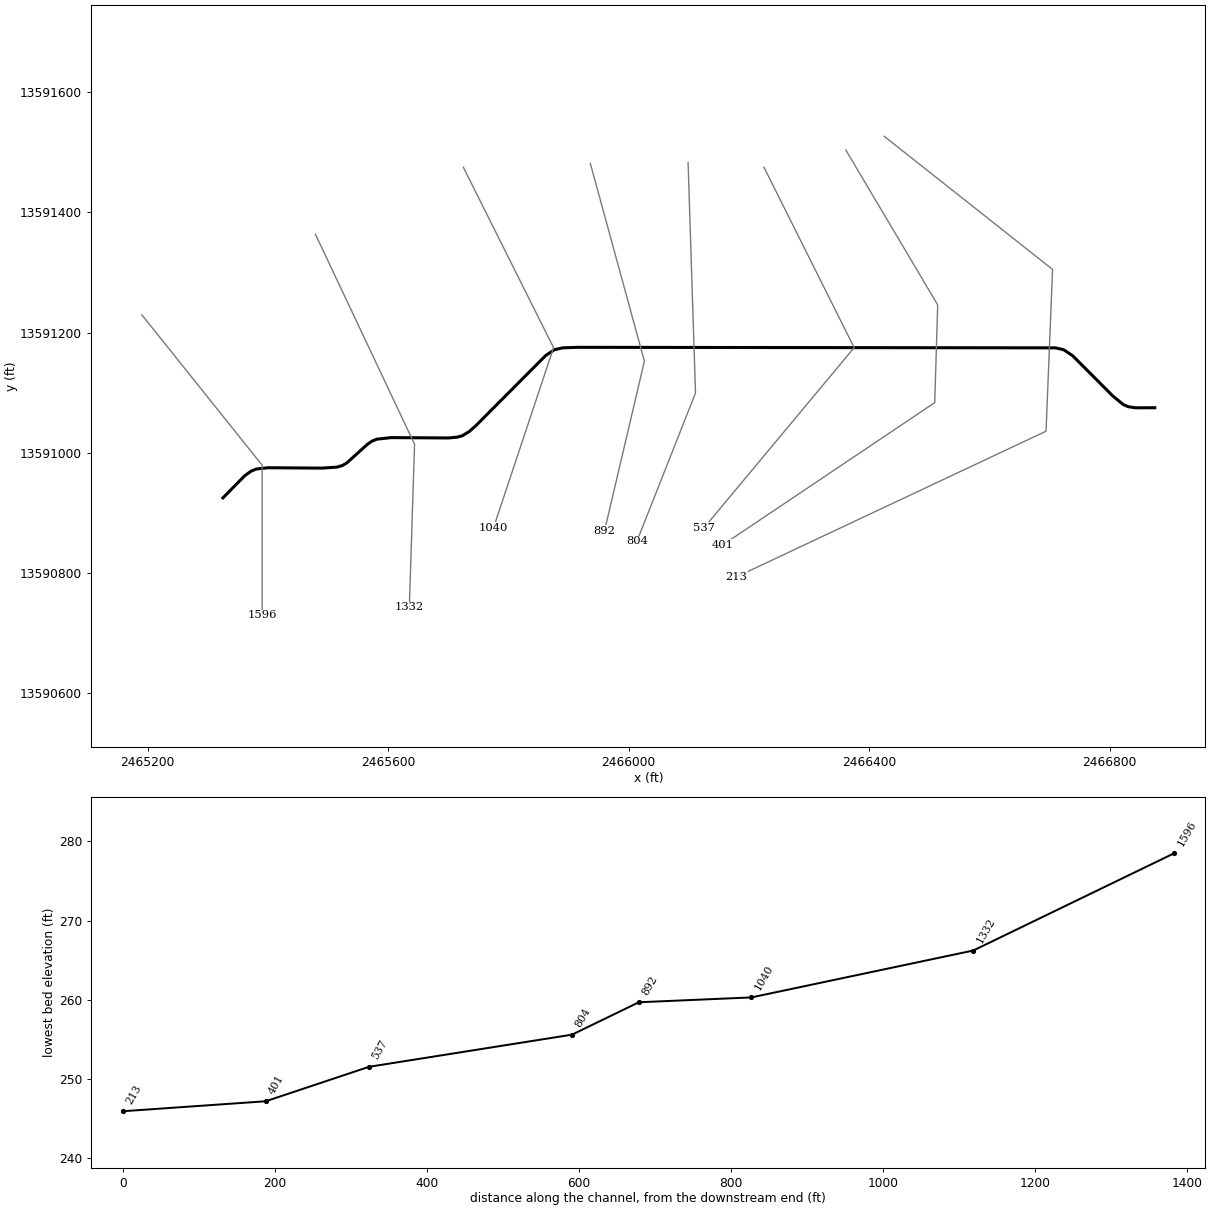
--- Stream0823.prj (project) ---

Proj Title=Stream0823 Base Level Engineering
Current Plan=p01
Default Exp/Contr=0.3,0.1
English Units
Geom File=g01
Flow File=f01
Plan File=p01
BEGIN DESCRIPTION:
Stream0823
END DESCRIPTION:

--- Stream0823.p01 (plan) ---

Plan Title=Multiple Run
Short Identifier=Multiple
Geom File=g01
Flow File=f01
Subcritical Flow
K Sum by GR= 0
Std Step Tol= 0.01
Critical Tol= 0.01
Num of Std Step Trials= 20
Max Error Tol= 0.3
Flow Tol Ratio= 0.001
Split Flow NTrial= 30
Split Flow Tol= 0.02
Split Flow Ratio= 0.02
Log Output Level= 0
Friction Slope Method= 1
Unsteady Friction Slope Method= 2
Unsteady Bridges Friction Slope Method= 1
Parabolic Critical Depth
Global Vel Dist=  1 , 1 , 1
Global Log Level= 0
CheckData=True
Encroach Param= -1, 0, 0, 0
BEGIN DESCRIPTION:
Multiple Run
END DESCRIPTION:

--- Stream0823.f01 (steady flow) ---

Flow Title=Multiple
Number of Profiles=7
Profile Names=10-year,25-year,50-year,1pct_min,100-year,1pct_plu,500-year
River Rch & RM= Stream0823,Reach-1,1596
     324     505     664     425     849    1693    1367
Boundary for River Rch & Prof#=Stream0823,Reach-1,1
Up Type=0
Dn Type=3
Dn Slope=0.005
Boundary for River Rch & Prof#=Stream0823,Reach-1,2
Up Type=0
Dn Type=3
Dn Slope=0.005
Boundary for River Rch & Prof#=Stream0823,Reach-1,3
Up Type=0
Dn Type=3
Dn Slope=0.005
Boundary for River Rch & Prof#=Stream0823,Reach-1,4
Up Type=0
Dn Type=3
Dn Slope=0.005
Boundary for River Rch & Prof#=Stream0823,Reach-1,5
Up Type=0
Dn Type=3
Dn Slope=0.005
Boundary for River Rch & Prof#=Stream0823,Reach-1,6
Up Type=0
Dn Type=3
Dn Slope=0.005
Boundary for River Rch & Prof#=Stream0823,Reach-1,7
Up Type=0
Dn Type=3
Dn Slope=0.005

--- Stream0823.g01 (geometry) ---

Geom Title=Existing Conditions

River Reach=Stream0823,Reach-1
Reach XY= 30
      2465325.00     13590925.00      2465361.50     13590962.08
      2465372.42     13590969.85      2465380.79     13590973.09
      2465399.91     13590975.21      2465490.17     13590974.60
      2465514.49     13590976.23      2465523.43     13590978.79
      2465531.05     13590983.14      2465565.35     13591014.14
      2465572.67     13591019.25      2465580.94     13591022.73
      2465604.87     13591025.32      2465700.11     13591024.73
      2465714.56     13591026.06      2465723.53     13591028.54
      2465734.80     13591035.48      2465745.16     13591044.61
      2465861.68     13591161.63      2465876.46     13591171.46
      2465890.16     13591174.62      2465914.79     13591175.50
      2466709.84     13591174.62      2466723.54     13591171.46
      2466738.32     13591161.63      2466804.93     13591094.84
      2466822.49     13591080.33      2466831.15     13591076.69
      2466843.12     13591074.93      2466875.00     13591075.00

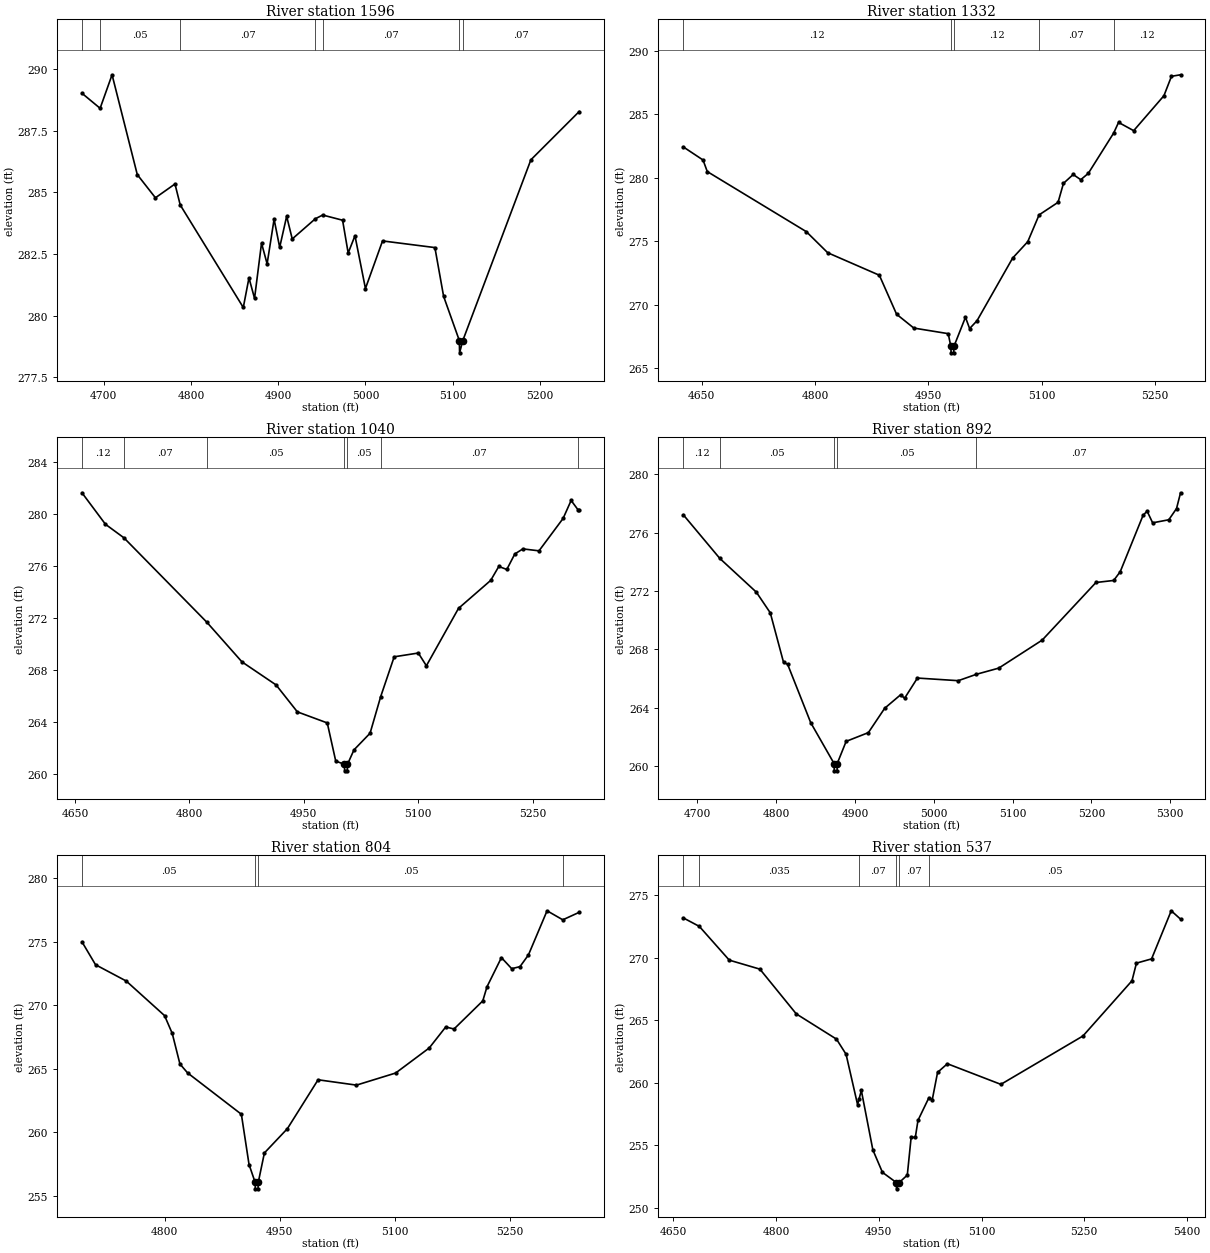
Type RM Length L Ch R = 1,1596,264,264,264
BEGIN DESCRIPTION:
Stream0823 3.0
END DESCRIPTION:
XS GIS Cut Line= 3
      2465190.34     13591229.37      2465390.36     13590979.34
      2465390.36     13590729.64
#Sta/Elev= 30
  4675.1  289.02  4695.9  288.41  4709.6  289.77  4738.5  285.72  4759.3  284.78
  4781.7  285.34  4787.7  284.49  4860.0  280.33  4866.5  281.53  4872.9  280.70
  4880.9  282.94  4887.3  282.10  4895.3  283.91  4901.7  282.77  4909.7  284.03
  4916.1  283.11  4942.6  283.93  4951.0  284.08  4973.8  283.87  4980.2  282.54
  4988.0  283.24  5000.0  281.10  5019.6  283.03  5079.6  282.76  5089.6  280.78
  5107.6  278.99  5107.9  278.49  5111.6  278.99  5189.6  286.32  5245.0  288.28
#Mann=7,-1,0
  4675.1    0.07       0  4695.9    0.05       0  4787.7    0.07       0
  4942.6    0.12       0  4951.0    0.07       0  5107.6    0.05       0
  5111.6    0.07       0
Bank Sta=5107.6,5111.6
Exp/Cntr=0.3,0.1

Type RM Length L Ch R = 1,1332,292,292,292
BEGIN DESCRIPTION:
XS7785
END DESCRIPTION:
XS GIS Cut Line= 3
      2465478.88     13591363.63      2465643.79     13591014.28
      2465635.11     13590743.04
#Sta/Elev= 30
  4625.7  282.42  4651.8  281.39  4657.4  280.48  4788.4  275.75  4816.7  274.09
  4885.0  272.32  4907.8  269.25  4930.6  268.16  4976.1  267.72  4979.6  266.71
  4979.9  266.21  4983.4  266.21  4983.6  266.71  4998.9  269.01  5004.4  268.12
  5014.2  268.74  5061.3  273.67  5081.3  274.96  5096.3  277.07  5121.4  278.06
  5128.5  279.55  5141.4  280.25  5151.4  279.84  5161.4  280.34  5195.0  283.52
  5201.4  284.35  5221.4  283.70  5261.4  286.45  5271.4  287.98  5283.4  288.10
#Mann=5,-1,0
  4625.7    0.12       0  4979.6    0.05       0  4983.6    0.12       0
  5096.3    0.07       0  5195.0    0.12       0
Bank Sta=4979.6,4983.6
Exp/Cntr=0.3,0.1

Type RM Length L Ch R = 1,1040,148,148,148
BEGIN DESCRIPTION:
Stream0823 2.0
END DESCRIPTION:
XS GIS Cut Line= 3
      2465724.99     13591475.02      2465875.00     13591175.00
      2465774.99     13590874.97
#Sta/Elev= 30
  4659.2  281.64  4690.0  279.22  4714.2  278.18  4822.8  271.70  4868.9  268.65
  4913.6  266.88  4941.5  264.81  4980.7  263.96  4991.8  261.03  5003.2  260.78
  5003.4  260.28  5006.9  260.28  5007.2  260.78  5015.7  261.89  5036.8  263.17
  5050.7  265.98  5068.4  269.04  5100.0  269.33  5110.6  268.35  5152.7  272.76
  5194.9  274.91  5205.5  275.98  5216.0  275.75  5226.5  276.94  5237.1  277.33
  5258.2  277.18  5289.8  279.67  5300.3  281.05  5309.5  280.32  5310.9  280.32
#Mann=7,-1,0
  4659.2    0.12       0  4714.2    0.07       0  4822.8    0.05       0
  5003.2    0.05       0  5007.2    0.05       0  5050.7    0.07       0
  5309.5    0.12       0
Bank Sta=5003.2,5007.2
Exp/Cntr=0.3,0.1

Type RM Length L Ch R = 1,892,88,88,88
BEGIN DESCRIPTION:
H21108
END DESCRIPTION:
XS GIS Cut Line= 3
      2465936.16     13591481.40      2466026.08     13591152.50
      2465959.88     13590870.53
#Sta/Elev= 30
  4682.4  277.22  4728.7  274.23  4775.0  271.92  4792.7  270.50  4809.5  267.11
  4814.7  266.97  4844.0  262.97  4873.6  260.17  4873.9  259.67  4877.4  259.67
  4877.6  260.17  4888.9  261.69  4917.1  262.29  4937.8  263.96  4957.9  264.88
  4963.1  264.65  4979.3  266.03  5031.1  265.85  5054.2  266.29  5082.4  266.71
  5137.5  268.63  5205.7  272.58  5228.2  272.72  5236.5  273.32  5265.5  277.19
  5270.6  277.47  5277.6  276.67  5298.1  276.88  5307.9  277.65  5313.0  278.73
#Mann=5,-1,0
  4682.4    0.12       0  4728.7    0.05       0  4873.6    0.05       0
  4877.6    0.05       0  5054.2    0.07       0
Bank Sta=4873.6,4877.6
Exp/Cntr=0.3,0.1

Type RM Length L Ch R = 1,804,267,267,267
BEGIN DESCRIPTION:
H21107
END DESCRIPTION:
XS GIS Cut Line= 3
      2466098.77     13591482.65      2466111.09     13591099.53
      2466013.78     13590853.17
#Sta/Elev= 30
  4692.2  274.98  4709.9  273.18  4749.9  271.90  4799.9  269.18  4809.9  267.78
  4819.9  265.38  4829.9  264.68  4900.0  261.43  4910.0  257.48  4918.0  256.07
  4918.2  255.57  4921.7  255.57  4922.0  256.07  4930.0  258.39  4960.0  260.30
  5000.0  264.14  5050.0  263.72  5101.1  264.67  5144.9  266.64  5166.4  268.29
  5177.2  268.13  5214.7  270.34  5220.2  271.45  5239.0  273.74  5252.4  272.87
  5263.2  273.03  5274.2  273.95  5298.5  277.42  5319.0  276.71  5340.4  277.30
#Mann=4,-1,0
  4692.2    0.05       0  4918.0    0.05       0  4922.0    0.05       0
  5319.0    0.07       0
Bank Sta=4918,4922
Exp/Cntr=0.3,0.1

Type RM Length L Ch R = 1,537,136,136,136
BEGIN DESCRIPTION:
Stream0823 1.0
END DESCRIPTION:
XS GIS Cut Line= 3
      2466225.00     13591475.00      2466375.00     13591175.00
      2466125.02     13590875.02
#Sta/Elev= 30
  4664.6  273.19  4688.0  272.51  4731.7  269.81  4776.4  269.09  4829.5  265.51
  4888.2  263.49  4902.2  262.28  4919.0  258.25  4921.1  258.68  4924.5  259.38
  4941.3  254.63  4955.3  252.83  4975.7  252.01  4975.9  251.51  4979.7  252.01
  4991.6  252.61  4997.2  255.63  5003.3  255.63  5007.2  256.99  5023.2  258.81
  5028.0  258.63  5035.8  260.83  5050.1  261.52  5128.2  259.87  5248.0  263.74
  5319.6  268.16  5326.1  269.57  5348.2  269.91  5376.9  273.76  5390.5  273.09
#Mann=6,-1,0
  4664.6    0.05       0  4688.0   0.035       0  4921.1    0.07       0
  4975.7    0.05       0  4979.7    0.07       0  5023.2    0.05       0
Bank Sta=4975.7,4979.7
Exp/Cntr=0.3,0.1

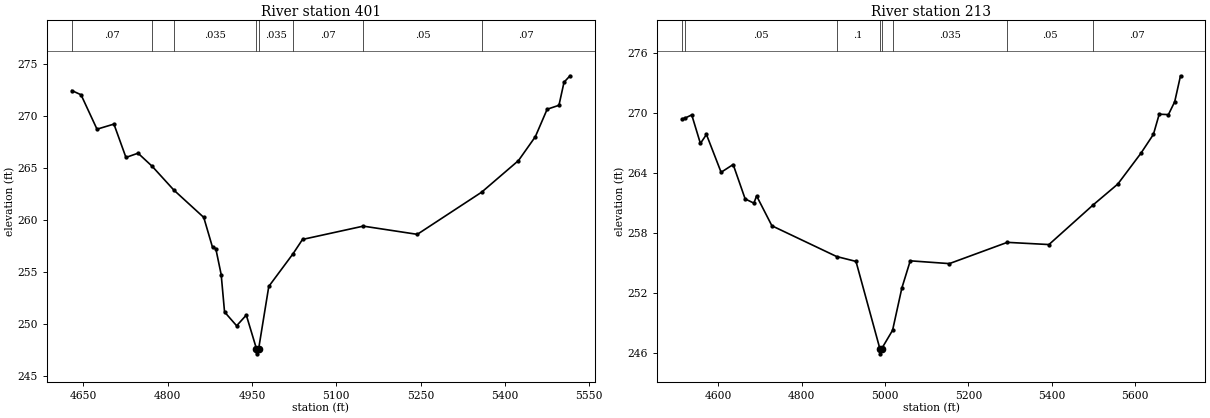
Type RM Length L Ch R = 1,401,188,188,188
BEGIN DESCRIPTION:
H21106
END DESCRIPTION:
XS GIS Cut Line= 4
      2466361.18     13591503.58      2466513.93     13591246.13
      2466509.00     13591083.51      2466156.68     13590846.99
#Sta/Elev= 30
  4629.5  272.49  4646.0  272.08  4674.4  268.77  4704.5  269.26  4725.9  266.05
  4747.4  266.46  4772.7  265.19  4811.1  262.91  4864.3  260.28  4879.9  257.40
  4885.7  257.28  4895.3  254.78  4901.3  251.18  4922.8  249.85  4940.0  250.88
  4958.0  247.65  4958.2  247.15  4962.0  247.65  4980.0  253.64  5023.1  256.78
  5040.0  258.16  5148.1  259.44  5244.2  258.65  5358.7  262.71  5424.2  265.75
  5454.2  268.05  5475.2  270.69  5496.2  271.07  5505.2  273.29  5515.9  273.91
#Mann=8,-1,0
  4629.5    0.07       0  4772.7    0.05       0  4811.1   0.035       0
  4958.0   0.035       0  4962.0   0.035       0  5023.1    0.07       0
  5148.1    0.05       0  5358.7    0.07       0
Bank Sta=4958,4962
Exp/Cntr=0.3,0.1

Type RM Length L Ch R = 1,213,0,0,0
BEGIN DESCRIPTION:
XS7784
END DESCRIPTION:
XS GIS Cut Line= 4
      2466425.02     13591526.45      2466704.99     13591305.08
      2466694.14     13591035.98      2466178.79     13590793.46
#Sta/Elev= 30
  4513.2  269.44  4519.8  269.51  4536.0  269.83  4556.8  266.97  4571.3  267.87
  4606.5  264.08  4635.4  264.86  4664.2  261.41  4685.1  260.99  4691.7  261.71
  4728.4  258.72  4883.7  255.64  4930.2  255.15  4987.6  246.39  4987.9  245.89
  4991.6  246.39  5018.0  248.25  5040.3  252.49  5060.4  255.21  5154.3  254.93
  5293.3  257.06  5393.3  256.84  5499.3  260.81  5558.5  262.90  5613.7  265.97
  5644.0  267.88  5657.9  269.90  5680.0  269.86  5695.1  271.15  5709.0  273.75
#Mann=8,-1,0
  4513.2    0.07       0  4519.8    0.05       0  4883.7     0.1       0
  4987.6    0.05       0  4991.6     0.1       0  5018.0   0.035       0
  5293.3    0.05       0  5499.3    0.07       0
Bank Sta=4987.6,4991.6
Exp/Cntr=0.3,0.1

Chan Stop Cuts=-1