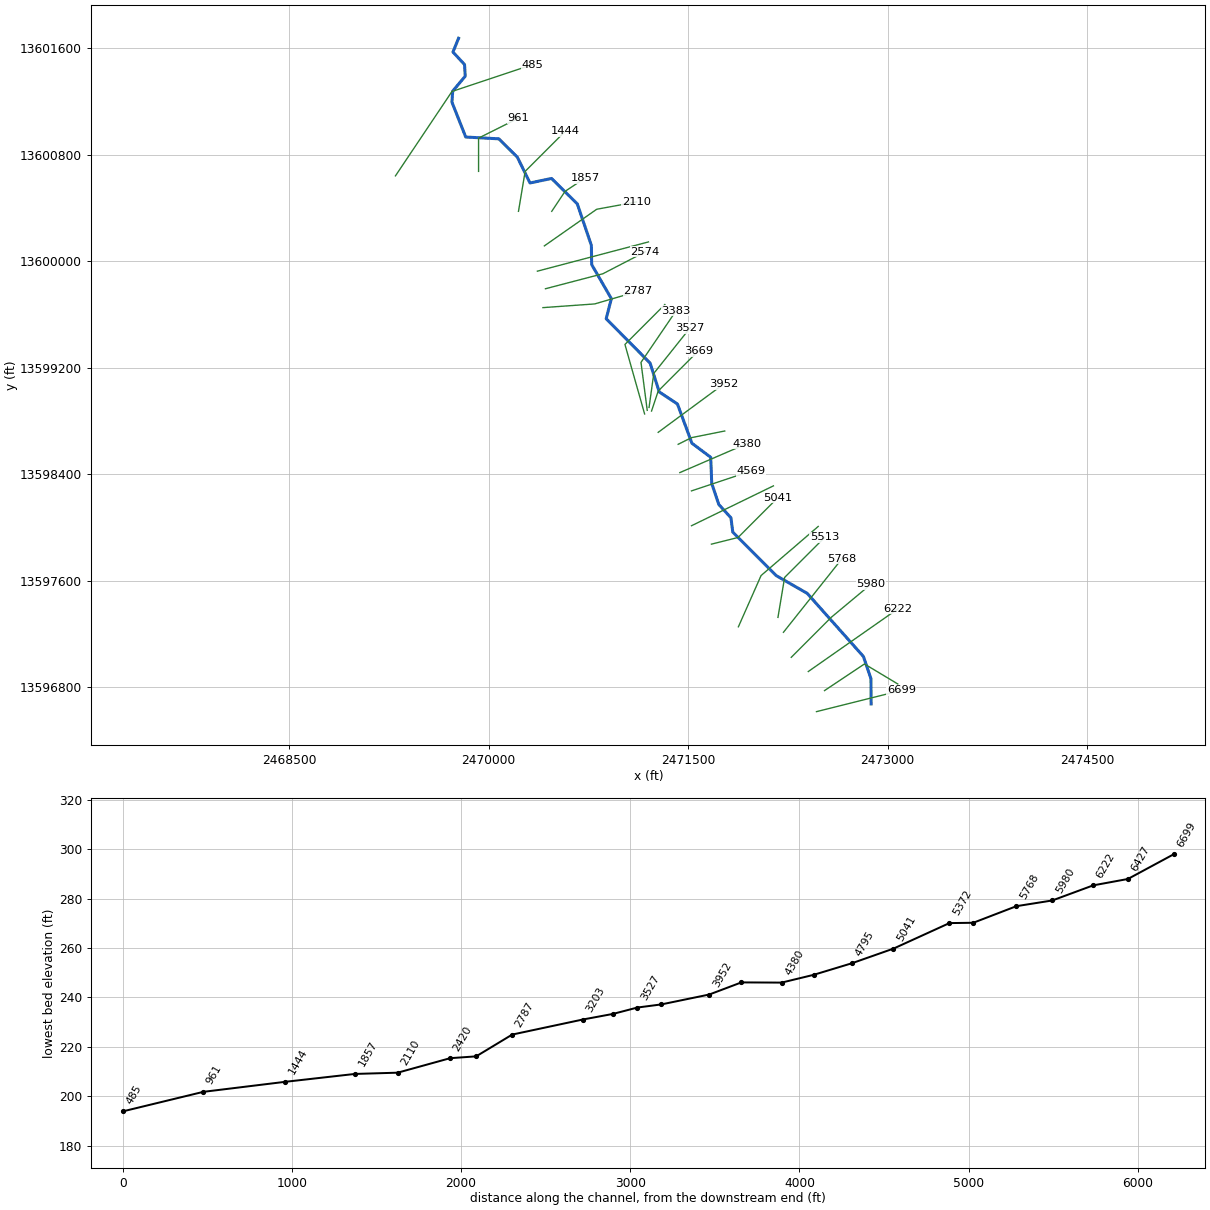
--- Stream0824.prj (project) ---

Proj Title=Stream0824 Base Level Engineering
Current Plan=p01
Default Exp/Contr=0.3,0.1
English Units
Geom File=g01
Flow File=f01
Plan File=p01
BEGIN DESCRIPTION:
Stream0824
END DESCRIPTION:

--- Stream0824.p01 (plan) ---

Plan Title=Multiple Run
Short Identifier=Multiple
Geom File=g01
Flow File=f01
Subcritical Flow
K Sum by GR= 0
Std Step Tol= 0.01
Critical Tol= 0.01
Num of Std Step Trials= 20
Max Error Tol= 0.3
Flow Tol Ratio= 0.001
Split Flow NTrial= 30
Split Flow Tol= 0.02
Split Flow Ratio= 0.02
Log Output Level= 0
Friction Slope Method= 1
Unsteady Friction Slope Method= 2
Unsteady Bridges Friction Slope Method= 1
Parabolic Critical Depth
Global Vel Dist=  1 , 1 , 1
Global Log Level= 0
CheckData=True
Encroach Param= -1, 0, 0, 0
BEGIN DESCRIPTION:
Multiple Run
END DESCRIPTION:

--- Stream0824.f01 (steady flow) ---

Flow Title=Multiple
Number of Profiles=7
Profile Names=10-year,25-year,50-year,1pct_min,100-year,1pct_plu,500-year
River Rch & RM= Stream0824,Reach-1,6699
     310     483     635     406     811    1618    1305
River Rch & RM= Stream0824,Reach-1,2420
     618    1009    1367     900    1796    3583    3063
Boundary for River Rch & Prof#=Stream0824,Reach-1,1
Up Type=0
Dn Type=3
Dn Slope=0.005
Boundary for River Rch & Prof#=Stream0824,Reach-1,2
Up Type=0
Dn Type=3
Dn Slope=0.005
Boundary for River Rch & Prof#=Stream0824,Reach-1,3
Up Type=0
Dn Type=3
Dn Slope=0.005
Boundary for River Rch & Prof#=Stream0824,Reach-1,4
Up Type=0
Dn Type=3
Dn Slope=0.005
Boundary for River Rch & Prof#=Stream0824,Reach-1,5
Up Type=0
Dn Type=3
Dn Slope=0.005
Boundary for River Rch & Prof#=Stream0824,Reach-1,6
Up Type=0
Dn Type=3
Dn Slope=0.005
Boundary for River Rch & Prof#=Stream0824,Reach-1,7
Up Type=0
Dn Type=3
Dn Slope=0.005

--- Stream0824.g01 (geometry) ---

Geom Title=Existing Conditions

River Reach=Stream0824,Reach-1
Reach XY= 30
      2472875.00     13596675.00      2472873.79     13596864.50
      2472817.14     13597031.17      2472395.09     13597505.21
      2472161.79     13597638.63      2471835.52     13597965.21
      2471821.37     13598073.50      2471730.54     13598172.58
      2471677.26     13598330.94      2471669.54     13598527.47
      2471528.17     13598633.34      2471419.58     13598927.67
      2471282.75     13599018.55      2471214.24     13599234.68
      2470884.15     13599568.27      2470922.85     13599719.03
      2470775.00     13599975.00      2470772.78     13600119.08
      2470666.86     13600431.06      2470473.37     13600621.87
      2470311.43     13600587.98      2470216.86     13600781.06
      2470077.45     13600919.54      2469828.35     13600933.09
      2469724.90     13601195.10      2469730.41     13601277.42
      2469824.76     13601390.22      2469819.58     13601477.43
      2469732.60     13601571.62      2469775.00     13601675.00

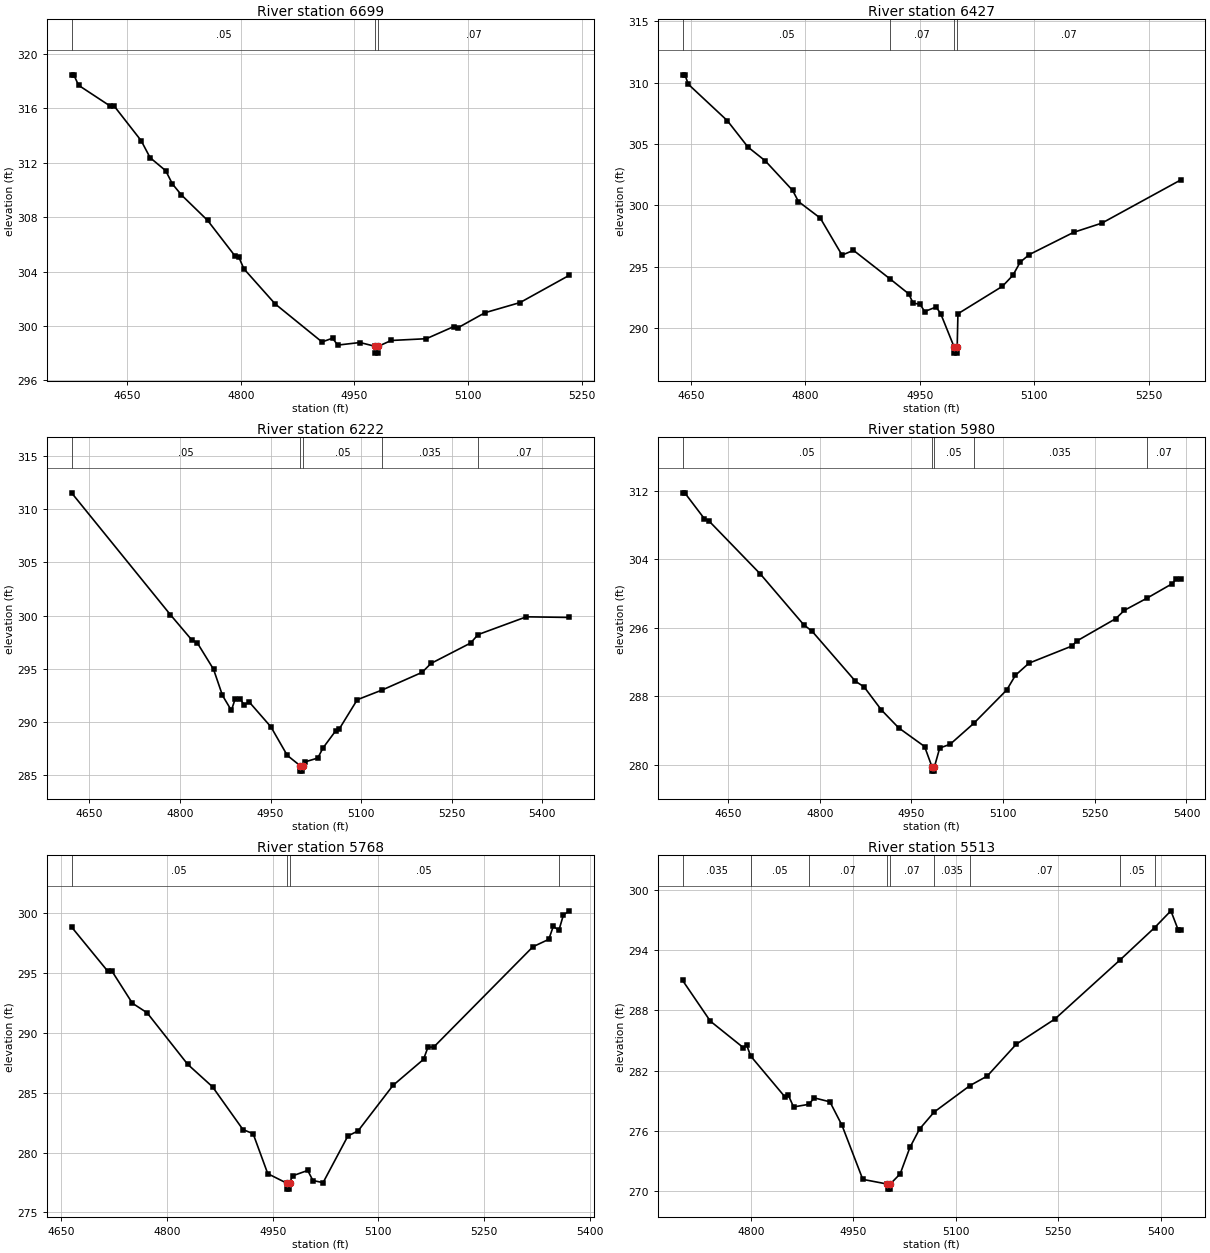
Type RM Length L Ch R = 1,6699,272,272,272
BEGIN DESCRIPTION:
XS7787
END DESCRIPTION:
XS GIS Cut Line= 2
      2472464.47     13596616.87      2473101.66     13596776.17
#Sta/Elev= 30
  4576.8  318.47  4579.7  318.47  4586.1  317.70  4627.3  316.19  4632.5  316.21
  4668.6  313.63  4680.4  312.38  4701.0  311.42  4709.8  310.45  4721.7  309.64
  4756.2  307.77  4792.3  305.16  4797.4  305.07  4804.1  304.21  4845.3  301.63
  4907.2  298.83  4921.1  299.11  4927.8  298.60  4957.2  298.79  4977.3  298.51
  4977.6  298.01  4981.1  298.01  4981.3  298.51  4998.4  298.94  5044.8  299.07
  5080.9  299.96  5086.0  299.86  5122.1  300.98  5168.5  301.73  5233.6  303.74
#Mann=3,-1,0
  4576.8    0.05       0  4977.3    0.05       0  4981.3    0.07       0
Bank Sta=4977.3,4981.3
Exp/Cntr=0.3,0.1

Type RM Length L Ch R = 1,6427,205,205,205
BEGIN DESCRIPTION:
Stream0824 14.0
END DESCRIPTION:
XS GIS Cut Line= 3
      2472525.00     13596775.00      2472825.00     13596975.00
      2473075.00     13596825.00
#Sta/Elev= 30
  4639.4  310.65  4642.4  310.65  4646.9  309.88  4698.0  306.91  4725.0  304.76
  4747.6  303.64  4783.6  301.22  4791.1  300.32  4819.7  298.97  4848.2  295.95
  4863.2  296.34  4911.5  293.99  4935.4  292.80  4941.4  292.03  4950.4  291.95
  4956.4  291.35  4971.4  291.72  4977.4  291.18  4995.0  288.46  4995.2  287.96
  4998.7  287.96  4999.0  288.46  5000.0  291.17  5058.3  293.41  5071.9  294.30
  5081.6  295.38  5093.3  295.99  5151.6  297.81  5188.5  298.56  5291.5  302.07
#Mann=4,-1,0
  4639.4    0.05       0  4911.5    0.07       0  4995.0    0.05       0
  4999.0    0.07       0
Bank Sta=4995,4999
Exp/Cntr=0.3,0.1

Type RM Length L Ch R = 1,6222,242,242,242
BEGIN DESCRIPTION:
H21117
END DESCRIPTION:
XS GIS Cut Line= 2
      2472403.04     13596918.32      2473078.75     13597390.77
#Sta/Elev= 30
  4620.4  311.53  4784.0  300.08  4819.7  297.69  4828.4  297.45  4855.5  294.95
  4870.3  292.49  4885.1  291.08  4891.2  292.16  4899.9  292.13  4906.0  291.62
  4914.8  291.86  4950.5  289.54  4977.6  286.86  4999.1  285.88  4999.3  285.38
  5002.8  285.38  5003.1  285.88  5007.2  286.25  5028.1  286.61  5036.9  287.57
  5057.8  289.17  5063.9  289.36  5093.5  292.09  5135.0  293.01  5200.8  294.66
  5215.6  295.50  5281.0  297.41  5293.6  298.21  5373.5  299.88  5444.9  299.82
#Mann=5,-1,0
  4620.4    0.05       0  4999.1    0.05       0  5003.1    0.05       0
  5135.0   0.035       0  5293.6    0.07       0
Bank Sta=4999.1,5003.1
Exp/Cntr=0.3,0.1

Type RM Length L Ch R = 1,5980,212,212,212
BEGIN DESCRIPTION:
Stream0824 13.0
END DESCRIPTION:
XS GIS Cut Line= 3
      2472275.00     13597025.00      2472575.00     13597325.00
      2472875.01     13597575.01
#Sta/Elev= 30
  4575.5  311.74  4579.0  311.74  4610.9  308.74  4617.9  308.51  4702.8  302.26
  4773.5  296.36  4787.6  295.57  4858.3  289.75  4872.5  289.09  4900.8  286.40
  4929.1  284.31  4971.5  282.13  4983.6  279.76  4983.9  279.26  4987.4  279.26
  4987.6  279.76  4996.2  281.95  5013.4  282.40  5052.0  284.84  5105.9  288.73
  5120.2  290.45  5142.3  291.86  5212.6  293.86  5220.4  294.44  5284.2  297.05
  5298.5  298.03  5335.5  299.45  5376.6  301.13  5383.1  301.67  5390.3  301.67
#Mann=5,-1,0
  4575.5    0.05       0  4983.6    0.05       0  4987.6    0.05       0
  5052.0   0.035       0  5335.5    0.07       0
Bank Sta=4983.6,4987.6
Exp/Cntr=0.3,0.1

Type RM Length L Ch R = 1,5768,255,255,255
BEGIN DESCRIPTION:
H21116
END DESCRIPTION:
XS GIS Cut Line= 2
      2472215.98     13597212.75      2472656.17     13597765.74
#Sta/Elev= 30
  4664.4  298.83  4715.5  295.16  4721.9  295.13  4750.7  292.47  4771.6  291.67
  4829.2  287.37  4864.5  285.49  4907.7  281.92  4922.1  281.58  4942.9  278.24
  4969.8  277.45  4970.0  276.95  4973.5  276.95  4973.8  277.45  4978.2  278.06
  4999.6  278.51  5007.0  277.67  5021.4  277.49  5056.7  281.39  5071.1  281.81
  5120.7  285.61  5164.0  287.78  5170.4  288.81  5178.4  288.80  5319.3  297.18
  5341.8  297.80  5348.2  298.88  5356.2  298.56  5362.6  299.84  5371.2  300.18
#Mann=4,-1,0
  4664.4    0.05       0  4969.8    0.05       0  4973.8    0.05       0
  5356.2    0.07       0
Bank Sta=4969.8,4973.8
Exp/Cntr=0.3,0.1

Type RM Length L Ch R = 1,5513,141,141,141
BEGIN DESCRIPTION:
Stream0824 12.0
END DESCRIPTION:
XS GIS Cut Line= 3
      2472174.99     13597324.95      2472225.00     13597625.00
      2472524.97     13597924.97
#Sta/Elev= 30
  4700.3  290.98  4740.9  286.93  4789.1  284.30  4794.1  284.54  4799.8  283.47
  4849.9  279.41  4855.0  279.57  4862.6  278.40  4884.8  278.66  4893.0  279.30
  4915.8  278.91  4933.5  276.57  4963.9  271.20  5000.0  270.73  5000.2  270.23
  5003.7  270.23  5004.0  270.73  5018.6  271.75  5032.8  274.37  5046.9  276.20
  5068.2  277.89  5120.8  280.53  5145.9  281.47  5188.3  284.63  5244.9  287.14
  5339.8  292.99  5391.0  296.24  5414.6  297.90  5425.2  296.02  5428.7  296.02
#Mann=9,-1,0
  4700.3   0.035       0  4799.8    0.05       0  4884.8    0.07       0
  5000.0    0.05       0  5004.0    0.07       0  5068.2   0.035       0
  5120.8    0.07       0  5339.8    0.05       0  5391.0   0.035       0
Bank Sta=5000,5004
Exp/Cntr=0.3,0.1

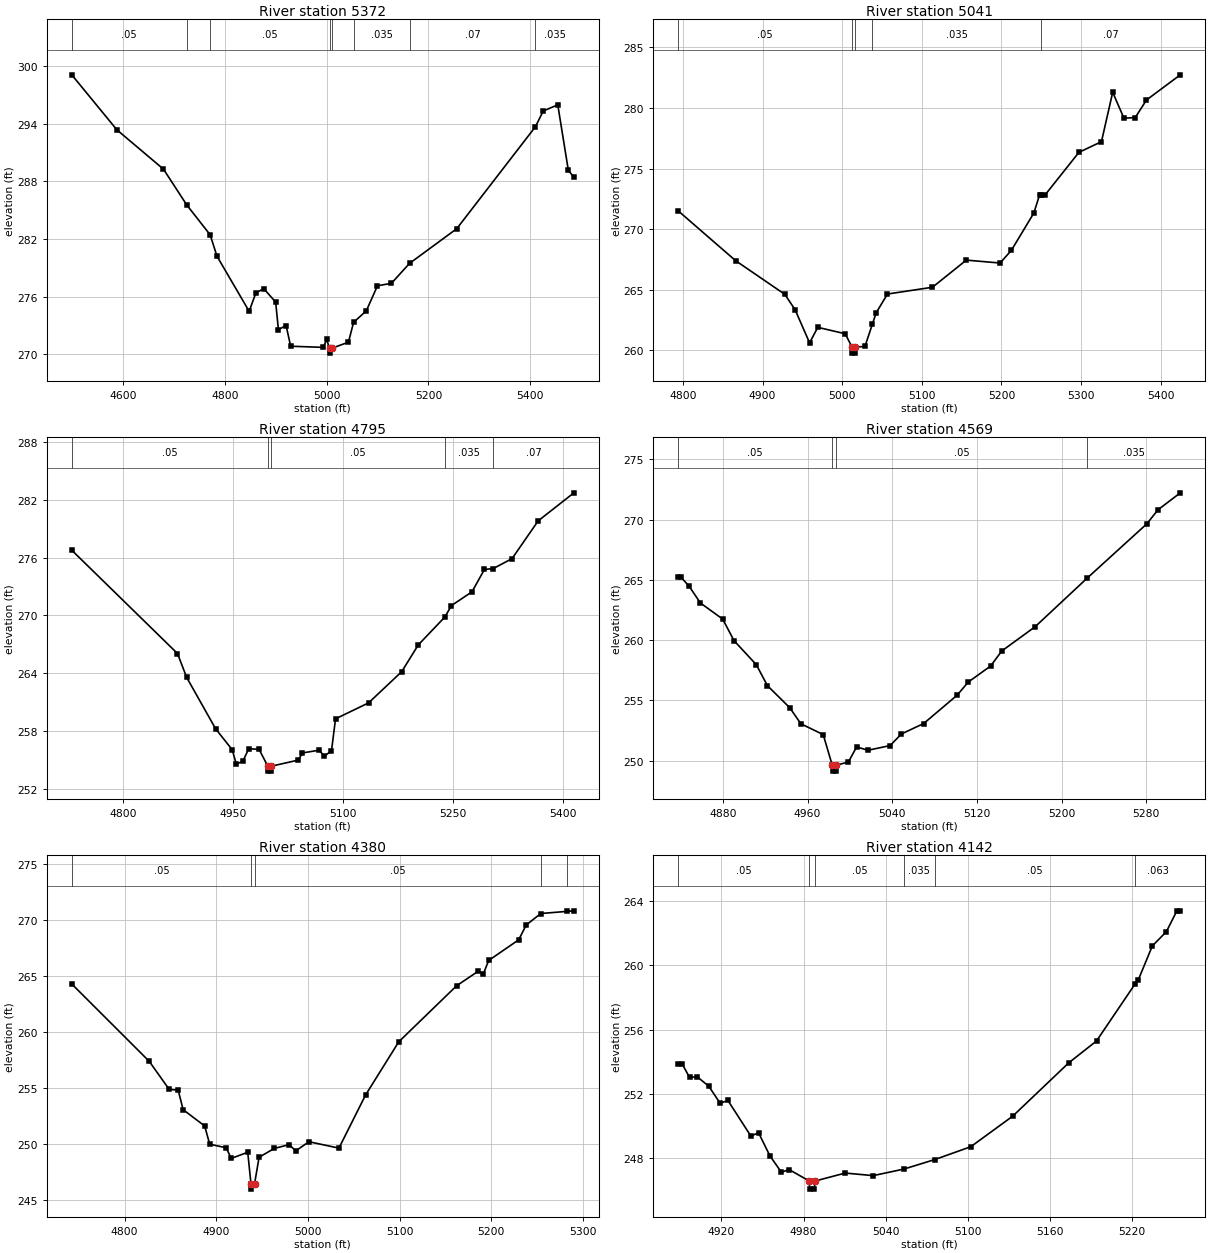
Type RM Length L Ch R = 1,5372,331,331,331
BEGIN DESCRIPTION:
H21115
END DESCRIPTION:
XS GIS Cut Line= 3
      2471877.54     13597253.97      2472048.13     13597639.16
      2472477.35     13598007.85
#Sta/Elev= 30
  4498.9  299.12  4587.5  293.39  4679.2  289.28  4725.1  285.54  4770.9  282.44
  4784.4  280.20  4847.6  274.46  4860.9  276.39  4876.4  276.82  4899.7  275.42
  4905.1  272.55  4920.2  272.98  4929.2  270.82  4993.4  270.70  5000.0  271.53
  5005.6  270.60  5005.9  270.10  5009.6  270.60  5042.8  271.24  5052.9  273.31
  5077.9  274.51  5099.8  277.12  5127.3  277.38  5162.9  279.46  5255.6  283.07
  5410.4  293.71  5425.7  295.35  5454.3  295.99  5475.1  289.15  5486.0  288.44
#Mann=8,-1,0
  4498.9    0.05       0  4725.1   0.035       0  4770.9    0.05       0
  5005.6    0.05       0  5009.6    0.05       0  5052.9   0.035       0
  5162.9    0.07       0  5410.4   0.035       0
Bank Sta=5005.6,5009.6
Exp/Cntr=0.3,0.1

Type RM Length L Ch R = 1,5041,246,246,246
BEGIN DESCRIPTION:
Stream0824 11.0
END DESCRIPTION:
XS GIS Cut Line= 3
      2471674.96     13597874.99      2471875.00     13597925.00
      2472175.03     13598225.03
#Sta/Elev= 30
  4794.1  271.51  4866.3  267.39  4928.1  264.61  4941.0  263.33  4959.1  260.61
  4969.4  261.89  5003.8  261.36  5012.4  260.26  5012.7  259.76  5016.2  259.76
  5016.4  260.26  5028.6  260.31  5037.9  262.14  5042.7  263.09  5056.9  264.64
  5113.4  265.20  5155.9  267.44  5198.3  267.20  5212.4  268.24  5240.7  271.33
  5247.8  272.81  5250.0  272.82  5254.9  272.83  5297.3  276.34  5325.6  277.22
  5339.7  281.30  5353.8  279.16  5368.0  279.21  5382.1  280.66  5424.6  282.74
#Mann=5,-1,0
  4794.1    0.05       0  5012.4    0.05       0  5016.4    0.05       0
  5037.9   0.035       0  5250.0    0.07       0
Bank Sta=5012.4,5016.4
Exp/Cntr=0.3,0.1

Type RM Length L Ch R = 1,4795,226,226,226
BEGIN DESCRIPTION:
H21118
END DESCRIPTION:
XS GIS Cut Line= 2
      2471525.39     13598013.34      2472140.80     13598312.80
#Sta/Elev= 30
  4729.9  276.77  4874.0  266.04  4886.5  263.56  4926.0  258.22  4948.6  256.05
  4954.1  254.57  4963.0  254.84  4971.1  256.16  4985.2  256.09  4997.2  254.33
  4997.5  253.83  5001.0  253.83  5001.2  254.33  5038.8  254.98  5044.3  255.72
  5066.9  256.00  5074.2  255.39  5083.9  255.94  5089.4  259.26  5134.5  260.92
  5179.6  264.16  5202.2  266.94  5238.6  269.85  5247.3  271.02  5275.4  272.45
  5292.3  274.77  5304.5  274.87  5330.0  275.90  5365.6  279.82  5414.3  282.73
#Mann=5,-1,0
  4729.9    0.05       0  4997.2    0.05       0  5001.2    0.05       0
  5238.6   0.035       0  5304.5    0.07       0
Bank Sta=4997.2,5001.2
Exp/Cntr=0.3,0.1

Type RM Length L Ch R = 1,4569,189,189,189
BEGIN DESCRIPTION:
Stream0824 10.0
END DESCRIPTION:
XS GIS Cut Line= 3
      2471525.03     13598275.01      2471675.00     13598325.00
      2471974.99     13598425.00
#Sta/Elev= 30
  4837.8  265.24  4840.4  265.24  4848.3  264.46  4858.8  263.09  4879.9  261.75
  4890.5  259.97  4911.6  257.97  4922.1  256.23  4943.2  254.40  4953.7  253.07
  4974.8  252.17  4983.3  249.64  4983.6  249.14  4987.1  249.14  4987.3  249.64
  4998.5  249.89  5006.4  251.15  5017.0  250.87  5038.0  251.26  5048.6  252.22
  5069.7  253.09  5101.3  255.44  5111.8  256.53  5132.9  257.86  5143.5  259.11
  5175.1  261.13  5224.2  265.16  5280.5  269.66  5291.0  270.82  5312.1  272.23
#Mann=4,-1,0
  4837.8    0.05       0  4983.3    0.05       0  4987.3    0.05       0
  5224.2   0.035       0
Bank Sta=4983.3,4987.3
Exp/Cntr=0.3,0.1

Type RM Length L Ch R = 1,4380,238,238,238
BEGIN DESCRIPTION:
H21114
END DESCRIPTION:
XS GIS Cut Line= 2
      2471437.38     13598412.29      2471940.41     13598629.44
#Sta/Elev= 30
  4742.3  264.31  4826.8  257.41  4848.6  254.90  4858.4  254.84  4863.8  253.09
  4887.3  251.64  4892.8  250.01  4910.8  249.69  4916.3  248.74  4934.3  249.29
  4937.8  246.50  4938.0  246.00  4941.8  246.50  4946.7  248.85  4963.3  249.63
  4979.3  249.97  4986.8  249.42  5001.1  250.23  5033.8  249.66  5062.8  254.39
  5099.1  259.15  5162.2  264.15  5185.8  265.45  5191.2  265.17  5197.2  266.41
  5229.9  268.25  5238.2  269.58  5254.1  270.60  5282.6  270.79  5290.2  270.84
#Mann=5,-1,0
  4742.3    0.05       0  4937.8    0.05       0  4941.8    0.05       0
  5254.1   0.063       0  5282.6   0.035       0
Bank Sta=4937.8,4941.8
Exp/Cntr=0.3,0.1

Type RM Length L Ch R = 1,4142,190,190,190
BEGIN DESCRIPTION:
Stream0824 9.0
END DESCRIPTION:
XS GIS Cut Line= 3
      2471425.04     13598625.02      2471525.00     13598675.00
      2471774.99     13598725.00
#Sta/Elev= 30
  4888.4  253.89  4891.2  253.89  4896.7  253.03  4902.3  253.07  4910.7  252.49
  4919.1  251.42  4924.7  251.60  4941.5  249.38  4947.1  249.59  4955.4  248.15
  4963.8  247.13  4969.4  247.30  4984.2  246.58  4984.4  246.08  4987.9  246.08
  4988.2  246.58  5010.4  247.08  5030.8  246.92  5053.3  247.33  5075.8  247.92
  5102.1  248.72  5132.7  250.62  5173.5  253.93  5193.9  255.30  5222.0  258.84
  5224.5  259.12  5234.7  261.22  5244.9  262.10  5252.6  263.40  5255.1  263.40
#Mann=6,-1,0
  4888.4    0.05       0  4984.2    0.05       0  4988.2    0.05       0
  5053.3   0.035       0  5075.8    0.05       0  5222.0   0.063       0
Bank Sta=4984.2,4988.2
Exp/Cntr=0.3,0.1

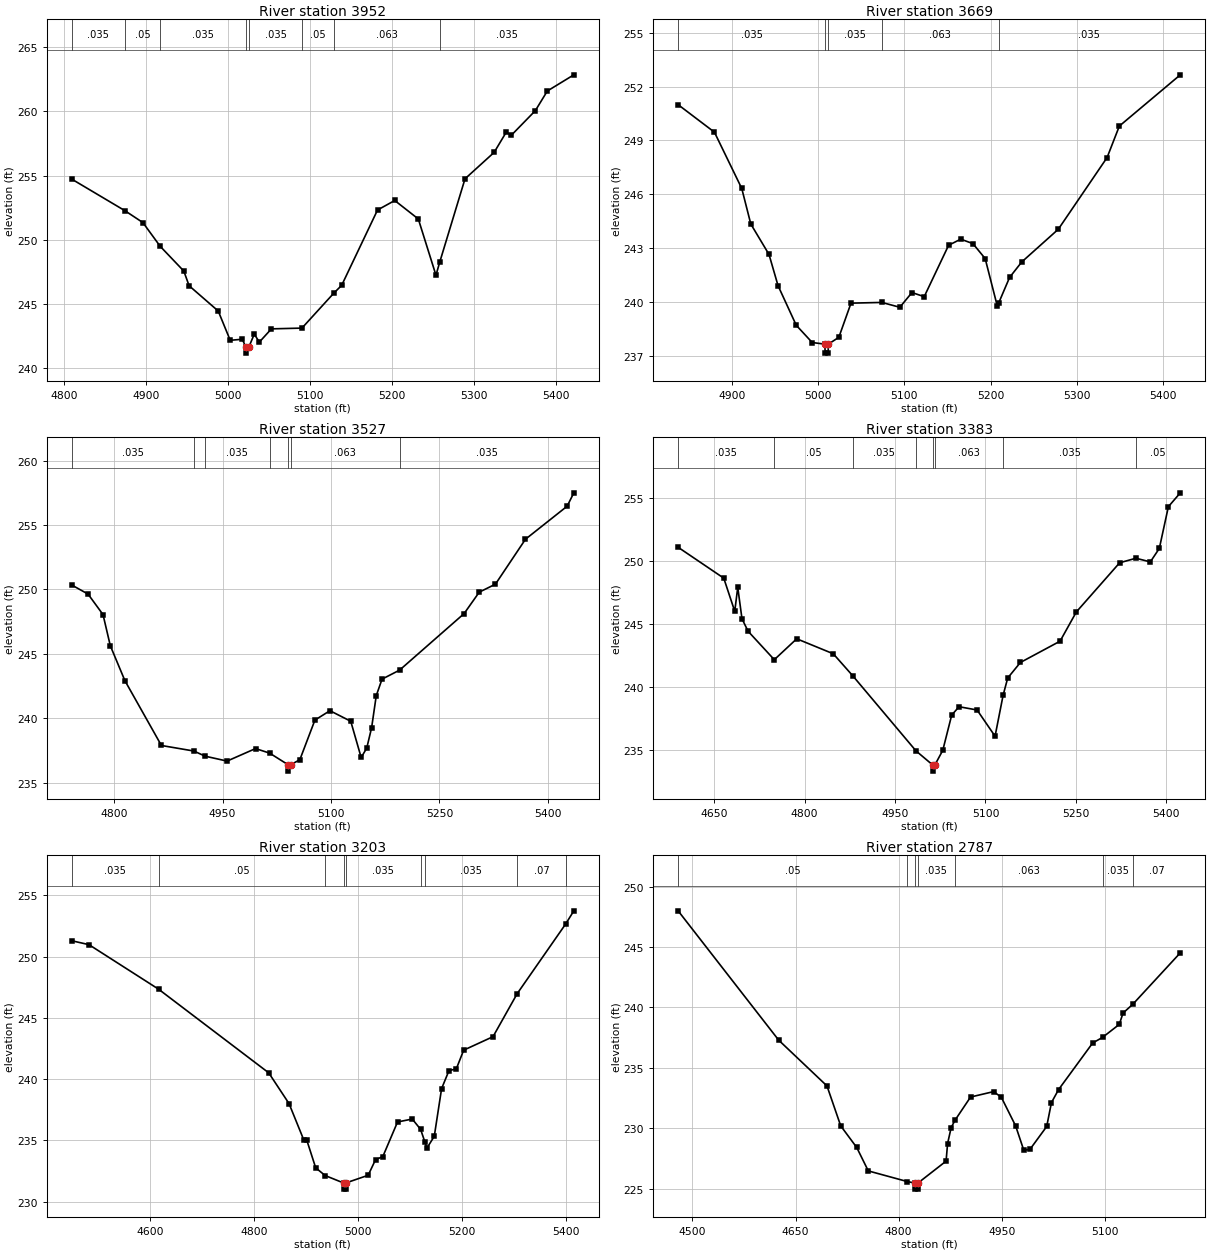
Type RM Length L Ch R = 1,3952,283,283,283
BEGIN DESCRIPTION:
H21113
END DESCRIPTION:
XS GIS Cut Line= 2
      2471275.02     13598714.92      2471767.49     13599078.08
#Sta/Elev= 30
  4809.7  254.73  4874.5  252.27  4896.5  251.34  4917.6  249.49  4946.4  247.56
  4952.8  246.42  4988.3  244.45  5002.9  242.17  5017.6  242.25  5021.8  241.67
  5022.0  241.17  5025.8  241.67  5032.2  242.65  5038.4  242.03  5053.1  243.06
  5090.3  243.12  5129.1  245.84  5138.7  246.45  5182.4  252.32  5203.4  253.06
  5232.1  251.62  5253.6  247.24  5258.2  248.26  5289.0  254.75  5324.5  256.81
  5339.2  258.38  5345.4  258.14  5374.7  260.06  5389.3  261.59  5421.6  262.85
#Mann=8,-1,0
  4809.7   0.035       0  4874.5    0.05       0  4917.6   0.035       0
  5021.8   0.035       0  5025.8   0.035       0  5090.3    0.05       0
  5129.1   0.063       0  5258.2   0.035       0
Bank Sta=5021.8,5025.8
Exp/Cntr=0.3,0.1

Type RM Length L Ch R = 1,3669,142,142,142
BEGIN DESCRIPTION:
Stream0824 8.0
END DESCRIPTION:
XS GIS Cut Line= 3
      2471225.01     13598875.02      2471275.00     13599025.00
      2471575.03     13599325.03
#Sta/Elev= 30
  4837.7  250.99  4879.8  249.46  4911.5  246.33  4922.0  244.35  4943.1  242.66
  4953.6  240.92  4974.7  238.72  4993.2  237.76  5007.9  237.67  5008.2  237.17
  5011.7  237.17  5011.9  237.67  5024.1  238.05  5038.2  239.95  5074.0  239.99
  5094.8  239.72  5108.9  240.54  5123.1  240.31  5151.4  243.17  5165.5  243.51
  5179.6  243.26  5193.8  242.43  5207.9  239.78  5209.3  239.94  5222.1  241.38
  5236.2  242.24  5278.6  244.06  5335.2  248.05  5349.4  249.80  5420.1  252.65
#Mann=5,-1,0
  4837.7   0.035       0  5007.9   0.035       0  5011.9   0.035       0
  5074.0   0.063       0  5209.3   0.035       0
Bank Sta=5007.9,5011.9
Exp/Cntr=0.3,0.1

Type RM Length L Ch R = 1,3527,144,144,144
BEGIN DESCRIPTION:
H21112
END DESCRIPTION:
XS GIS Cut Line= 3
      2471206.23     13598901.98      2471242.00     13599157.87
      2471514.36     13599499.01
#Sta/Elev= 30
  4741.1  250.35  4763.8  249.64  4784.5  248.05  4794.6  245.63  4814.8  242.92
  4865.3  237.89  4910.2  237.46  4925.8  237.06  4956.2  236.68  4995.5  237.65
  5015.0  237.30  5040.5  236.40  5040.7  235.90  5044.5  236.40  5056.9  236.79
  5077.7  239.86  5098.5  240.59  5127.3  239.77  5141.7  236.96  5149.4  237.68
  5156.2  239.28  5162.6  241.76  5170.6  243.04  5194.9  243.74  5284.2  248.13
  5305.1  249.79  5327.5  250.41  5369.1  253.90  5426.7  256.46  5436.0  257.50
#Mann=7,-1,0
  4741.1   0.035       0  4910.2    0.05       0  4925.8   0.035       0
  5015.0   0.063       0  5040.5   0.035       0  5044.5   0.063       0
  5194.9   0.035       0
Bank Sta=5040.5,5044.5
Exp/Cntr=0.3,0.1

Type RM Length L Ch R = 1,3383,180,180,180
BEGIN DESCRIPTION:
H21111
END DESCRIPTION:
XS GIS Cut Line= 3
      2471192.48     13598879.95      2471145.71     13599240.41
      2471409.84     13599628.35
#Sta/Elev= 30
  4590.3  251.08  4666.0  248.63  4684.2  246.00  4689.2  247.90  4696.2  245.41
  4706.3  244.42  4749.8  242.16  4787.0  243.82  4847.6  242.63  4880.0  240.88
  4984.7  234.93  5012.2  233.82  5012.5  233.32  5016.2  233.82  5029.2  234.97
  5044.0  237.77  5056.2  238.43  5086.1  238.17  5115.9  236.09  5129.3  239.35
  5136.9  240.71  5157.9  241.94  5223.7  243.63  5250.7  245.95  5322.5  249.85
  5349.4  250.21  5373.4  249.92  5388.3  250.99  5403.3  254.30  5423.1  255.40
#Mann=8,-1,0
  4590.3   0.035       0  4749.8    0.05       0  4880.0   0.035       0
  4984.7   0.063       0  5012.2    0.05       0  5016.2   0.063       0
  5129.3   0.035       0  5349.4    0.05       0
Bank Sta=5012.2,5016.2
Exp/Cntr=0.3,0.1

Type RM Length L Ch R = 1,3203,416,416,416
BEGIN DESCRIPTION:
Stream0824 7.0
END DESCRIPTION:
XS GIS Cut Line= 3
      2471172.84     13598853.00      2471025.00     13599375.00
      2471325.00     13599675.00
#Sta/Elev= 30
  4449.2  251.30  4482.5  250.98  4616.4  247.35  4828.6  240.52  4867.7  238.01
  4896.5  235.00  4901.7  235.05  4919.0  232.77  4937.2  232.14  4972.8  231.53
  4973.0  231.03  4976.5  231.03  4976.8  231.53  5020.0  232.16  5034.2  233.43
  5048.3  233.69  5076.6  236.51  5104.9  236.75  5121.0  235.91  5129.5  234.84
  5133.2  234.38  5147.3  235.34  5161.4  239.23  5175.6  240.70  5189.7  240.84
  5203.9  242.37  5260.4  243.47  5306.9  246.98  5400.0  252.65  5416.0  253.74
#Mann=9,-1,0
  4449.2   0.035       0  4616.4    0.05       0  4937.2   0.035       0
  4972.8   0.035       0  4976.8   0.035       0  5121.0   0.063       0
  5129.5   0.035       0  5306.9    0.07       0  5400.0    0.05       0
Bank Sta=4972.8,4976.8
Exp/Cntr=0.3,0.1

Type RM Length L Ch R = 1,2787,213,213,213
BEGIN DESCRIPTION:
Stream0824 6.0
END DESCRIPTION:
XS GIS Cut Line= 3
      2470408.97     13599651.61      2470797.84     13599679.38
      2471125.00     13599775.00
#Sta/Elev= 30
  4479.2  248.01  4625.6  237.29  4695.8  233.50  4715.8  230.19  4739.1  228.40
  4755.9  226.46  4812.5  225.58  4824.1  225.45  4824.4  224.95  4827.9  224.95
  4828.1  225.45  4869.1  227.27  4871.3  228.73  4876.5  230.05  4882.0  230.65
  4904.7  232.58  4938.2  233.03  4949.4  232.57  4970.3  230.19  4982.1  228.18
  4991.1  228.24  5015.5  230.14  5022.4  232.12  5032.8  233.20  5082.4  237.06
  5096.7  237.52  5121.1  238.60  5126.6  239.54  5141.0  240.28  5209.9  244.53
#Mann=7,-1,0
  4479.2    0.05       0  4812.5   0.035       0  4824.1    0.05       0
  4828.1   0.035       0  4882.0   0.063       0  5096.7   0.035       0
  5141.0    0.07       0
Bank Sta=4824.1,4828.1
Exp/Cntr=0.3,0.1

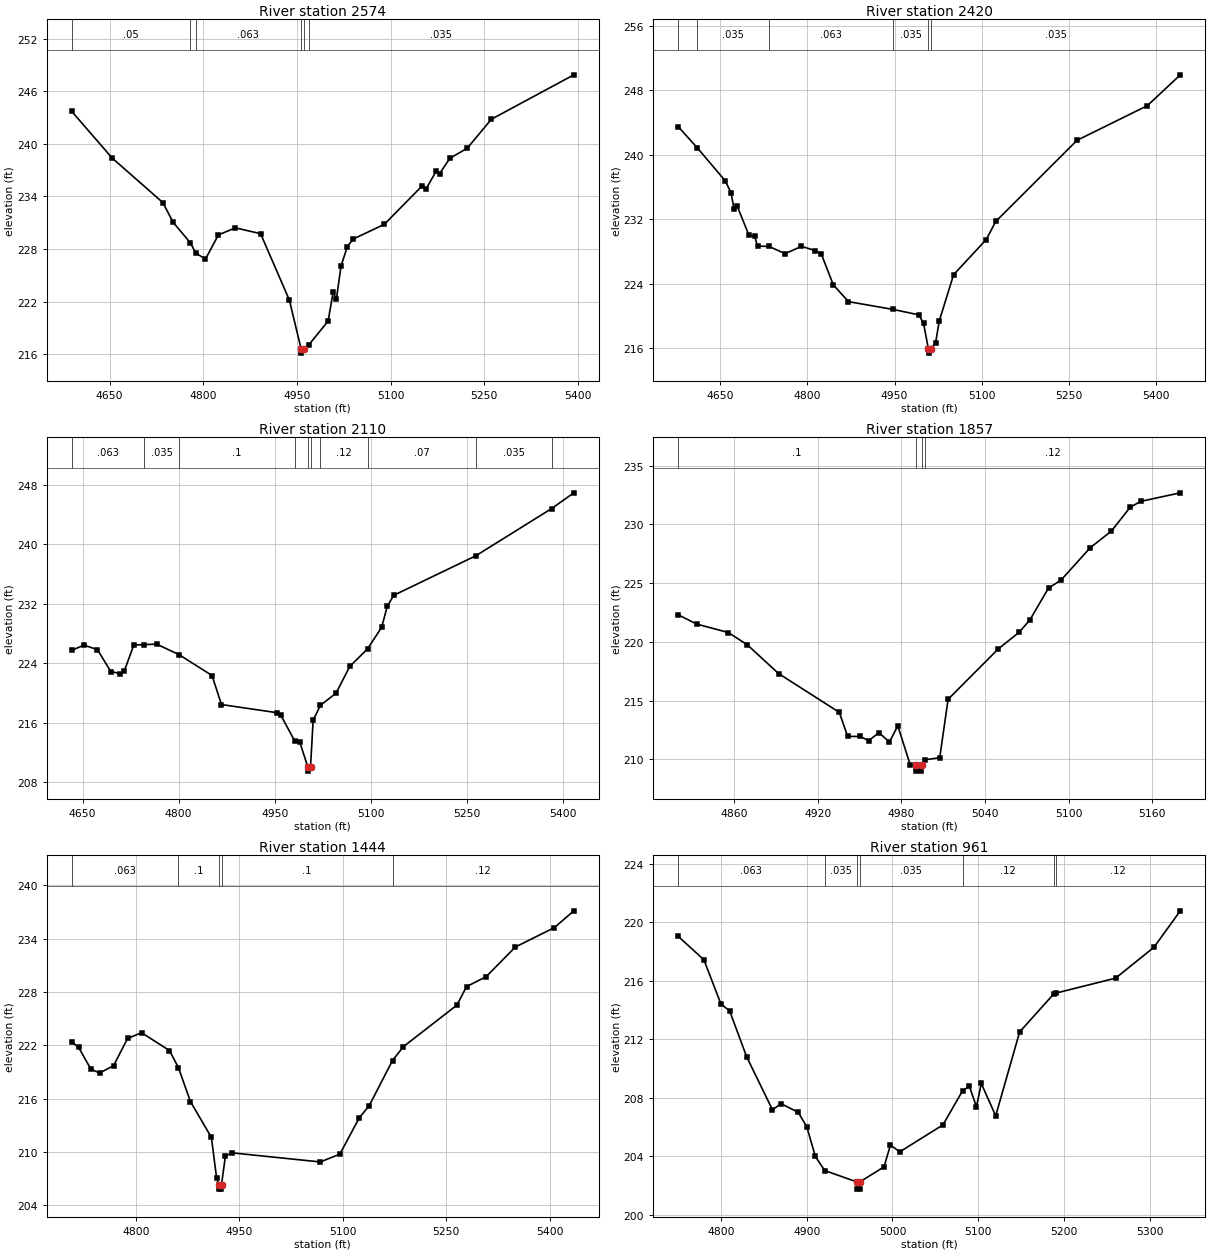
Type RM Length L Ch R = 1,2574,154,154,154
BEGIN DESCRIPTION:
Stream0824 5.0
END DESCRIPTION:
XS GIS Cut Line= 3
      2470427.61     13599793.42      2470859.57     13599906.22
      2471177.42     13600070.63
#Sta/Elev= 30
  4589.2  243.72  4654.3  238.37  4735.2  233.31  4751.9  231.04  4779.3  228.72
  4788.0  227.55  4803.5  226.85  4824.2  229.62  4851.4  230.42  4891.8  229.76
  4937.9  222.18  4956.6  216.63  4956.8  216.13  4960.6  216.63  4968.9  217.06
  4999.9  219.78  5008.0  223.09  5013.2  222.30  5020.6  226.05  5030.7  228.28
  5040.0  229.14  5089.9  230.82  5150.7  235.22  5156.3  234.80  5172.8  236.86
  5178.5  236.61  5195.0  238.36  5222.8  239.51  5261.4  242.81  5393.5  247.88
#Mann=6,-1,0
  4589.2    0.05       0  4779.3   0.035       0  4788.0   0.063       0
  4956.6   0.035       0  4960.6   0.063       0  4968.9   0.035       0
Bank Sta=4956.6,4960.6
Exp/Cntr=0.3,0.1

Type RM Length L Ch R = 1,2420,310,310,310
BEGIN DESCRIPTION:
H21110
END DESCRIPTION:
XS GIS Cut Line= 2
      2470367.07     13599925.48      2471201.75     13600145.13
#Sta/Elev= 30
  4578.0  243.51  4611.3  240.84  4658.6  236.81  4668.9  235.32  4674.2  233.23
  4679.4  233.67  4699.9  229.99  4709.4  229.88  4714.6  228.68  4734.2  228.63
  4762.0  227.74  4790.0  228.64  4813.7  228.12  4824.0  227.71  4844.7  223.87
  4870.7  221.78  4947.7  220.81  4991.7  220.14  4999.8  219.10  5008.2  215.89
  5008.4  215.39  5012.2  215.89  5020.5  216.66  5026.8  219.38  5051.5  225.13
  5107.5  229.48  5123.9  231.73  5263.6  241.80  5384.6  246.11  5441.1  249.93
#Mann=6,-1,0
  4578.0    0.05       0  4611.3   0.035       0  4734.2   0.063       0
  4947.7   0.035       0  5008.2   0.035       0  5012.2   0.035       0
Bank Sta=5008.2,5012.2
Exp/Cntr=0.3,0.1

Type RM Length L Ch R = 1,2110,253,253,253
BEGIN DESCRIPTION:
H21109
END DESCRIPTION:
XS GIS Cut Line= 3
      2470419.38     13600115.33      2470812.80     13600390.45
      2471111.34     13600445.23
#Sta/Elev= 30
  4633.0  225.73  4652.1  226.44  4673.2  225.84  4694.1  222.89  4709.0  222.61
  4715.1  222.94  4729.9  226.45  4746.1  226.51  4765.6  226.57  4800.4  225.17
  4852.0  222.36  4866.8  218.46  4953.1  217.37  4959.2  217.06  4981.5  213.50
  4988.9  213.44  5001.7  210.02  5002.0  209.52  5005.7  210.02  5009.8  216.34
  5021.0  218.34  5045.6  219.99  5066.9  223.57  5094.7  225.94  5116.7  228.82
  5125.5  231.66  5135.6  233.13  5263.7  238.44  5381.8  244.77  5416.6  246.89
#Mann=10,-1,0
  4633.0   0.063       0  4746.1   0.035       0  4800.4     0.1       0
  4981.5    0.07       0  5001.7    0.05       0  5005.7    0.07       0
  5021.0    0.12       0  5094.7    0.07       0  5263.7   0.035       0
  5381.8    0.07       0
Bank Sta=5001.7,5005.7
Exp/Cntr=0.3,0.1

Type RM Length L Ch R = 1,1857,413,413,413
BEGIN DESCRIPTION:
Stream0824 4.0
END DESCRIPTION:
XS GIS Cut Line= 3
      2470475.00     13600375.01      2470575.00     13600525.00
      2470724.96     13600624.97
#Sta/Elev= 30
  4819.7  222.31  4833.2  221.51  4855.7  220.80  4869.3  219.76  4891.8  217.31
  4935.4  214.01  4941.4  211.96  4950.4  211.96  4956.4  211.60  4963.9  212.28
  4971.4  211.48  4977.4  212.87  4986.4  209.51  4990.5  209.51  4990.7  209.01
  4994.2  209.01  4994.5  209.51  4996.6  209.97  5007.5  210.15  5013.5  215.12
  5049.5  219.40  5064.6  220.83  5072.1  221.85  5085.6  224.58  5094.6  225.26
  5115.6  228.02  5130.7  229.42  5144.2  231.45  5151.7  231.95  5180.2  232.68
#Mann=4,-1,0
  4819.7     0.1       0  4990.5    0.05       0  4994.5     0.1       0
  4996.6    0.12       0
Bank Sta=4990.5,4994.5
Exp/Cntr=0.3,0.1

Type RM Length L Ch R = 1,1444,483,483,483
BEGIN DESCRIPTION:
Stream0824 3.0
END DESCRIPTION:
XS GIS Cut Line= 3
      2470225.00     13600375.03      2470275.00     13600675.00
      2470575.02     13600975.02
#Sta/Elev= 30
  4706.6  222.38  4716.7  221.77  4734.5  219.31  4747.1  218.88  4767.4  219.71
  4787.7  222.77  4808.0  223.42  4848.5  221.41  4861.5  219.48  4878.9  215.67
  4909.3  211.63  4916.9  207.03  4920.0  206.31  4920.3  205.81  4923.8  205.81
  4924.0  206.31  4929.6  209.55  4939.7  209.89  5067.3  208.87  5095.6  209.75
  5123.8  213.84  5138.0  215.18  5172.0  220.29  5187.5  221.83  5265.3  226.52
  5279.4  228.61  5307.7  229.72  5350.1  233.06  5406.7  235.25  5435.0  237.14
#Mann=5,-1,0
  4706.6   0.063       0  4861.5     0.1       0  4920.0    0.05       0
  4924.0     0.1       0  5172.0    0.12       0
Bank Sta=4920,4924
Exp/Cntr=0.3,0.1

Type RM Length L Ch R = 1,961,476,476,476
BEGIN DESCRIPTION:
Stream0824 2.0
END DESCRIPTION:
XS GIS Cut Line= 3
      2469925.00     13600674.99      2469925.00     13600925.00
      2470224.98     13601074.99
#Sta/Elev= 30
  4750.1  219.04  4780.1  217.44  4800.1  214.40  4810.1  213.95  4830.1  210.79
  4860.1  207.18  4870.1  207.60  4890.1  207.01  4900.1  206.02  4910.1  203.99
  4921.0  203.03  4958.1  202.26  4958.4  201.76  4961.9  201.76  4962.1  202.26
  4990.1  203.28  4997.6  204.77  5008.5  204.31  5058.8  206.15  5081.7  208.48
  5089.6  208.79  5097.9  207.39  5103.5  208.98  5120.3  206.77  5148.2  212.50
  5188.1  215.11  5190.1  215.15  5260.1  216.18  5304.8  218.29  5335.5  220.78
#Mann=7,-1,0
  4750.1   0.063       0  4921.0   0.035       0  4958.1   0.035       0
  4962.1   0.035       0  5081.7    0.12       0  5188.1     0.1       0
  5190.1    0.12       0
Bank Sta=4958.1,4962.1
Exp/Cntr=0.3,0.1

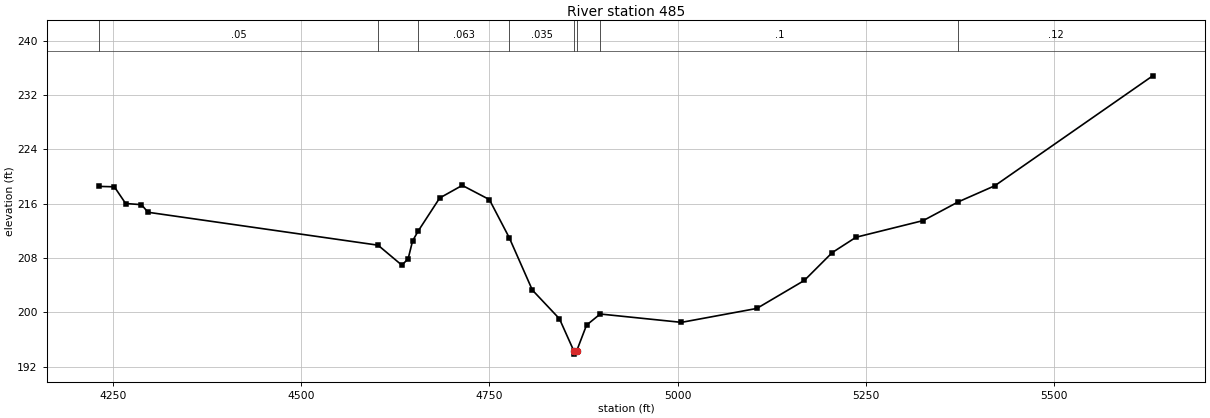
Type RM Length L Ch R = 1,485,0,0,0
BEGIN DESCRIPTION:
Stream0824 1.0
END DESCRIPTION:
XS GIS Cut Line= 3
      2469300.27     13600641.17      2469725.00     13601275.00
      2470328.88     13601476.55
#Sta/Elev= 30
  4231.7  218.56  4251.8  218.50  4266.8  216.04  4287.8  215.87  4296.5  214.75
  4602.1  209.90  4633.6  206.97  4642.0  207.85  4648.0  210.53  4655.5  211.99
  4684.0  216.85  4714.0  218.71  4750.0  216.62  4776.4  211.01  4807.1  203.29
  4843.1  199.06  4862.1  194.35  4862.4  193.85  4866.1  194.35  4879.1  198.12
  4897.3  199.76  5005.2  198.53  5105.3  200.58  5168.5  204.71  5205.5  208.81
  5237.1  211.07  5326.5  213.53  5373.1  216.29  5421.4  218.65  5631.3  234.85
#Mann=8,-1,0
  4231.7    0.05       0  4602.1   0.035       0  4655.5   0.063       0
  4776.4   0.035       0  4862.1    0.05       0  4866.1   0.035       0
  4897.3     0.1       0  5373.1    0.12       0
Bank Sta=4862.1,4866.1
Exp/Cntr=0.3,0.1

Chan Stop Cuts=-1