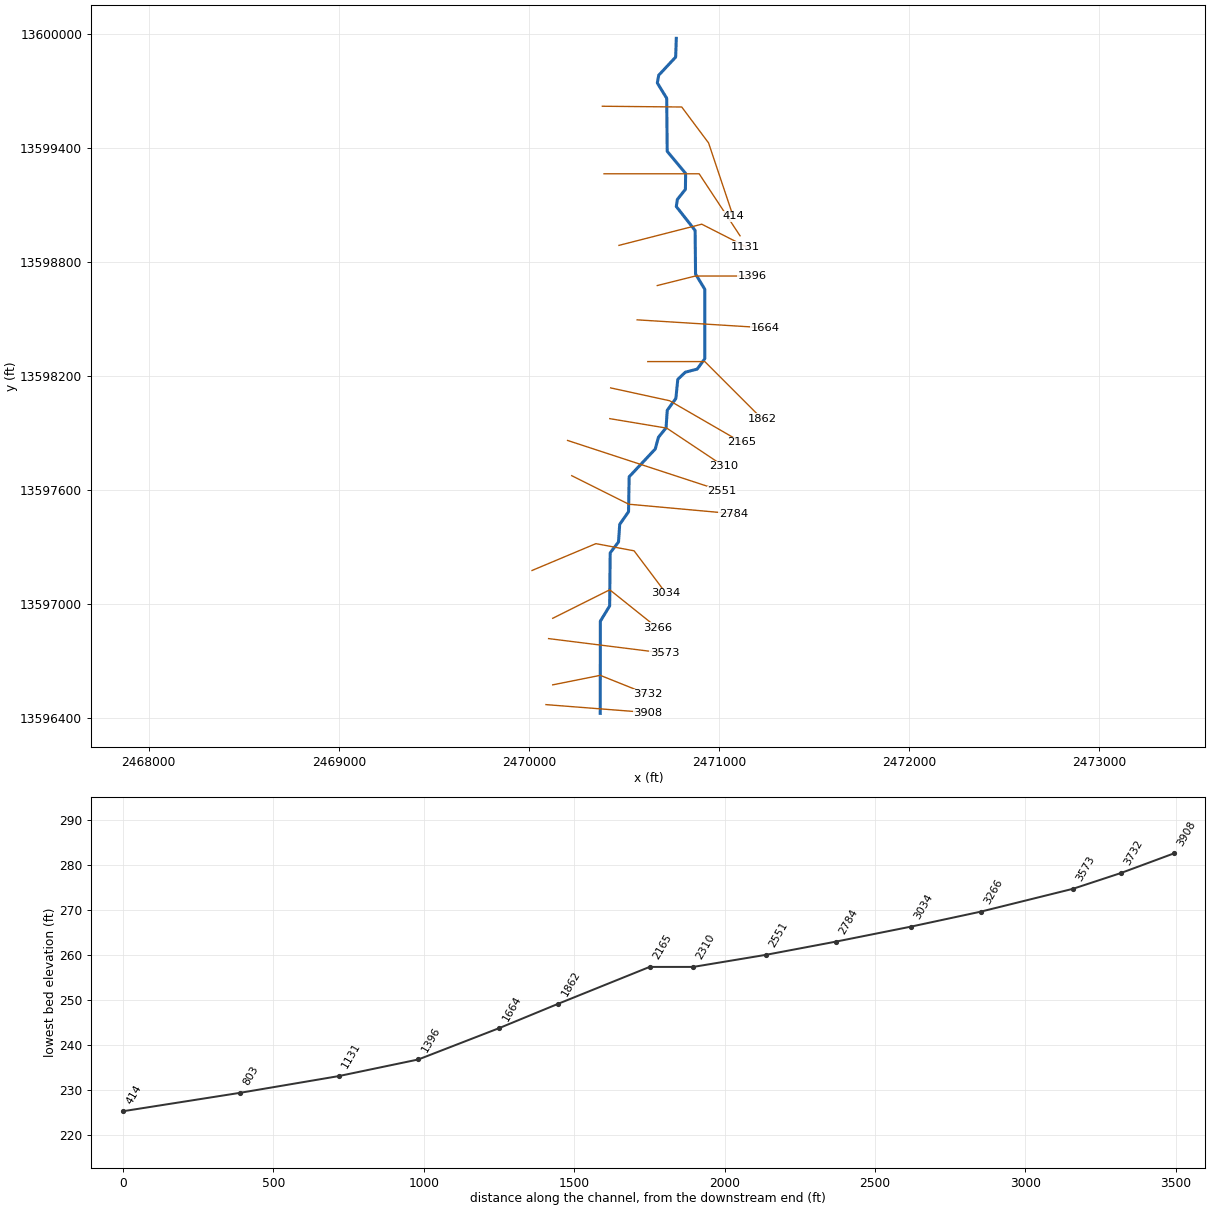
--- Stream0825.prj (project) ---

Proj Title=Stream0825 Base Level Engineering
Current Plan=p01
Default Exp/Contr=0.3,0.1
English Units
Geom File=g01
Flow File=f01
Plan File=p01
BEGIN DESCRIPTION:
Stream0825
END DESCRIPTION:

--- Stream0825.p01 (plan) ---

Plan Title=Multiple Run
Short Identifier=Multiple
Geom File=g01
Flow File=f01
Subcritical Flow
K Sum by GR= 0
Std Step Tol= 0.01
Critical Tol= 0.01
Num of Std Step Trials= 20
Max Error Tol= 0.3
Flow Tol Ratio= 0.001
Split Flow NTrial= 30
Split Flow Tol= 0.02
Split Flow Ratio= 0.02
Log Output Level= 0
Friction Slope Method= 1
Unsteady Friction Slope Method= 2
Unsteady Bridges Friction Slope Method= 1
Parabolic Critical Depth
Global Vel Dist=  1 , 1 , 1
Global Log Level= 0
CheckData=True
Encroach Param= -1, 0, 0, 0
BEGIN DESCRIPTION:
Multiple Run
END DESCRIPTION:

--- Stream0825.f01 (steady flow) ---

Flow Title=Multiple
Number of Profiles=7
Profile Names=10-year,25-year,50-year,1pct_min,100-year,1pct_plu,500-year
River Rch & RM= Stream0825,Reach-1,3908
     284     439     573     365     728    1453    1158
Boundary for River Rch & Prof#=Stream0825,Reach-1,1
Up Type=0
Dn Type=3
Dn Slope=0.005
Boundary for River Rch & Prof#=Stream0825,Reach-1,2
Up Type=0
Dn Type=3
Dn Slope=0.005
Boundary for River Rch & Prof#=Stream0825,Reach-1,3
Up Type=0
Dn Type=3
Dn Slope=0.005
Boundary for River Rch & Prof#=Stream0825,Reach-1,4
Up Type=0
Dn Type=3
Dn Slope=0.005
Boundary for River Rch & Prof#=Stream0825,Reach-1,5
Up Type=0
Dn Type=3
Dn Slope=0.005
Boundary for River Rch & Prof#=Stream0825,Reach-1,6
Up Type=0
Dn Type=3
Dn Slope=0.005
Boundary for River Rch & Prof#=Stream0825,Reach-1,7
Up Type=0
Dn Type=3
Dn Slope=0.005

--- Stream0825.g01 (geometry) ---

Geom Title=Existing Conditions

River Reach=Stream0825,Reach-1
Reach XY= 30
      2470375.00     13596425.00      2470375.52     13596909.78
      2470424.48     13596990.22      2470427.26     13597269.06
      2470471.14     13597326.60      2470477.36     13597419.02
      2470523.78     13597485.50      2470527.06     13597669.15
      2470664.24     13597815.32      2470681.14     13597877.17
      2470721.18     13597926.58      2470727.35     13598019.03
      2470772.64     13598080.98      2470782.75     13598181.45
      2470822.45     13598219.25      2470885.04     13598235.63
      2470924.67     13598290.03      2470924.93     13598654.97
      2470876.22     13598735.50      2470873.94     13598964.56
      2470774.96     13599090.34      2470780.36     13599127.17
      2470822.81     13599180.97      2470824.06     13599264.52
      2470727.07     13599380.86      2470724.46     13599659.79
      2470675.03     13599740.42      2470682.50     13599781.05
      2470771.60     13599876.41      2470775.00     13599975.00

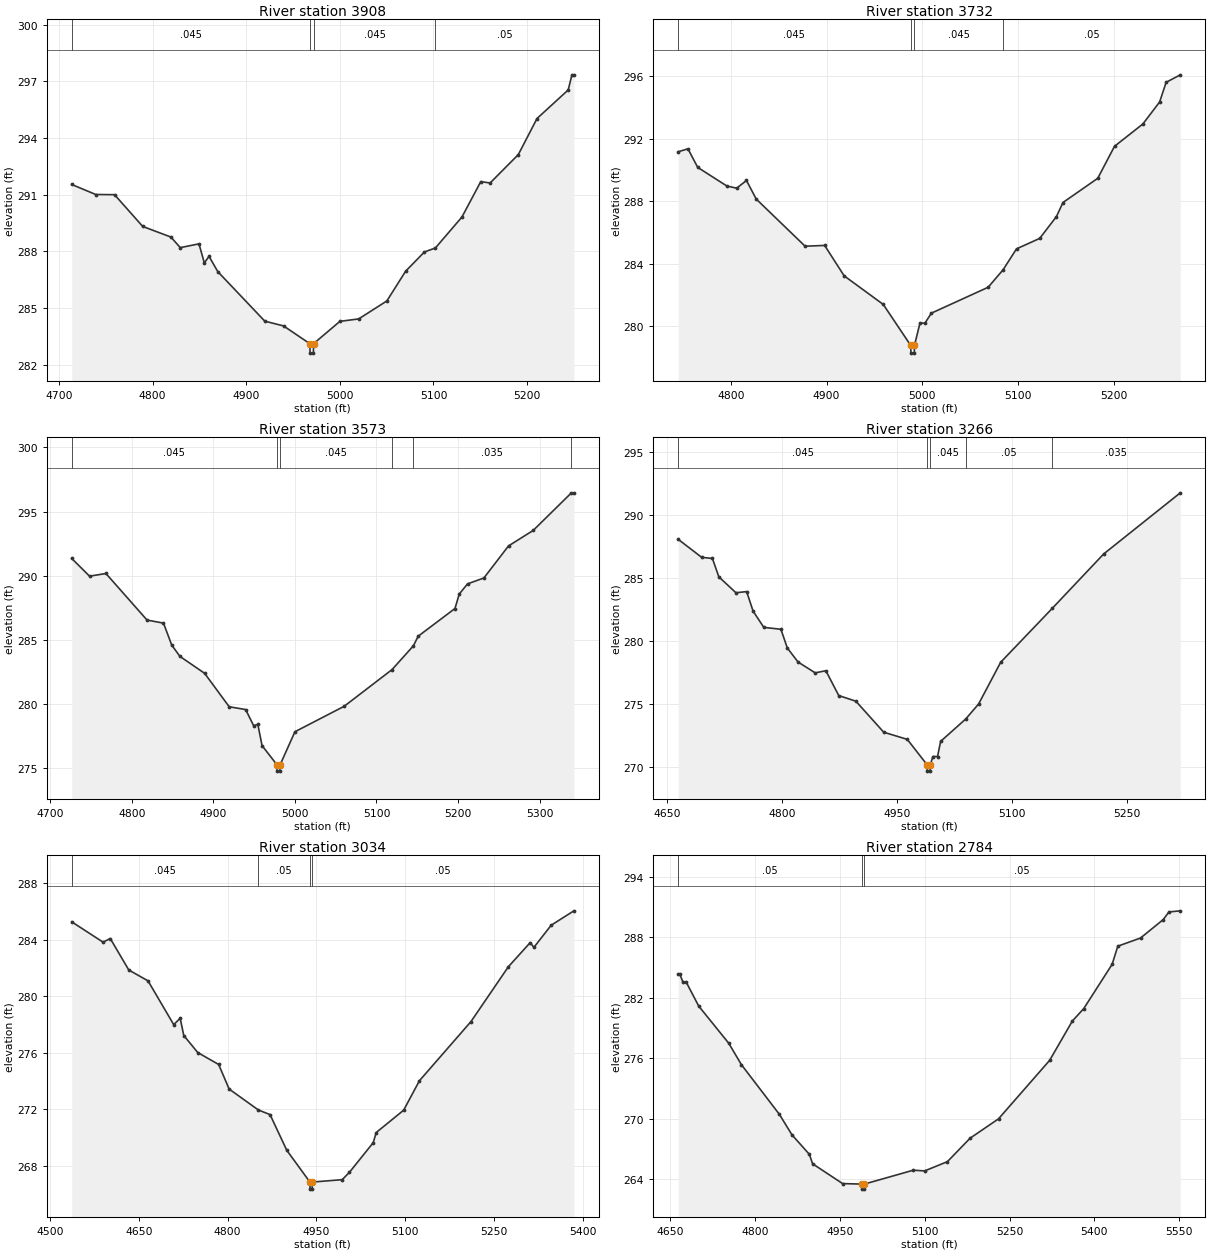
Type RM Length L Ch R = 1,3908,176,176,176
BEGIN DESCRIPTION:
XS7789
END DESCRIPTION:
XS GIS Cut Line= 2
      2470089.46     13596471.05      2470624.24     13596429.38
#Sta/Elev= 30
  4713.6  291.54  4739.2  291.01  4759.3  291.00  4789.4  289.32  4819.5  288.76
  4829.5  288.20  4849.5  288.40  4855.2  287.39  4860.2  287.74  4869.6  286.93
  4919.8  284.31  4939.8  284.06  4967.9  283.12  4968.2  282.62  4971.7  282.62
  4971.9  283.12  5000.0  284.30  5020.1  284.43  5050.2  285.38  5070.2  286.95
  5090.3  287.97  5102.0  288.18  5130.4  289.82  5150.5  291.69  5160.5  291.62
  5190.6  293.12  5210.6  295.03  5243.9  296.54  5247.9  297.34  5250.0  297.34
#Mann=4,-1,0
  4713.6   0.045       0  4967.9   0.045       0  4971.9   0.045       0
  5102.0    0.05       0
Bank Sta=4967.9,4971.9
Exp/Cntr=0.3,0.1

Type RM Length L Ch R = 1,3732,159,159,159
BEGIN DESCRIPTION:
Stream0825 6.0
END DESCRIPTION:
XS GIS Cut Line= 3
      2470125.04     13596575.01      2470375.00     13596625.00
      2470625.03     13596524.99
#Sta/Elev= 30
  4745.1  291.16  4755.3  291.35  4765.5  290.16  4796.1  288.96  4806.2  288.83
  4816.4  289.32  4826.6  288.13  4877.6  285.11  4898.0  285.16  4918.4  283.21
  4959.2  281.38  4987.8  278.76  4988.1  278.26  4991.6  278.26  4991.8  278.76
  4997.5  280.18  5002.7  280.18  5009.4  280.82  5068.7  282.48  5084.3  283.60
  5098.3  284.94  5122.5  285.61  5140.0  287.01  5146.8  287.91  5183.1  289.46
  5200.6  291.51  5230.2  292.94  5247.7  294.35  5254.5  295.61  5269.3  296.09
#Mann=4,-1,0
  4745.1   0.045       0  4987.8   0.045       0  4991.8   0.045       0
  5084.3    0.05       0
Bank Sta=4987.8,4991.8
Exp/Cntr=0.3,0.1

Type RM Length L Ch R = 1,3573,307,307,307
BEGIN DESCRIPTION:
XS7788
END DESCRIPTION:
XS GIS Cut Line= 2
      2470103.39     13596818.27      2470714.54     13596741.88
#Sta/Elev= 30
  4726.3  291.34  4748.1  289.96  4768.2  290.17  4818.6  286.54  4838.8  286.30
  4848.9  284.59  4858.9  283.71  4889.2  282.39  4919.4  279.78  4939.6  279.56
  4949.4  278.30  4954.5  278.41  4959.7  276.75  4977.9  275.26  4978.1  274.76
  4981.6  274.76  4981.9  275.26  5000.0  277.83  5060.5  279.82  5119.2  282.68
  5145.3  284.53  5151.2  285.28  5196.3  287.44  5201.6  288.57  5211.7  289.36
  5231.8  289.82  5262.0  292.32  5292.3  293.53  5339.0  296.45  5342.2  296.46
#Mann=6,-1,0
  4726.3   0.045       0  4977.9   0.045       0  4981.9   0.045       0
  5119.2    0.05       0  5145.3   0.035       0  5339.0    0.05       0
Bank Sta=4977.9,4981.9
Exp/Cntr=0.3,0.1

Type RM Length L Ch R = 1,3266,232,232,232
BEGIN DESCRIPTION:
Stream0825 5.0
END DESCRIPTION:
XS GIS Cut Line= 3
      2470125.02     13596925.01      2470425.00     13597075.00
      2470674.96     13596875.03
#Sta/Elev= 30
  4664.5  288.07  4695.2  286.64  4709.2  286.55  4717.6  285.09  4739.9  283.83
  4753.9  283.92  4762.3  282.37  4776.3  281.08  4798.6  280.93  4807.0  279.44
  4821.0  278.33  4843.4  277.47  4857.3  277.64  4874.1  275.67  4896.5  275.22
  4932.8  272.76  4963.6  272.19  4989.5  270.17  4989.8  269.67  4993.3  269.67
  4993.5  270.17  4997.1  270.83  5003.1  270.83  5007.1  272.03  5039.9  273.81
  5056.7  275.00  5085.5  278.31  5153.0  282.60  5220.0  286.91  5320.0  291.76
#Mann=5,-1,0
  4664.5   0.045       0  4989.5   0.045       0  4993.5   0.045       0
  5039.9    0.05       0  5153.0   0.035       0
Bank Sta=4989.5,4993.5
Exp/Cntr=0.3,0.1

Type RM Length L Ch R = 1,3034,250,250,250
BEGIN DESCRIPTION:
H21124
END DESCRIPTION:
XS GIS Cut Line= 4
      2470016.23     13597176.47      2470352.20     13597317.62
      2470553.00     13597279.85      2470720.99     13597056.52
#Sta/Elev= 30
  4536.7  285.27  4589.6  283.83  4601.7  284.09  4633.0  281.86  4665.5  281.09
  4708.9  277.99  4719.8  278.44  4725.9  277.22  4749.6  276.01  4784.8  275.17
  4802.5  273.43  4852.1  271.94  4871.6  271.62  4899.9  269.09  4939.0  266.84
  4939.2  266.34  4942.7  266.34  4943.0  266.84  4993.5  267.01  5005.7  267.53
  5045.9  269.63  5051.0  270.35  5097.3  271.93  5124.0  274.02  5211.1  278.21
  5274.2  282.09  5311.1  283.80  5317.3  283.46  5346.5  285.03  5384.9  286.05
#Mann=4,-1,0
  4536.7   0.045       0  4852.1    0.05       0  4939.0    0.05       0
  4943.0    0.05       0
Bank Sta=4939,4943
Exp/Cntr=0.3,0.1

Type RM Length L Ch R = 1,2784,233,233,233
BEGIN DESCRIPTION:
Stream0825 4.0
END DESCRIPTION:
XS GIS Cut Line= 3
      2470225.01     13597674.99      2470525.00     13597525.00
      2471075.03     13597475.00
#Sta/Elev= 30
  4664.2  284.36  4667.0  284.36  4672.6  283.57  4678.2  283.58  4700.5  281.18
  4753.6  277.49  4776.0  275.36  4843.1  270.43  4865.4  268.39  4896.2  266.45
  4901.8  265.52  4954.9  263.55  4989.2  263.50  4989.5  263.00  4993.0  263.00
  4993.2  263.50  5079.9  264.88  5100.0  264.81  5140.2  265.73  5180.3  268.06
  5230.5  269.98  5320.9  275.79  5361.1  279.70  5381.2  280.93  5431.4  285.33
  5441.4  287.13  5481.6  287.94  5521.7  289.77  5531.8  290.53  5551.9  290.64
#Mann=3,-1,0
  4664.2    0.05       0  4989.2    0.05       0  4993.2    0.05       0
Bank Sta=4989.2,4993.2
Exp/Cntr=0.3,0.1

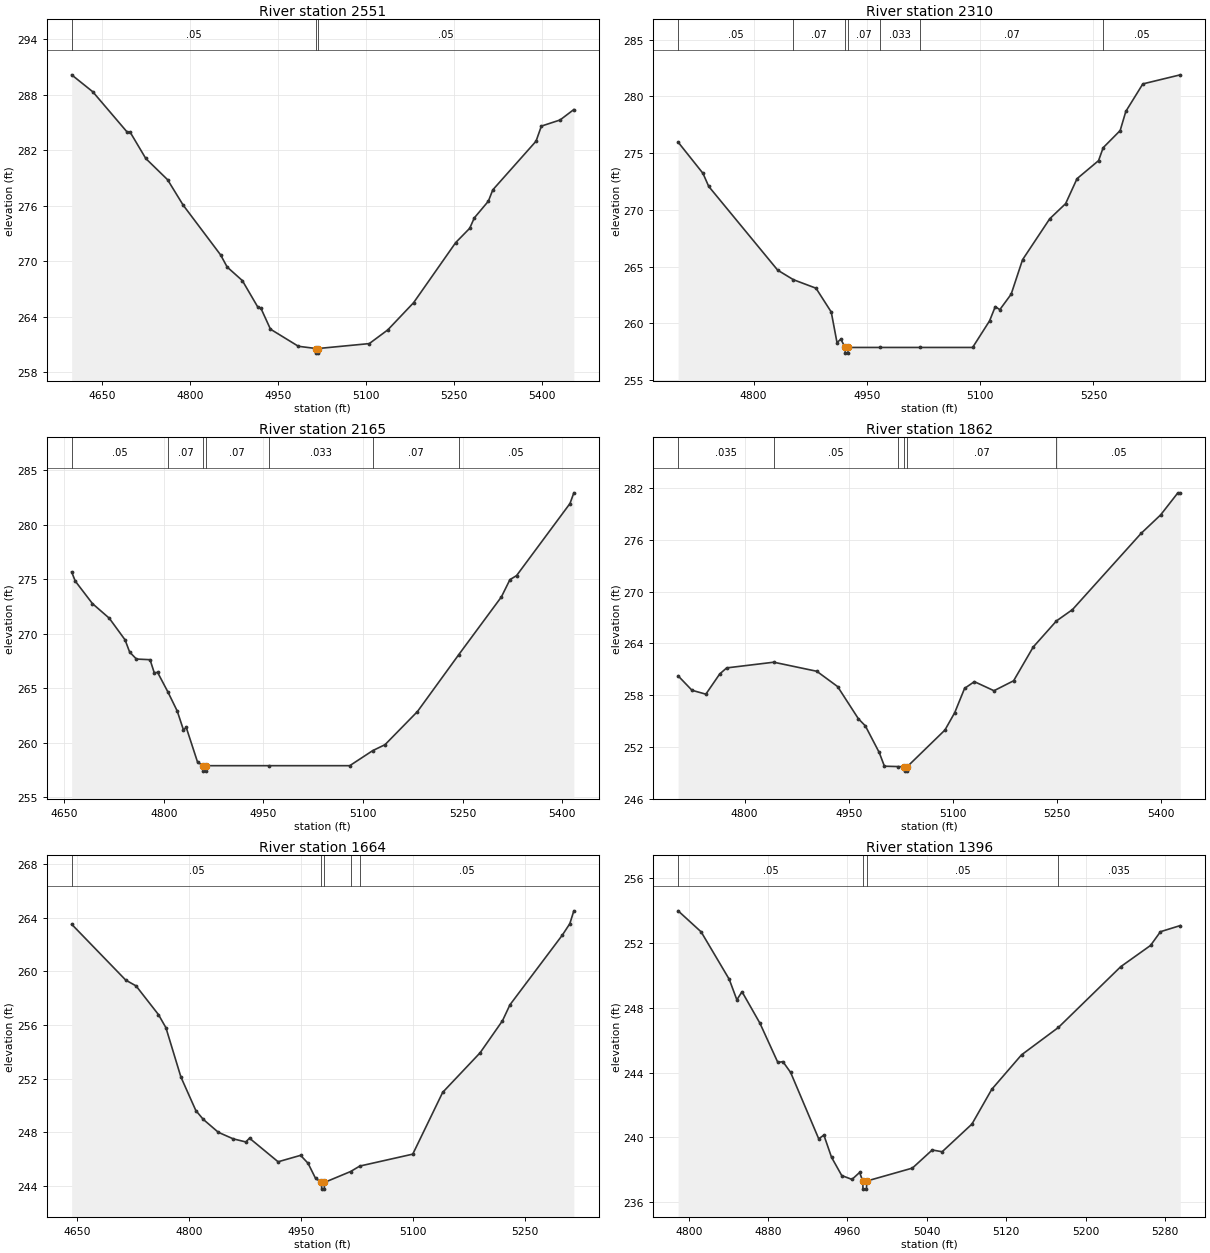
Type RM Length L Ch R = 1,2551,241,241,241
BEGIN DESCRIPTION:
H21123
END DESCRIPTION:
XS GIS Cut Line= 2
      2470203.13     13597860.36      2471016.21     13597593.97
#Sta/Elev= 30
  4598.1  290.13  4634.1  288.30  4692.6  283.95  4697.8  283.93  4724.4  281.09
  4761.5  278.80  4788.1  276.05  4851.8  270.68  4863.1  269.36  4888.9  267.90
  4915.5  265.01  4920.7  264.89  4936.8  262.65  4984.4  260.80  5014.3  260.56
  5014.5  260.06  5018.0  260.06  5018.3  260.56  5105.2  261.09  5136.7  262.57
  5180.7  265.51  5252.5  272.01  5276.3  273.55  5284.1  274.67  5308.1  276.48
  5315.6  277.70  5389.3  282.96  5398.4  284.59  5430.2  285.25  5453.7  286.38
#Mann=3,-1,0
  4598.1    0.05       0  5014.3    0.05       0  5018.3    0.05       0
Bank Sta=5014.3,5018.3
Exp/Cntr=0.3,0.1

Type RM Length L Ch R = 1,2310,145,145,145
BEGIN DESCRIPTION:
Stream0825 3.0
END DESCRIPTION:
XS GIS Cut Line= 3
      2470425.02     13597975.00      2470725.00     13597925.00
      2471025.02     13597724.99
#Sta/Elev= 30
  4700.2  275.97  4733.1  273.22  4740.7  272.07  4832.0  264.69  4852.8  263.85
  4882.7  263.10  4902.9  261.00  4910.5  258.31  4915.6  258.61  4921.2  257.88
  4921.5  257.38  4925.0  257.38  4925.2  257.88  4967.5  257.88  5019.7  257.88
  5090.0  257.88  5112.5  260.23  5120.0  261.48  5126.0  261.21  5141.0  262.57
  5156.1  265.61  5192.1  269.22  5213.1  270.55  5228.2  272.75  5256.7  274.34
  5262.8  275.48  5285.3  276.99  5292.8  278.68  5315.3  281.10  5364.9  281.90
#Mann=7,-1,0
  4700.2    0.05       0  4852.8    0.07       0  4921.2   0.033       0
  4925.2    0.07       0  4967.5   0.033       0  5019.7    0.07       0
  5262.8    0.05       0
Bank Sta=4921.2,4925.2
Exp/Cntr=0.3,0.1

Type RM Length L Ch R = 1,2165,303,303,303
BEGIN DESCRIPTION:
H21122
END DESCRIPTION:
XS GIS Cut Line= 3
      2470429.70     13598136.72      2470739.88     13598069.12
      2471119.45     13597849.68
#Sta/Elev= 30
  4661.4  275.67  4666.8  274.83  4692.7  272.76  4718.0  271.42  4741.8  269.43
  4748.7  268.31  4758.9  267.67  4779.4  267.61  4785.7  266.42  4790.8  266.44
  4806.1  264.67  4820.3  262.90  4829.7  261.16  4833.9  261.39  4851.0  258.19
  4859.3  257.88  4859.5  257.38  4863.0  257.38  4863.3  257.88  4957.8  257.88
  5080.0  257.88  5114.5  259.26  5133.1  259.81  5181.9  262.85  5243.9  268.06
  5308.2  273.37  5321.1  274.96  5331.1  275.33  5411.5  281.95  5417.3  282.93
#Mann=7,-1,0
  4661.4    0.05       0  4806.1    0.07       0  4859.3   0.033       0
  4863.3    0.07       0  4957.8   0.033       0  5114.5    0.07       0
  5243.9    0.05       0
Bank Sta=4859.3,4863.3
Exp/Cntr=0.3,0.1

Type RM Length L Ch R = 1,1862,198,198,198
BEGIN DESCRIPTION:
Stream0825 2.0
END DESCRIPTION:
XS GIS Cut Line= 3
      2470625.05     13598275.00      2470925.00     13598275.00
      2471224.99     13597975.01
#Sta/Elev= 30
  4704.1  260.24  4724.1  258.57  4744.1  258.12  4764.1  260.46  4774.1  261.16
  4842.0  261.82  4904.1  260.77  4934.1  259.00  4964.1  255.27  4974.1  254.45
  4994.1  251.37  5001.6  249.78  5020.7  249.74  5030.3  249.71  5030.6  249.21
  5034.1  249.21  5034.3  249.71  5088.9  253.97  5103.0  255.98  5117.2  258.79
  5131.3  259.57  5159.6  258.52  5187.9  259.67  5216.2  263.58  5249.7  266.60
  5272.8  267.91  5371.7  276.73  5400.0  278.88  5424.8  281.43  5428.3  281.43
#Mann=6,-1,0
  4704.1   0.035       0  4842.0    0.05       0  5020.7    0.07       0
  5030.3    0.05       0  5034.3    0.07       0  5249.7    0.05       0
Bank Sta=5030.3,5034.3
Exp/Cntr=0.3,0.1

Type RM Length L Ch R = 1,1664,268,268,268
BEGIN DESCRIPTION:
H21121
END DESCRIPTION:
XS GIS Cut Line= 2
      2470568.90     13598494.57      2471240.41     13598452.85
#Sta/Elev= 30
  4643.2  263.51  4715.7  259.34  4729.5  258.91  4759.5  256.77  4769.5  255.79
  4789.6  252.11  4809.6  249.61  4819.6  248.95  4839.7  247.99  4859.7  247.50
  4876.5  247.27  4881.5  247.55  4919.8  245.79  4949.9  246.27  4959.9  245.68
  4969.9  244.56  4977.9  244.25  4978.2  243.75  4981.7  243.75  4981.9  244.25
  5016.8  245.06  5029.2  245.47  5100.2  246.36  5140.3  250.97  5190.4  253.92
  5220.4  256.31  5230.4  257.50  5300.6  262.70  5310.6  263.55  5316.0  264.51
#Mann=5,-1,0
  4643.2    0.05       0  4977.9    0.05       0  4981.9    0.05       0
  5016.8   0.035       0  5029.2    0.05       0
Bank Sta=4977.9,4981.9
Exp/Cntr=0.3,0.1

Type RM Length L Ch R = 1,1396,265,265,265
BEGIN DESCRIPTION:
Stream0825 1.0
END DESCRIPTION:
XS GIS Cut Line= 3
      2470675.02     13598675.01      2470875.00     13598725.00
      2471174.97     13598725.00
#Sta/Elev= 30
  4789.3  254.00  4812.5  252.70  4840.8  249.77  4848.5  248.50  4853.7  249.00
  4871.7  247.06  4889.8  244.63  4894.9  244.68  4902.7  244.01  4931.0  239.91
  4936.2  240.14  4943.9  238.77  4954.2  237.64  4964.5  237.40  4972.2  237.83
  4975.4  237.30  4975.6  236.80  4979.1  236.80  4979.4  237.30  5025.4  238.10
  5045.4  239.22  5055.4  239.11  5085.4  240.82  5105.4  242.97  5135.4  245.10
  5172.5  246.79  5235.4  250.55  5265.4  251.86  5275.4  252.71  5295.4  253.09
#Mann=4,-1,0
  4789.3    0.05       0  4975.4    0.05       0  4979.4    0.05       0
  5172.5   0.035       0
Bank Sta=4975.4,4979.4
Exp/Cntr=0.3,0.1

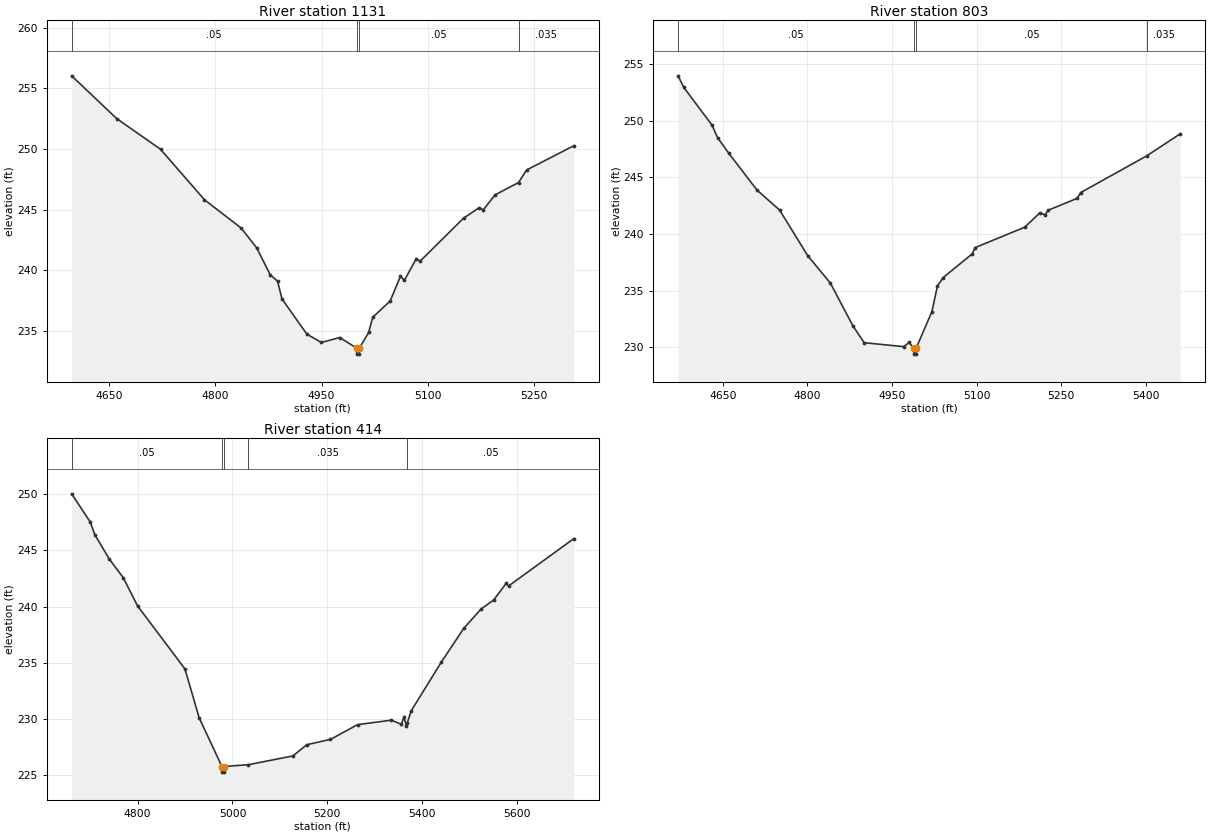
Type RM Length L Ch R = 1,1131,328,328,328
BEGIN DESCRIPTION:
H21120
END DESCRIPTION:
XS GIS Cut Line= 3
      2470473.48     13598886.23      2470908.87     13598997.56
      2471140.01     13598880.03
#Sta/Elev= 30
  4597.4  256.03  4660.9  252.51  4722.8  249.98  4784.8  245.82  4836.4  243.50
  4858.5  241.86  4877.7  239.63  4888.0  239.11  4894.2  237.65  4929.3  234.75
  4949.9  234.06  4975.8  234.47  4999.5  233.60  4999.8  233.10  5003.3  233.10
  5003.5  233.60  5016.6  234.89  5022.2  236.13  5046.8  237.47  5061.4  239.51
  5067.0  239.18  5083.6  240.95  5089.2  240.76  5150.4  244.30  5172.6  245.17
  5178.2  244.98  5194.9  246.22  5228.1  247.24  5239.4  248.27  5306.1  250.27
#Mann=4,-1,0
  4597.4    0.05       0  4999.5    0.05       0  5003.5    0.05       0
  5228.1   0.035       0
Bank Sta=4999.5,5003.5
Exp/Cntr=0.3,0.1

Type RM Length L Ch R = 1,803,389,389,389
BEGIN DESCRIPTION:
XS7786
END DESCRIPTION:
XS GIS Cut Line= 3
      2470395.02     13599262.72      2470895.07     13599262.72
      2471110.16     13598936.61
#Sta/Elev= 30
  4570.7  253.97  4580.7  252.95  4630.7  249.62  4640.7  248.51  4660.7  247.12
  4710.7  243.87  4750.7  242.11  4800.7  238.07  4840.7  235.66  4880.7  231.88
  4900.7  230.39  4970.7  230.04  4980.7  230.41  4988.7  229.88  4988.9  229.38
  4992.4  229.38  4992.7  229.88  5020.7  233.12  5030.7  235.41  5040.7  236.14
  5091.9  238.22  5097.9  238.80  5185.2  240.59  5212.3  241.86  5221.4  241.69
  5227.4  242.10  5278.6  243.15  5284.6  243.65  5401.9  246.90  5461.4  248.85
#Mann=4,-1,0
  4570.7    0.05       0  4988.7    0.05       0  4992.7    0.05       0
  5401.9   0.035       0
Bank Sta=4988.7,4992.7
Exp/Cntr=0.3,0.1

Type RM Length L Ch R = 1,414,0,0,0
BEGIN DESCRIPTION:
H21119
END DESCRIPTION:
XS GIS Cut Line= 4
      2470386.03     13599617.84      2470803.50     13599613.87
      2470944.65     13599425.00      2471073.77     13599039.62
#Sta/Elev= 30
  4660.7  250.03  4699.7  247.54  4709.7  246.39  4739.7  244.26  4769.7  242.57
  4799.7  240.07  4899.7  234.47  4929.7  230.13  4977.7  225.79  4977.9  225.29
  4981.4  225.29  4981.7  225.79  5033.6  225.95  5127.7  226.73  5156.9  227.73
  5206.9  228.20  5264.0  229.51  5335.6  229.91  5356.2  229.54  5361.9  230.17
  5367.1  229.43  5368.7  229.64  5377.2  230.74  5440.5  235.05  5488.1  238.07
  5524.9  239.80  5551.2  240.59  5577.5  242.06  5582.8  241.84  5720.4  246.05
#Mann=5,-1,0
  4660.7    0.05       0  4977.7    0.05       0  4981.7    0.05       0
  5033.6   0.035       0  5368.7    0.05       0
Bank Sta=4977.7,4981.7
Exp/Cntr=0.3,0.1

Chan Stop Cuts=-1