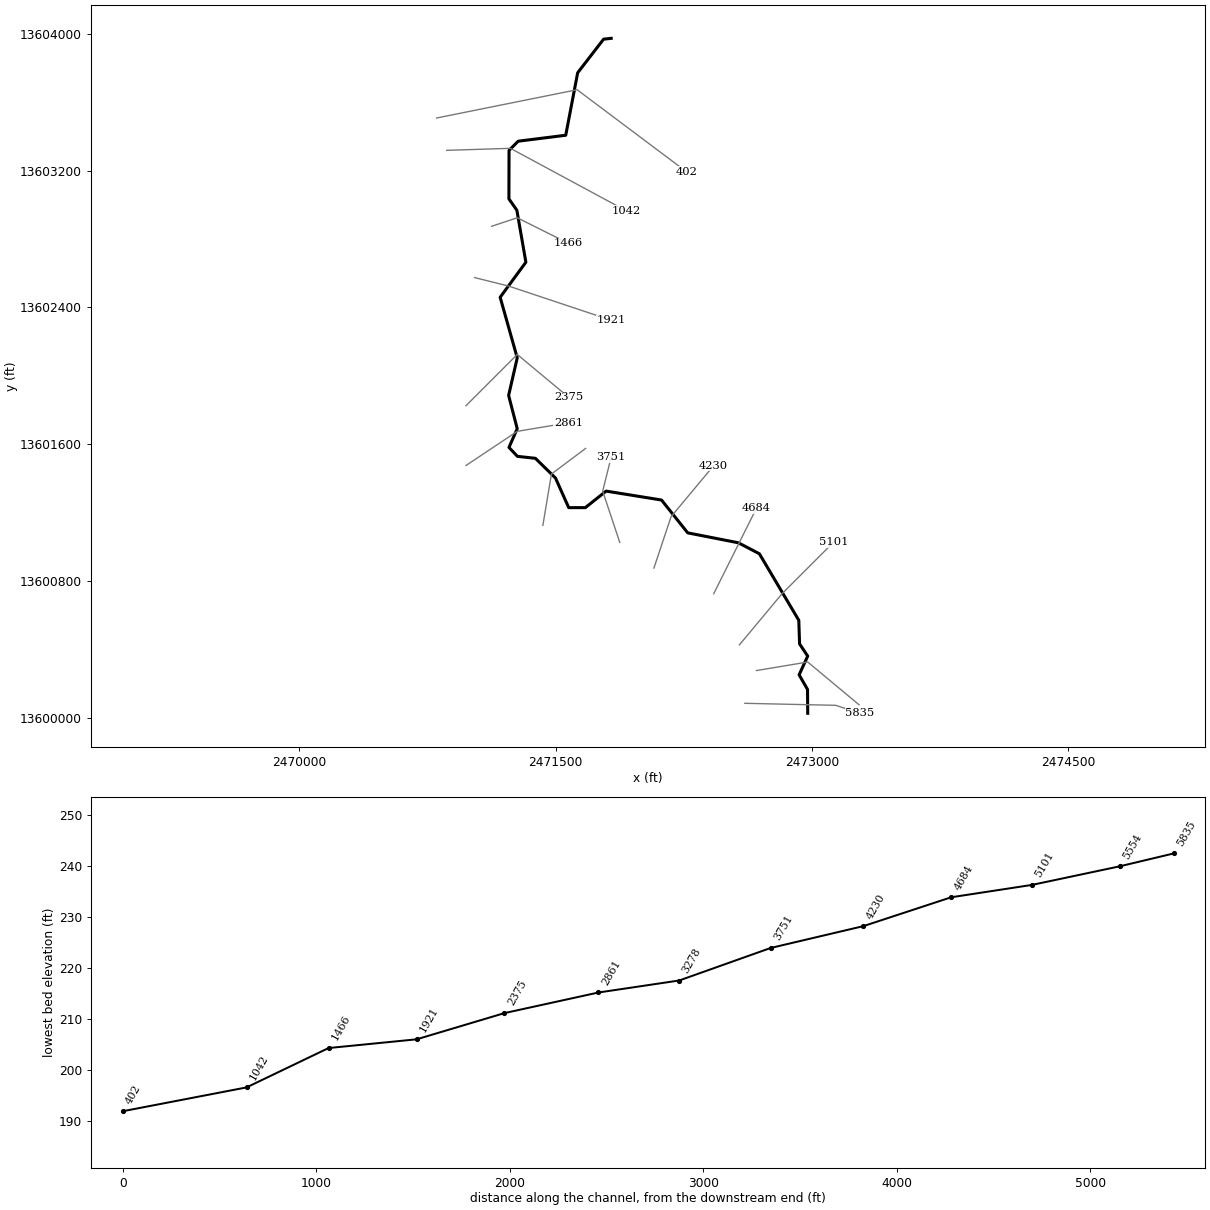
--- Stream0826.prj (project) ---

Proj Title=Stream0826 Base Level Engineering
Current Plan=p01
Default Exp/Contr=0.3,0.1
English Units
Geom File=g01
Flow File=f01
Plan File=p01
BEGIN DESCRIPTION:
Stream0826
END DESCRIPTION:

--- Stream0826.p01 (plan) ---

Plan Title=Multiple Run
Short Identifier=Multiple
Geom File=g01
Flow File=f01
Subcritical Flow
K Sum by GR= 0
Std Step Tol= 0.01
Critical Tol= 0.01
Num of Std Step Trials= 20
Max Error Tol= 0.3
Flow Tol Ratio= 0.001
Split Flow NTrial= 30
Split Flow Tol= 0.02
Split Flow Ratio= 0.02
Log Output Level= 0
Friction Slope Method= 1
Unsteady Friction Slope Method= 2
Unsteady Bridges Friction Slope Method= 1
Parabolic Critical Depth
Global Vel Dist=  1 , 1 , 1
Global Log Level= 0
CheckData=True
Encroach Param= -1, 0, 0, 0
BEGIN DESCRIPTION:
Multiple Run
END DESCRIPTION:

--- Stream0826.f01 (steady flow) ---

Flow Title=Multiple
Number of Profiles=7
Profile Names=10-year,25-year,50-year,1pct_min,100-year,1pct_plu,500-year
River Rch & RM= Stream0826,Reach-1,5835
     548     882    1183     770    1537    3066    2565
Boundary for River Rch & Prof#=Stream0826,Reach-1,1
Up Type=0
Dn Type=3
Dn Slope=0.005
Boundary for River Rch & Prof#=Stream0826,Reach-1,2
Up Type=0
Dn Type=3
Dn Slope=0.005
Boundary for River Rch & Prof#=Stream0826,Reach-1,3
Up Type=0
Dn Type=3
Dn Slope=0.005
Boundary for River Rch & Prof#=Stream0826,Reach-1,4
Up Type=0
Dn Type=3
Dn Slope=0.005
Boundary for River Rch & Prof#=Stream0826,Reach-1,5
Up Type=0
Dn Type=3
Dn Slope=0.005
Boundary for River Rch & Prof#=Stream0826,Reach-1,6
Up Type=0
Dn Type=3
Dn Slope=0.005
Boundary for River Rch & Prof#=Stream0826,Reach-1,7
Up Type=0
Dn Type=3
Dn Slope=0.005

--- Stream0826.g01 (geometry) ---

Geom Title=Existing Conditions

River Reach=Stream0826,Reach-1
Reach XY= 30
      2472975.00     13600025.00      2472973.81     13600164.52
      2472924.61     13600250.00      2472974.90     13600359.60
      2472927.30     13600430.93      2472922.75     13600569.07
      2472692.05     13600958.51      2472569.07     13601022.76
      2472272.69     13601080.82      2472119.33     13601273.02
      2471795.05     13601325.21      2471673.49     13601228.47
      2471576.25     13601228.36      2471498.82     13601401.87
      2471381.17     13601517.14      2471276.22     13601528.53
      2471226.54     13601580.83      2471274.89     13601690.39
      2471224.50     13601885.17      2471274.95     13602104.96
      2471174.95     13602459.66      2471325.55     13602664.81
      2471272.73     13602969.06      2471226.22     13603035.50
      2471226.97     13603319.35      2471280.65     13603373.03
      2471558.76     13603407.77      2471628.61     13603773.50
      2471780.33     13603970.08      2471825.00     13603975.00

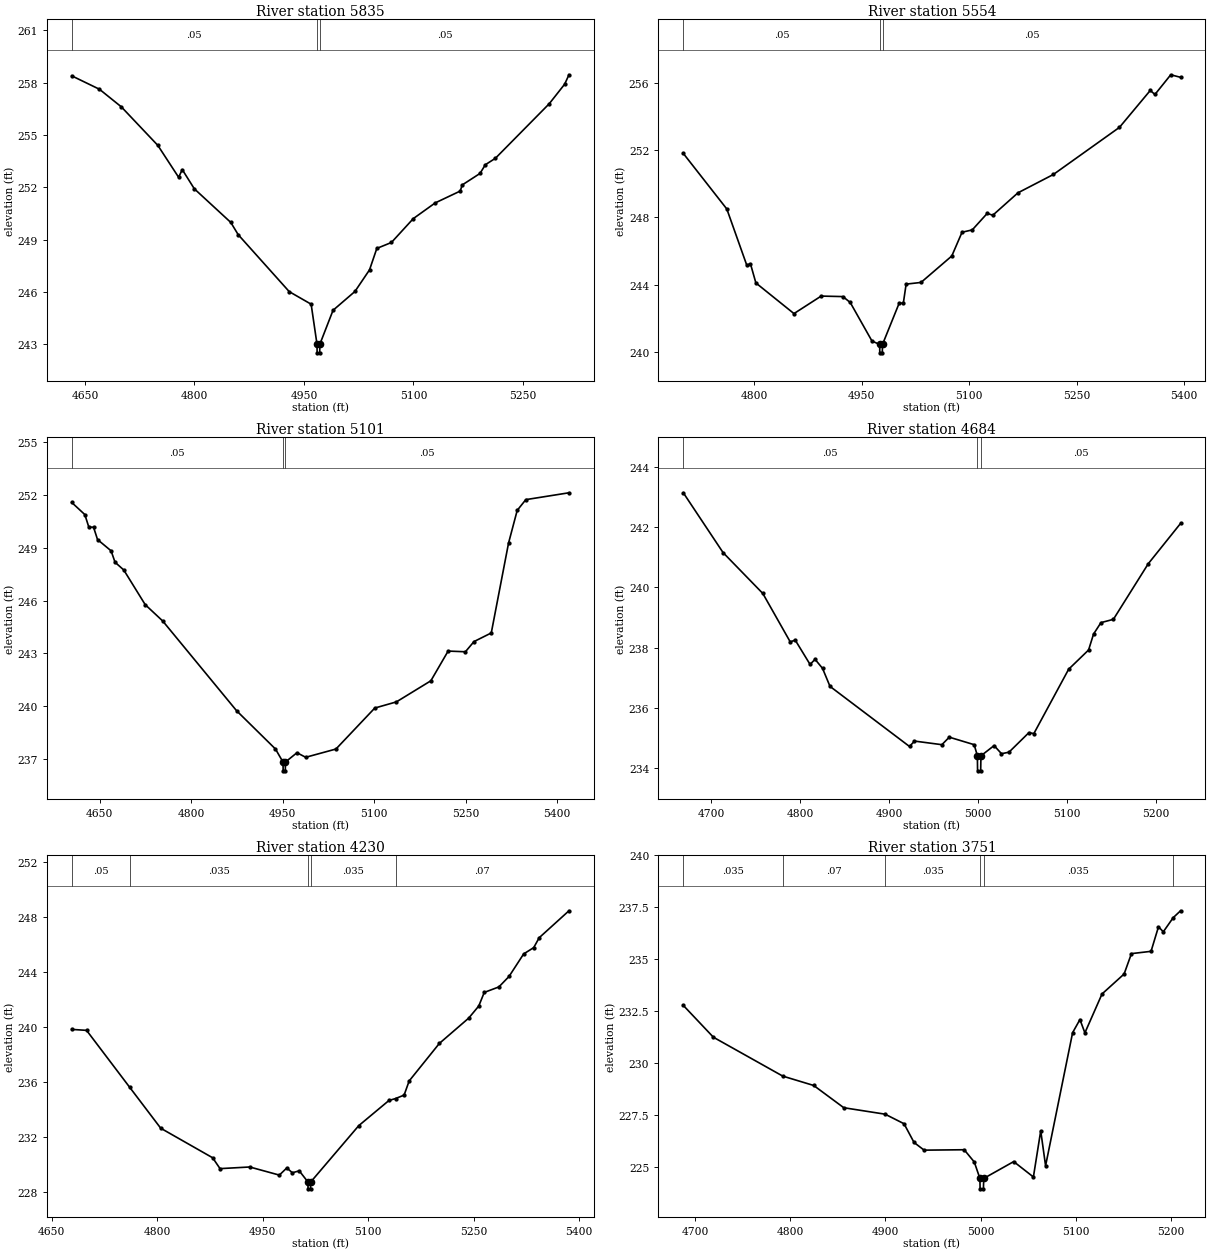
Type RM Length L Ch R = 1,5835,281,281,281
BEGIN DESCRIPTION:
XS7790
END DESCRIPTION:
XS GIS Cut Line= 3
      2472607.01     13600083.33      2473139.25     13600071.51
      2473280.63     13600024.38
#Sta/Elev= 30
  4631.8  258.39  4669.8  257.62  4699.8  256.61  4749.8  254.40  4778.3  252.57
  4783.3  253.01  4799.8  251.91  4849.8  249.98  4859.9  249.28  4929.9  246.01
  4959.9  245.29  4967.9  243.00  4968.1  242.50  4971.6  242.50  4971.9  243.00
  4989.9  244.94  5019.9  246.02  5039.9  247.26  5049.9  248.49  5069.9  248.83
  5099.9  250.20  5129.9  251.10  5164.2  251.78  5166.9  252.13  5191.3  252.79
  5198.6  253.29  5212.4  253.66  5286.2  256.79  5307.3  257.91  5313.2  258.45
#Mann=3,-1,0
  4631.8    0.05       0  4967.9    0.05       0  4971.9    0.05       0
Bank Sta=4967.9,4971.9
Exp/Cntr=0.3,0.1

Type RM Length L Ch R = 1,5554,453,453,453
BEGIN DESCRIPTION:
Stream0826 12.0
END DESCRIPTION:
XS GIS Cut Line= 3
      2472674.99     13600275.00      2472975.00     13600325.00
      2473275.03     13600074.98
#Sta/Elev= 30
  4700.6  251.80  4761.4  248.50  4789.3  245.16  4794.4  245.25  4802.0  244.11
  4855.2  242.29  4893.2  243.33  4923.6  243.30  4933.8  242.95  4964.2  240.66
  4974.9  240.46  4975.1  239.96  4978.6  239.96  4978.9  240.46  5002.2  242.91
  5008.0  242.91  5011.9  244.04  5032.7  244.14  5075.7  245.71  5090.0  247.12
  5104.3  247.26  5125.2  248.24  5133.0  248.13  5168.1  249.46  5217.6  250.55
  5310.0  253.35  5353.0  255.54  5359.5  255.30  5381.6  256.47  5395.3  256.32
#Mann=3,-1,0
  4700.6    0.05       0  4974.9    0.05       0  4978.9    0.05       0
Bank Sta=4974.9,4978.9
Exp/Cntr=0.3,0.1

Type RM Length L Ch R = 1,5101,417,417,417
BEGIN DESCRIPTION:
Stream0826 11.0
END DESCRIPTION:
XS GIS Cut Line= 3
      2472574.98     13600424.97      2472825.00     13600725.00
      2473124.99     13601024.99
#Sta/Elev= 30
  4604.4  251.58  4625.9  250.89  4632.4  250.18  4640.2  250.17  4646.7  249.47
  4668.9  248.83  4675.4  248.18  4689.7  247.74  4724.8  245.77  4753.5  244.84
  4874.5  239.74  4938.3  237.56  4950.6  236.82  4950.9  236.32  4954.4  236.32
  4954.6  236.82  4973.5  237.35  4987.8  237.09  5037.4  237.56  5101.0  239.89
  5136.4  240.24  5192.9  241.44  5221.2  243.13  5249.5  243.09  5263.6  243.67
  5291.9  244.16  5320.2  249.27  5334.4  251.13  5348.5  251.74  5419.2  252.13
#Mann=3,-1,0
  4604.4    0.05       0  4950.6    0.05       0  4954.6    0.05       0
Bank Sta=4950.6,4954.6
Exp/Cntr=0.3,0.1

Type RM Length L Ch R = 1,4684,454,454,454
BEGIN DESCRIPTION:
Stream0826 10.0
END DESCRIPTION:
XS GIS Cut Line= 3
      2472425.01     13600725.02      2472575.00     13601025.00
      2472675.00     13601225.01
#Sta/Elev= 30
  4668.7  243.15  4713.4  241.16  4758.1  239.80  4788.9  238.19  4794.5  238.25
  4811.2  237.44  4816.8  237.61  4825.2  237.31  4833.6  236.71  4923.0  234.71
  4928.6  234.89  4959.4  234.77  4967.7  235.02  4995.7  234.77  4999.3  234.40
  4999.5  233.90  5003.0  233.90  5003.3  234.40  5018.1  234.74  5026.4  234.47
  5034.8  234.52  5057.2  235.17  5062.8  235.14  5101.9  237.28  5124.3  237.92
  5129.9  238.45  5138.2  238.83  5152.2  238.94  5191.4  240.79  5227.7  242.13
#Mann=3,-1,0
  4668.7    0.05       0  4999.3    0.05       0  5003.3    0.05       0
Bank Sta=4999.3,5003.3
Exp/Cntr=0.3,0.1

Type RM Length L Ch R = 1,4230,479,479,479
BEGIN DESCRIPTION:
Stream0826 9.0
END DESCRIPTION:
XS GIS Cut Line= 3
      2472075.00     13600875.01      2472175.00     13601175.00
      2472424.98     13601474.98
#Sta/Elev= 30
  4678.7  239.84  4699.8  239.77  4761.2  235.62  4805.2  232.65  4879.0  230.50
  4889.5  229.71  4931.7  229.83  4973.8  229.24  4984.4  229.76  4992.3  229.41
  5002.1  229.55  5014.4  228.74  5014.6  228.24  5018.1  228.24  5018.4  228.74
  5086.7  232.84  5129.6  234.67  5139.0  234.81  5151.1  235.06  5158.3  236.09
  5201.2  238.82  5242.9  240.66  5257.2  241.54  5265.0  242.53  5285.8  242.93
  5300.2  243.69  5321.0  245.33  5335.3  245.79  5343.1  246.51  5385.4  248.47
#Mann=5,-1,0
  4678.7    0.05       0  4761.2   0.035       0  5014.4   0.035       0
  5018.4   0.035       0  5139.0    0.07       0
Bank Sta=5014.4,5018.4
Exp/Cntr=0.3,0.1

Type RM Length L Ch R = 1,3751,473,473,473
BEGIN DESCRIPTION:
Stream0826 8.0
END DESCRIPTION:
XS GIS Cut Line= 3
      2471875.00     13601025.01      2471775.00     13601325.00
      2471825.01     13601525.03
#Sta/Elev= 30
  4687.6  232.78  4719.2  231.25  4792.1  229.38  4824.6  228.93  4856.2  227.86
  4899.6  227.55  4919.5  227.09  4930.0  226.19  4940.6  225.82  4982.7  225.84
  4993.3  225.25  4999.2  224.46  4999.4  223.96  5002.9  223.96  5003.2  224.46
  5034.7  225.27  5055.4  224.53  5063.1  226.75  5068.2  225.07  5096.6  231.47
  5104.3  232.10  5109.5  231.46  5127.5  233.33  5150.7  234.29  5158.4  235.27
  5179.0  235.38  5186.8  236.56  5191.9  236.32  5202.3  237.00  5210.0  237.33
#Mann=6,-1,0
  4687.6   0.035       0  4792.1    0.07       0  4899.6   0.035       0
  4999.2   0.035       0  5003.2   0.035       0  5202.3    0.07       0
Bank Sta=4999.2,5003.2
Exp/Cntr=0.3,0.1

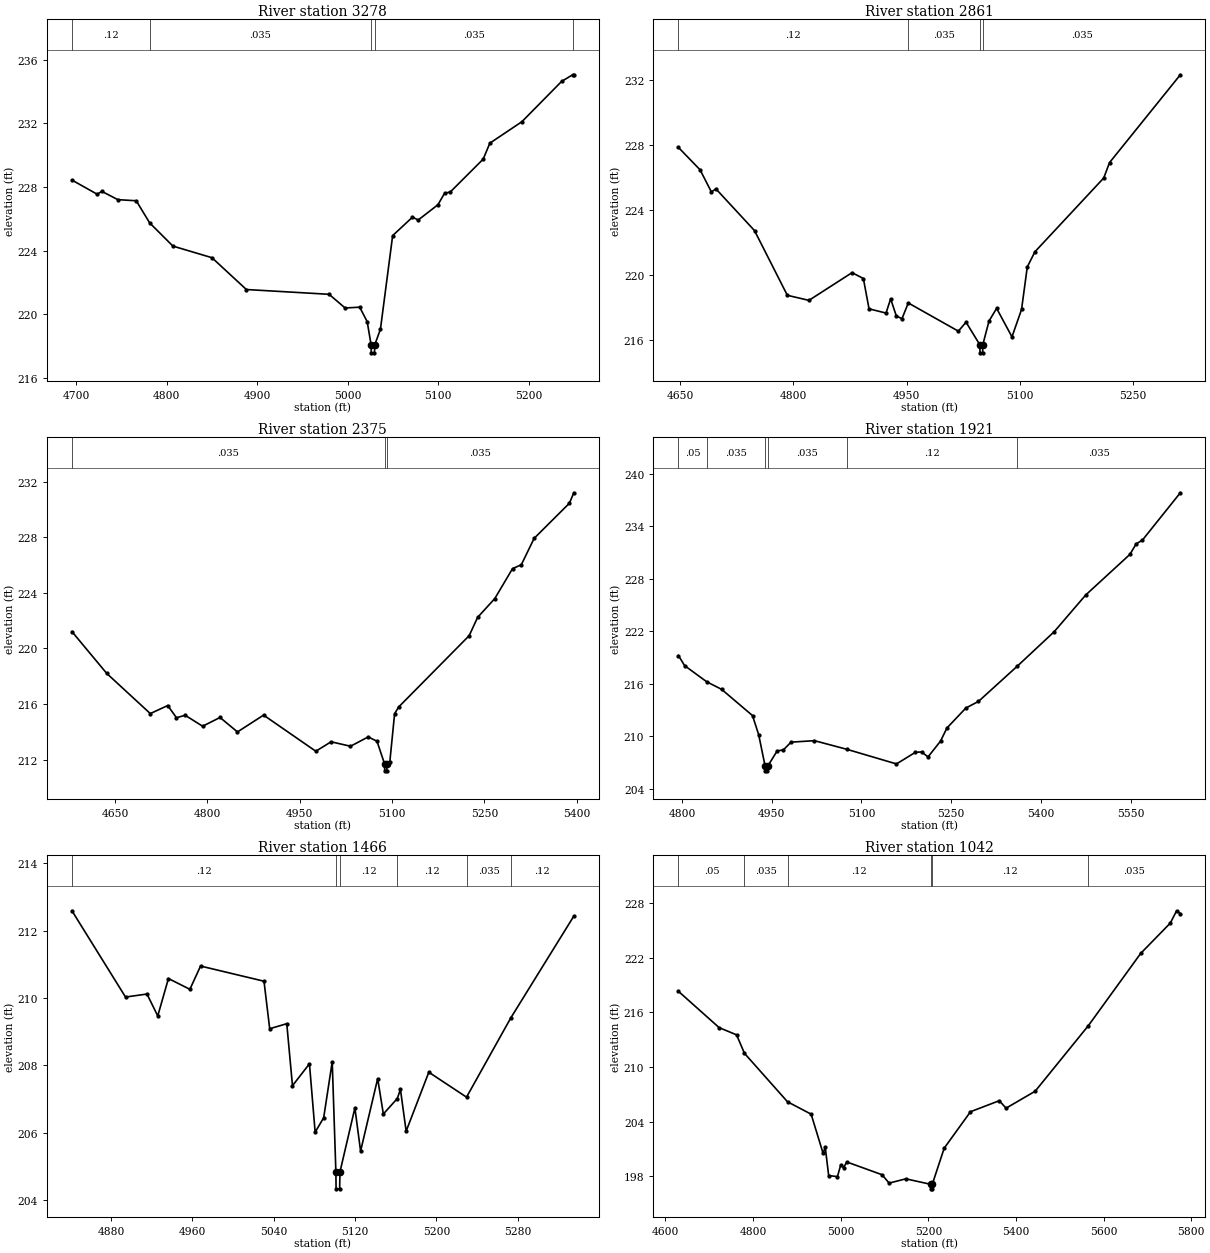
Type RM Length L Ch R = 1,3278,417,417,417
BEGIN DESCRIPTION:
Stream0826 7.0
END DESCRIPTION:
XS GIS Cut Line= 3
      2471425.00     13601125.00      2471475.00     13601425.00
      2471674.97     13601574.98
#Sta/Elev= 30
  4695.6  228.44  4723.5  227.55  4728.6  227.73  4746.3  227.21  4766.6  227.14
  4781.4  225.75  4807.1  224.29  4850.2  223.56  4888.2  221.56  4979.5  221.26
  4997.2  220.40  5013.3  220.45  5021.6  219.54  5025.9  218.08  5026.1  217.58
  5029.6  217.58  5029.9  218.08  5036.2  219.06  5049.7  224.95  5071.6  226.11
  5077.9  225.93  5099.7  226.89  5107.0  227.61  5113.3  227.69  5149.7  229.76
  5157.0  230.76  5192.4  232.11  5236.2  234.64  5248.4  235.06  5249.7  235.06
#Mann=5,-1,0
  4695.6    0.12       0  4781.4   0.035       0  5025.9   0.035       0
  5029.9   0.035       0  5248.4    0.07       0
Bank Sta=5025.9,5029.9
Exp/Cntr=0.3,0.1

Type RM Length L Ch R = 1,2861,486,486,486
BEGIN DESCRIPTION:
Stream0826 6.0
END DESCRIPTION:
XS GIS Cut Line= 3
      2470974.98     13601474.99      2471275.00     13601675.00
      2471574.99     13601725.00
#Sta/Elev= 30
  4647.9  227.83  4676.5  226.46  4691.5  225.10  4697.5  225.29  4748.6  222.73
  4792.1  218.76  4820.7  218.45  4877.8  220.15  4892.8  219.79  4900.3  217.93
  4922.8  217.67  4928.9  218.54  4936.4  217.50  4943.9  217.32  4952.3  218.29
  5018.6  216.56  5028.8  217.11  5047.0  215.73  5047.3  215.23  5050.8  215.23
  5051.0  215.73  5059.2  217.18  5069.3  217.96  5089.6  216.21  5102.3  217.89
  5109.9  220.50  5120.0  221.43  5211.2  225.96  5218.8  226.90  5312.6  232.29
#Mann=4,-1,0
  4647.9    0.12       0  4952.3   0.035       0  5047.0   0.035       0
  5051.0   0.035       0
Bank Sta=5047,5051
Exp/Cntr=0.3,0.1

Type RM Length L Ch R = 1,2375,454,454,454
BEGIN DESCRIPTION:
Stream0826 5.0
END DESCRIPTION:
XS GIS Cut Line= 3
      2470975.02     13601825.02      2471275.00     13602125.00
      2471574.97     13601875.03
#Sta/Elev= 30
  4580.3  221.21  4636.8  218.20  4707.5  215.31  4735.8  215.89  4750.0  215.01
  4764.1  215.19  4792.4  214.40  4820.7  215.03  4849.0  213.99  4891.4  215.20
  4976.2  212.60  5001.0  213.28  5032.5  212.96  5061.2  213.63  5075.5  213.32
  5087.8  211.69  5088.0  211.19  5091.5  211.19  5091.8  211.69  5096.3  211.82
  5104.1  215.30  5110.6  215.78  5225.2  220.92  5238.8  222.23  5266.8  223.59
  5295.5  225.74  5309.8  226.02  5330.6  227.92  5387.9  230.45  5395.0  231.20
#Mann=3,-1,0
  4580.3   0.035       0  5087.8   0.035       0  5091.8   0.035       0
Bank Sta=5087.8,5091.8
Exp/Cntr=0.3,0.1

Type RM Length L Ch R = 1,1921,455,455,455
BEGIN DESCRIPTION:
Stream0826 4.0
END DESCRIPTION:
XS GIS Cut Line= 3
      2471025.02     13602575.00      2471225.00     13602525.00
      2471825.01     13602325.00
#Sta/Elev= 30
  4794.2  219.23  4804.5  218.08  4841.5  216.23  4866.3  215.37  4917.9  212.37
  4928.2  210.19  4939.1  206.55  4939.3  206.05  4942.8  206.05  4943.1  206.55
  4959.1  208.33  4969.4  208.44  4982.3  209.33  5021.4  209.50  5075.7  208.51
  5158.5  206.84  5190.1  208.17  5200.6  208.21  5211.2  207.64  5232.2  209.46
  5242.8  210.95  5274.4  213.23  5295.5  213.99  5359.9  217.99  5422.0  221.96
  5474.7  226.16  5548.5  230.80  5559.0  232.00  5569.5  232.44  5632.8  237.85
#Mann=6,-1,0
  4794.2    0.05       0  4841.5   0.035       0  4939.1   0.035       0
  4943.1   0.035       0  5075.7    0.12       0  5359.9   0.035       0
Bank Sta=4939.1,4943.1
Exp/Cntr=0.3,0.1

Type RM Length L Ch R = 1,1466,424,424,424
BEGIN DESCRIPTION:
Stream0826 3.0
END DESCRIPTION:
XS GIS Cut Line= 3
      2471124.96     13602874.99      2471275.00     13602925.00
      2471575.03     13602774.98
#Sta/Elev= 30
  4841.5  212.59  4894.2  210.03  4915.3  210.12  4925.9  209.47  4936.4  210.58
  4957.5  210.26  4968.0  210.95  5030.4  210.50  5036.0  209.09  5052.8  209.24
  5058.4  207.40  5075.1  208.05  5080.7  206.02  5089.1  206.45  5097.5  208.11
  5101.1  204.84  5101.3  204.34  5104.8  204.34  5105.1  204.84  5119.8  206.74
  5125.4  205.46  5142.2  207.61  5147.8  206.56  5161.5  207.02  5164.6  207.29
  5170.2  206.05  5192.5  207.80  5229.6  207.06  5273.1  209.41  5335.1  212.43
#Mann=6,-1,0
  4841.5    0.12       0  5101.1    0.05       0  5105.1    0.12       0
  5161.5    0.12       0  5229.6   0.035       0  5273.1    0.12       0
Bank Sta=5101.1,5105.1
Exp/Cntr=0.3,0.1

Type RM Length L Ch R = 1,1042,640,640,640
BEGIN DESCRIPTION:
Stream0826 2.0
END DESCRIPTION:
XS GIS Cut Line= 3
      2470862.37     13603319.46      2471234.95     13603331.29
      2471915.04     13602964.63
#Sta/Elev= 30
  4629.7  218.31  4722.4  214.33  4762.4  213.53  4780.2  211.51  4878.6  206.18
  4932.5  204.82  4959.7  200.53  4964.7  201.18  4972.5  198.08  4992.5  197.96
  5000.0  199.24  5006.7  198.96  5013.9  199.57  5094.3  198.17  5110.5  197.25
  5148.6  197.72  5205.0  197.12  5205.3  196.62  5208.8  196.62  5209.0  197.12
  5236.2  201.09  5296.2  205.09  5361.9  206.30  5377.4  205.48  5443.8  207.34
  5565.0  214.53  5684.7  222.48  5752.3  225.81  5766.6  227.16  5775.1  226.85
#Mann=6,-1,0
  4629.7    0.05       0  4780.2   0.035       0  4878.6    0.12       0
  5205.0    0.05       0  5209.0    0.12       0  5565.0   0.035       0
Bank Sta=5205,5209
Exp/Cntr=0.3,0.1

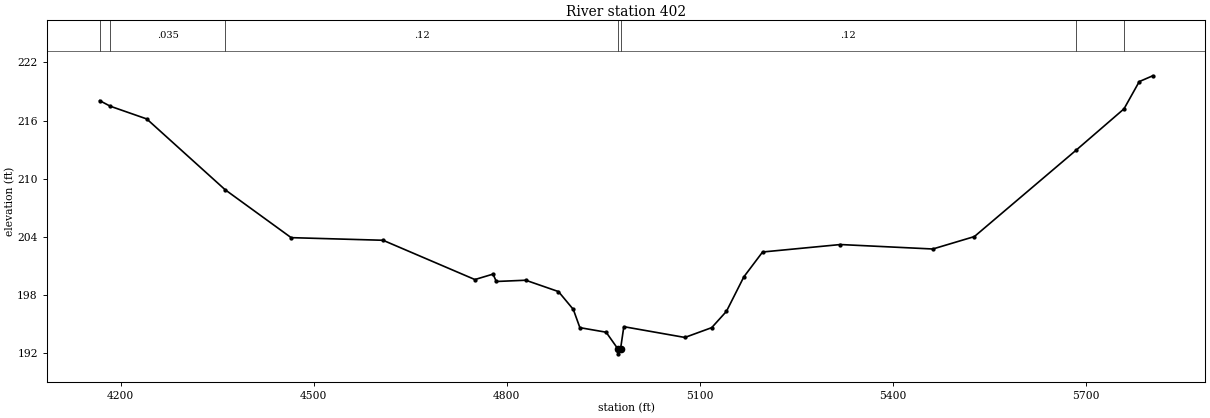
Type RM Length L Ch R = 1,402,0,0,0
BEGIN DESCRIPTION:
Stream0826 1.0
END DESCRIPTION:
XS GIS Cut Line= 3
      2470803.20     13603508.70      2471625.27     13603674.30
      2472264.00     13603195.25
#Sta/Elev= 30
  4167.4  218.06  4184.0  217.48  4240.6  216.17  4362.5  208.87  4465.1  203.93
  4607.9  203.66  4750.7  199.61  4778.9  200.17  4784.0  199.41  4829.7  199.54
  4880.6  198.37  4903.7  196.53  4913.9  194.65  4954.7  194.18  4973.1  192.45
  4973.4  191.95  4977.1  192.45  4982.2  194.75  5077.1  193.64  5118.8  194.65
  5141.7  196.33  5168.8  199.89  5197.9  202.45  5318.8  203.22  5462.5  202.76
  5527.1  204.04  5685.3  212.95  5759.7  217.21  5783.4  220.02  5804.4  220.62
#Mann=7,-1,0
  4167.4    0.05       0  4184.0   0.035       0  4362.5    0.12       0
  4973.1    0.05       0  4977.1    0.12       0  5685.3   0.035       0
  5759.7    0.12       0
Bank Sta=4973.1,4977.1
Exp/Cntr=0.3,0.1

Chan Stop Cuts=-1