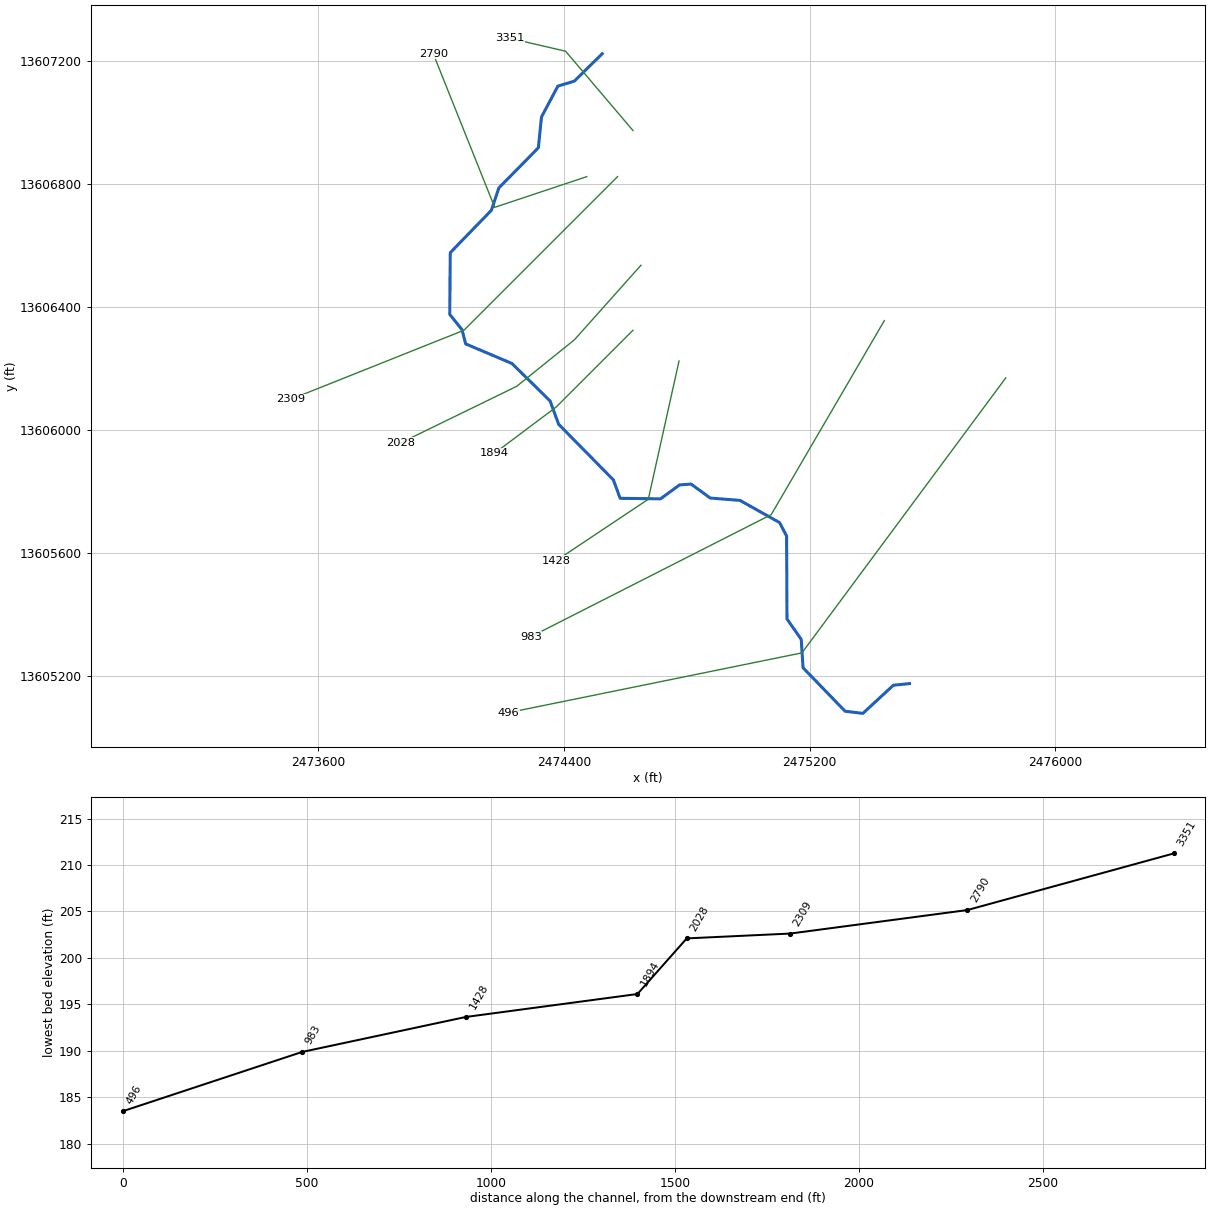
--- Stream0827.prj (project) ---

Proj Title=Stream0827 Base Level Engineering
Current Plan=p01
Default Exp/Contr=0.3,0.1
English Units
Geom File=g01
Flow File=f01
Plan File=p01
BEGIN DESCRIPTION:
Stream0827
END DESCRIPTION:

--- Stream0827.p01 (plan) ---

Plan Title=Multiple Run
Short Identifier=Multiple
Geom File=g01
Flow File=f01
Subcritical Flow
K Sum by GR= 0
Std Step Tol= 0.01
Critical Tol= 0.01
Num of Std Step Trials= 20
Max Error Tol= 0.3
Flow Tol Ratio= 0.001
Split Flow NTrial= 30
Split Flow Tol= 0.02
Split Flow Ratio= 0.02
Log Output Level= 0
Friction Slope Method= 1
Unsteady Friction Slope Method= 2
Unsteady Bridges Friction Slope Method= 1
Parabolic Critical Depth
Global Vel Dist=  1 , 1 , 1
Global Log Level= 0
CheckData=True
Encroach Param= -1, 0, 0, 0
BEGIN DESCRIPTION:
Multiple Run
END DESCRIPTION:

--- Stream0827.f01 (steady flow) ---

Flow Title=Multiple
Number of Profiles=7
Profile Names=10-year,25-year,50-year,1pct_min,100-year,1pct_plu,500-year
River Rch & RM= Stream0827,Reach-1,3351
     517     825    1101     713    1422    2838    2349
Boundary for River Rch & Prof#=Stream0827,Reach-1,1
Up Type=0
Dn Type=3
Dn Slope=0.005
Boundary for River Rch & Prof#=Stream0827,Reach-1,2
Up Type=0
Dn Type=3
Dn Slope=0.005
Boundary for River Rch & Prof#=Stream0827,Reach-1,3
Up Type=0
Dn Type=3
Dn Slope=0.005
Boundary for River Rch & Prof#=Stream0827,Reach-1,4
Up Type=0
Dn Type=3
Dn Slope=0.005
Boundary for River Rch & Prof#=Stream0827,Reach-1,5
Up Type=0
Dn Type=3
Dn Slope=0.005
Boundary for River Rch & Prof#=Stream0827,Reach-1,6
Up Type=0
Dn Type=3
Dn Slope=0.005
Boundary for River Rch & Prof#=Stream0827,Reach-1,7
Up Type=0
Dn Type=3
Dn Slope=0.005

--- Stream0827.g01 (geometry) ---

Geom Title=Existing Conditions

River Reach=Stream0827,Reach-1
Reach XY= 30
      2474525.00     13607225.00      2474434.42     13607135.83
      2474380.58     13607119.41      2474327.32     13607019.06
      2474317.14     13606918.83      2474188.63     13606788.21
      2474164.22     13606715.32      2474030.46     13606577.45
      2474028.74     13606376.52      2474068.72     13606326.84
      2474080.58     13606280.58      2474231.05     13606216.86
      2474355.21     13606095.09      2474383.16     13606018.95
      2474561.26     13605837.95      2474583.31     13605778.06
      2474714.49     13605776.22      2474776.73     13605821.63
      2474814.31     13605824.23      2474876.58     13605778.89
      2474973.42     13605771.18      2475102.30     13605698.91
      2475125.09     13605655.12      2475126.22     13605385.50
      2475172.64     13605319.02      2475178.61     13605226.50
      2475315.32     13605085.17      2475373.35     13605078.09
      2475472.49     13605169.67      2475525.00     13605175.00

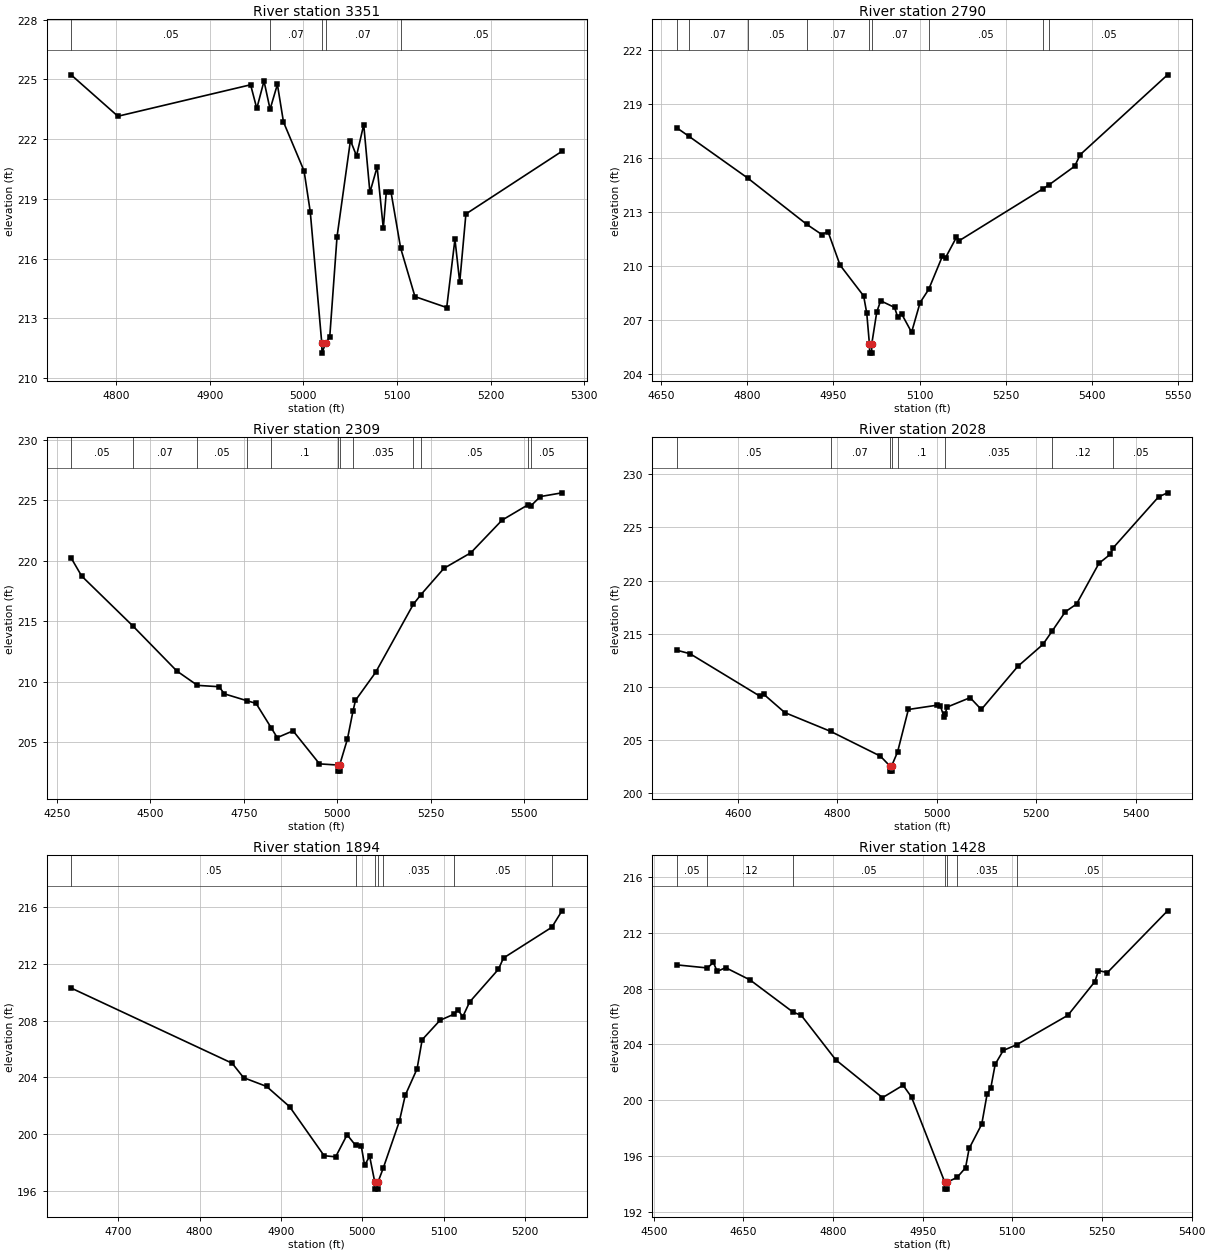
Type RM Length L Ch R = 1,3351,561,561,561
BEGIN DESCRIPTION:
Stream0827 7.0
END DESCRIPTION:
XS GIS Cut Line= 3
      2474625.02     13606974.97      2474405.82     13607233.07
      2474225.04     13607274.99
#Sta/Elev= 30
  4752.0  225.23  4802.0  223.15  4943.7  224.73  4950.3  223.54  4958.0  224.92
  4964.5  223.50  4972.3  224.75  4978.8  222.86  5000.8  220.40  5007.4  218.35
  5019.7  211.75  5019.9  211.25  5023.7  211.75  5028.2  212.06  5036.0  217.10
  5050.3  221.93  5056.8  221.16  5064.5  222.73  5071.1  219.32  5078.8  220.60
  5085.4  217.52  5088.6  219.35  5093.6  219.35  5103.9  216.53  5119.2  214.09
  5153.1  213.54  5161.9  216.97  5167.0  214.81  5173.6  218.24  5276.2  221.39
#Mann=5,-1,0
  4752.0    0.05       0  4964.5    0.07       0  5019.7    0.05       0
  5023.7    0.07       0  5103.9    0.05       0
Bank Sta=5019.7,5023.7
Exp/Cntr=0.3,0.1

Type RM Length L Ch R = 1,2790,481,481,481
BEGIN DESCRIPTION:
Stream0827 6.0
END DESCRIPTION:
XS GIS Cut Line= 3
      2474474.96     13606824.99      2474175.00     13606725.00
      2473975.00     13607225.00
#Sta/Elev= 30
  4677.1  217.68  4698.2  217.21  4800.9  214.88  4903.6  212.31  4930.0  211.74
  4940.6  211.91  4961.7  210.04  5002.7  208.33  5008.1  207.38  5012.8  205.65
  5013.1  205.15  5016.6  205.15  5016.8  205.65  5025.6  207.44  5032.3  208.06
  5056.6  207.69  5061.9  207.16  5068.7  207.34  5086.2  206.31  5101.0  207.96
  5115.9  208.69  5140.0  210.55  5145.4  210.46  5164.3  211.59  5169.6  211.41
  5314.7  214.28  5325.7  214.51  5370.2  215.54  5379.7  216.18  5531.8  220.62
#Mann=9,-1,0
  4677.1    0.05       0  4698.2    0.07       0  4800.9    0.05       0
  4903.6    0.07       0  5012.8    0.05       0  5016.8    0.07       0
  5115.9    0.05       0  5314.7    0.07       0  5325.7    0.05       0
Bank Sta=5012.8,5016.8
Exp/Cntr=0.3,0.1

Type RM Length L Ch R = 1,2309,281,281,281
BEGIN DESCRIPTION:
Stream0827 5.0
END DESCRIPTION:
XS GIS Cut Line= 3
      2474575.02     13606825.02      2474075.00     13606325.00
      2473511.71     13606100.26
#Sta/Elev= 30
  4288.0  220.25  4316.3  218.75  4453.4  214.62  4570.9  210.90  4626.2  209.71
  4684.0  209.60  4698.1  209.01  4757.7  208.45  4783.0  208.22  4823.1  206.22
  4839.6  205.39  4882.0  205.95  4952.7  203.22  5002.6  203.12  5002.8  202.62
  5006.3  202.62  5006.6  203.12  5027.4  205.26  5042.2  207.56  5049.0  208.47
  5102.8  210.78  5204.1  216.43  5224.4  217.22  5285.8  219.39  5357.6  220.67
  5441.2  223.37  5510.7  224.64  5518.3  224.55  5543.6  225.32  5601.6  225.63
#Mann=12,-1,0
  4288.0    0.05       0  4453.4    0.07       0  4626.2    0.05       0
  4757.7    0.07       0  4823.1     0.1       0  5002.6    0.05       0
  5006.6     0.1       0  5042.2   0.035       0  5204.1    0.12       0
  5224.4    0.05       0  5510.7    0.12       0  5518.3    0.05       0
Bank Sta=5002.6,5006.6
Exp/Cntr=0.3,0.1

Type RM Length L Ch R = 1,2028,134,134,134
BEGIN DESCRIPTION:
Stream0827 4.0a
END DESCRIPTION:
XS GIS Cut Line= 4
      2474651.01     13606536.43      2474434.51     13606293.90
      2474246.60     13606142.43      2473868.84     13605958.34
#Sta/Elev= 30
  4477.1  213.46  4503.9  213.13  4645.2  209.12  4652.7  209.30  4694.5  207.60
  4786.8  205.83  4886.6  203.51  4905.4  202.60  4905.6  202.10  4909.1  202.10
  4909.4  202.60  4921.2  203.90  4942.9  207.89  5000.1  208.29  5007.1  208.25
  5014.5  207.19  5016.7  207.50  5021.0  208.12  5067.0  209.00  5089.5  207.89
  5162.7  211.93  5213.3  214.00  5231.7  215.24  5258.4  217.07  5280.9  217.79
  5326.0  221.62  5348.6  222.46  5354.9  223.09  5445.8  227.86  5463.8  228.24
#Mann=8,-1,0
  4477.1    0.05       0  4786.8    0.07       0  4905.4    0.05       0
  4909.4    0.07       0  4921.2     0.1       0  5016.7   0.035       0
  5231.7    0.12       0  5354.9    0.05       0
Bank Sta=4905.4,4909.4
Exp/Cntr=0.3,0.1

Type RM Length L Ch R = 1,1894,466,466,466
BEGIN DESCRIPTION:
Stream0827 4.0
END DESCRIPTION:
XS GIS Cut Line= 3
      2474625.01     13606325.01      2474375.00     13606075.00
      2474174.98     13605924.98
#Sta/Elev= 30
  4641.9  210.31  4839.9  205.00  4854.0  203.98  4882.3  203.36  4910.6  201.93
  4953.0  198.47  4967.2  198.39  4981.3  199.95  4991.7  199.20  4998.6  199.19
  5002.8  197.79  5009.0  198.43  5015.3  196.61  5015.6  196.11  5019.1  196.11
  5019.3  196.61  5025.7  197.59  5045.5  200.89  5052.8  202.74  5067.3  204.60
  5073.6  206.66  5095.5  208.03  5112.6  208.46  5117.3  208.77  5123.6  208.29
  5131.9  209.32  5167.3  211.63  5173.6  212.43  5233.0  214.60  5245.5  215.76
#Mann=7,-1,0
  4641.9    0.05       0  4991.7    0.07       0  5015.3    0.05       0
  5019.3    0.07       0  5025.7   0.035       0  5112.6    0.05       0
  5233.0    0.07       0
Bank Sta=5015.3,5019.3
Exp/Cntr=0.3,0.1

Type RM Length L Ch R = 1,1428,445,445,445
BEGIN DESCRIPTION:
Stream0827 3.0
END DESCRIPTION:
XS GIS Cut Line= 3
      2474775.00     13606225.01      2474675.00     13605775.00
      2474375.03     13605575.02
#Sta/Elev= 30
  4538.1  209.70  4589.5  209.48  4599.6  209.87  4606.0  209.23  4620.1  209.50
  4661.0  208.62  4732.8  206.32  4746.8  206.08  4804.4  202.90  4882.6  200.19
  4917.1  201.08  4931.2  200.23  4986.8  194.14  4987.1  193.64  4990.6  193.64
  4990.8  194.14  5007.5  194.48  5021.6  195.17  5027.6  196.55  5048.7  198.29
  5057.7  200.45  5063.7  200.85  5071.2  202.58  5084.7  203.57  5107.6  203.99
  5192.9  206.09  5238.0  208.50  5244.0  209.29  5259.0  209.15  5359.6  213.57
#Mann=7,-1,0
  4538.1    0.05       0  4589.5    0.12       0  4732.8    0.05       0
  4986.8    0.05       0  4990.8    0.05       0  5007.5   0.035       0
  5107.6    0.05       0
Bank Sta=4986.8,4990.8
Exp/Cntr=0.3,0.1

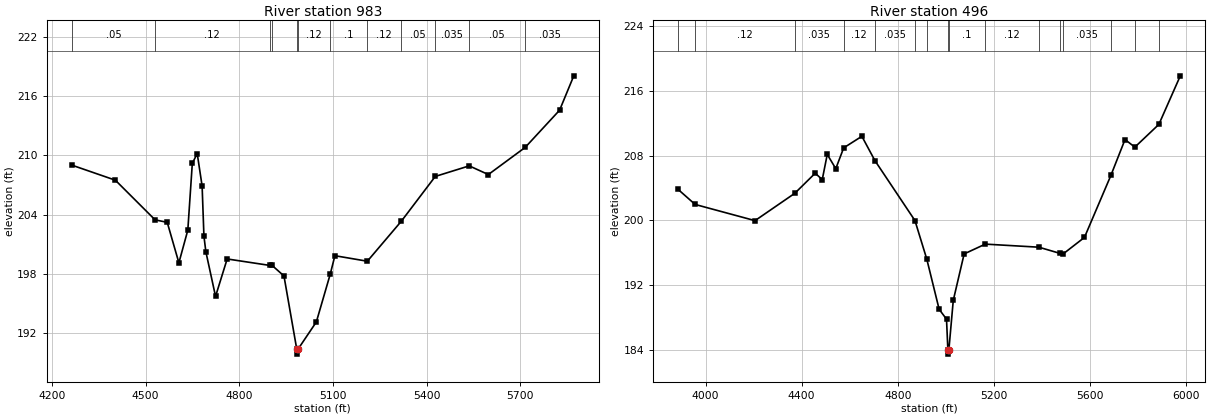
Type RM Length L Ch R = 1,983,487,487,487
BEGIN DESCRIPTION:
Stream0827 2.0
END DESCRIPTION:
XS GIS Cut Line= 3
      2475443.13     13606356.32      2475075.00     13605725.00
      2474292.95     13605327.68
#Sta/Elev= 30
  4263.4  209.02  4403.3  207.49  4530.6  203.47  4569.5  203.22  4606.8  199.12
  4635.4  202.43  4649.8  209.19  4665.5  210.19  4681.2  206.90  4687.0  201.83
  4693.2  200.24  4724.2  195.72  4761.4  199.51  4897.1  198.86  4905.5  198.85
  4943.3  197.79  4984.3  190.37  4984.6  189.87  4988.3  190.37  5047.0  193.13
  5091.5  197.97  5106.4  199.84  5210.3  199.28  5319.1  203.33  5427.9  207.87
  5536.6  208.94  5597.8  208.06  5715.8  210.81  5826.0  214.58  5871.4  218.06
#Mann=12,-1,0
  4263.4    0.05       0  4530.6    0.12       0  4897.1   0.035       0
  4905.5    0.12       0  4984.3    0.05       0  4988.3    0.12       0
  5091.5     0.1       0  5210.3    0.12       0  5319.1    0.05       0
  5427.9   0.035       0  5536.6    0.05       0  5715.8   0.035       0
Bank Sta=4984.3,4988.3
Exp/Cntr=0.3,0.1

Type RM Length L Ch R = 1,496,0,0,0
BEGIN DESCRIPTION:
Stream0827 1.0
END DESCRIPTION:
XS GIS Cut Line= 3
      2475838.12     13606169.72      2475175.00     13605275.00
      2474219.58     13605080.38
#Sta/Elev= 30
  3886.3  203.83  3956.9  201.98  4205.9  199.98  4371.5  203.36  4456.3  205.84
  4485.6  205.05  4506.4  208.16  4541.9  206.40  4574.7  208.97  4650.4  210.40
  4704.6  207.40  4871.2  199.99  4920.5  195.22  4971.8  189.03  5002.5  187.81
  5008.2  183.99  5008.4  183.49  5012.2  183.99  5030.6  190.13  5075.8  195.87
  5163.8  197.08  5386.6  196.70  5474.1  195.94  5486.4  195.84  5576.3  197.91
  5686.1  205.56  5745.0  210.00  5785.9  209.06  5885.8  211.87  5975.0  217.87
#Mann=16,-1,0
  3886.3    0.05       0  3956.9    0.12       0  4371.5   0.035       0
  4574.7    0.12       0  4704.6   0.035       0  4871.2    0.12       0
  4920.5     0.1       0  5008.2    0.05       0  5012.2     0.1       0
  5163.8    0.12       0  5386.6   0.035       0  5474.1    0.12       0
  5486.4   0.035       0  5686.1    0.05       0  5785.9   0.035       0
  5885.8    0.05       0
Bank Sta=5008.2,5012.2
Exp/Cntr=0.3,0.1

Chan Stop Cuts=-1