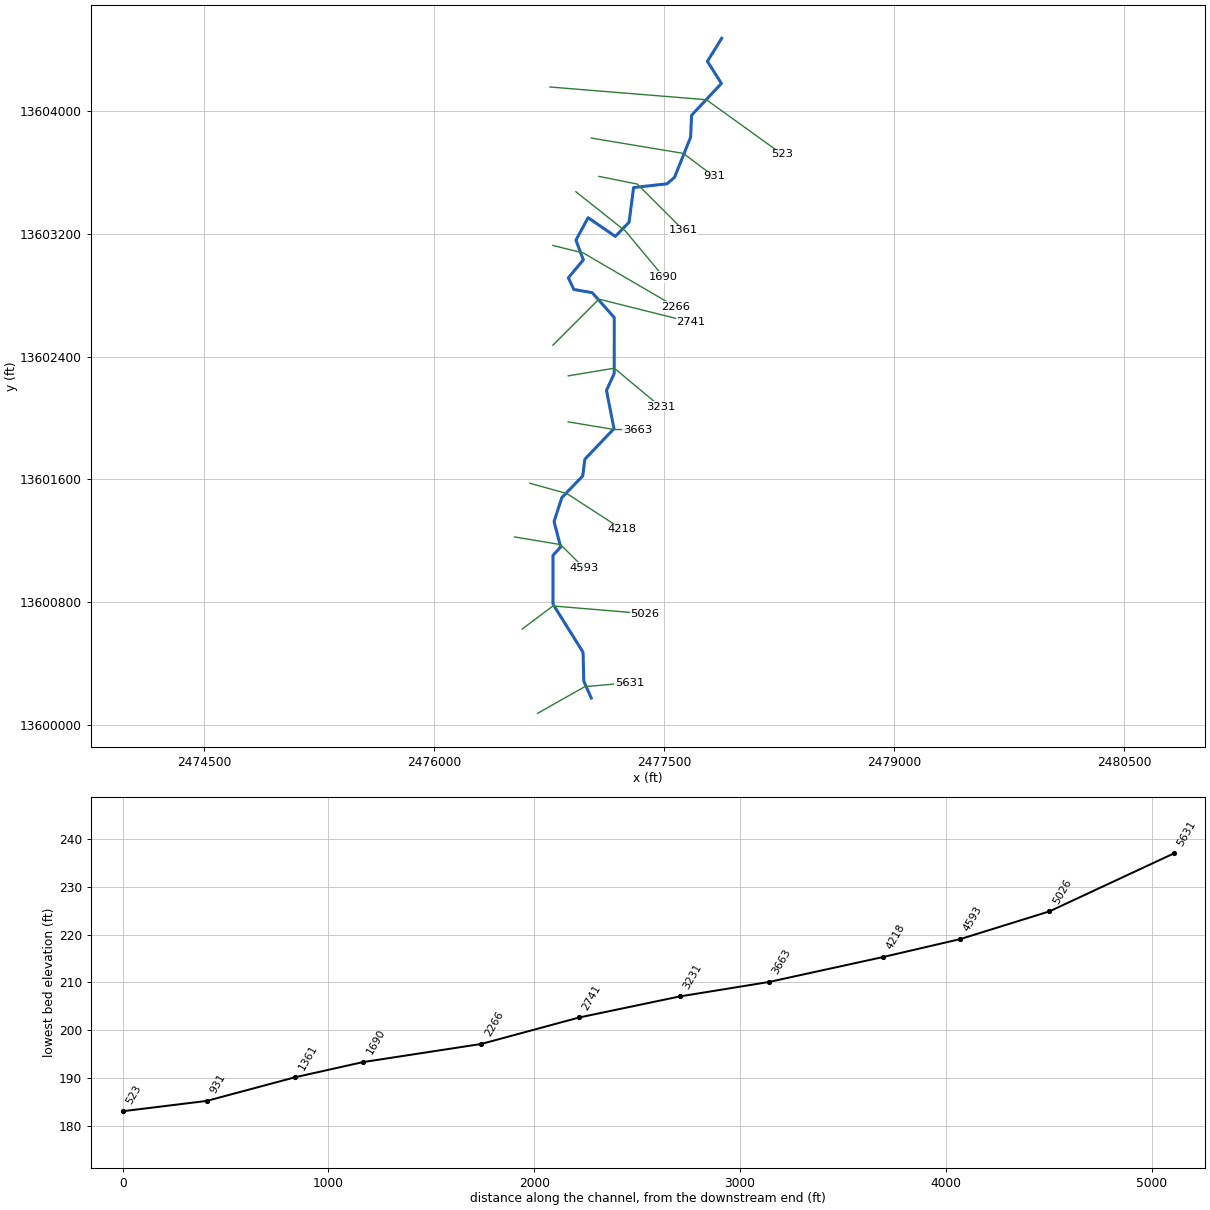
--- Stream0828.prj (project) ---

Proj Title=Stream0828 Base Level Engineering
Current Plan=p01
Default Exp/Contr=0.3,0.1
English Units
Geom File=g01
Flow File=f01
Plan File=p01
BEGIN DESCRIPTION:
Stream0828
END DESCRIPTION:

--- Stream0828.p01 (plan) ---

Plan Title=Multiple Run
Short Identifier=Multiple
Geom File=g01
Flow File=f01
Subcritical Flow
K Sum by GR= 0
Std Step Tol= 0.01
Critical Tol= 0.01
Num of Std Step Trials= 20
Max Error Tol= 0.3
Flow Tol Ratio= 0.001
Split Flow NTrial= 30
Split Flow Tol= 0.02
Split Flow Ratio= 0.02
Log Output Level= 0
Friction Slope Method= 1
Unsteady Friction Slope Method= 2
Unsteady Bridges Friction Slope Method= 1
Parabolic Critical Depth
Global Vel Dist=  1 , 1 , 1
Global Log Level= 0
CheckData=True
Encroach Param= -1, 0, 0, 0
BEGIN DESCRIPTION:
Multiple Run
END DESCRIPTION:

--- Stream0828.f01 (steady flow) ---

Flow Title=Multiple
Number of Profiles=7
Profile Names=10-year,25-year,50-year,1pct_min,100-year,1pct_plu,500-year
River Rch & RM= Stream0828,Reach-1,5631
     573     923    1239     807    1610    3212    2691
Boundary for River Rch & Prof#=Stream0828,Reach-1,1
Up Type=0
Dn Type=3
Dn Slope=0.005
Boundary for River Rch & Prof#=Stream0828,Reach-1,2
Up Type=0
Dn Type=3
Dn Slope=0.005
Boundary for River Rch & Prof#=Stream0828,Reach-1,3
Up Type=0
Dn Type=3
Dn Slope=0.005
Boundary for River Rch & Prof#=Stream0828,Reach-1,4
Up Type=0
Dn Type=3
Dn Slope=0.005
Boundary for River Rch & Prof#=Stream0828,Reach-1,5
Up Type=0
Dn Type=3
Dn Slope=0.005
Boundary for River Rch & Prof#=Stream0828,Reach-1,6
Up Type=0
Dn Type=3
Dn Slope=0.005
Boundary for River Rch & Prof#=Stream0828,Reach-1,7
Up Type=0
Dn Type=3
Dn Slope=0.005

--- Stream0828.g01 (geometry) ---

Geom Title=Existing Conditions

River Reach=Stream0828,Reach-1
Reach XY= 30
      2477025.00     13600175.00      2476976.12     13600285.46
      2476971.45     13600473.53      2476776.06     13600785.44
      2476775.30     13601104.70      2476825.53     13601159.53
      2476782.56     13601325.00      2476832.86     13601481.17
      2476969.48     13601622.57      2476982.88     13601731.17
      2477173.01     13601930.68      2477124.19     13602180.03
      2477174.48     13602290.22      2477175.04     13602655.02
      2477031.17     13602817.14      2476911.20     13602838.26
      2476875.54     13602914.31      2476973.37     13603031.04
      2476925.08     13603159.61      2477004.61     13603305.95
      2477181.69     13603183.95      2477271.46     13603276.44
      2477300.97     13603502.35      2477519.35     13603526.97
      2477567.28     13603568.50      2477672.75     13603830.93
      2477678.74     13603973.47      2477873.42     13604181.04
      2477782.07     13604325.00      2477875.00     13604475.00

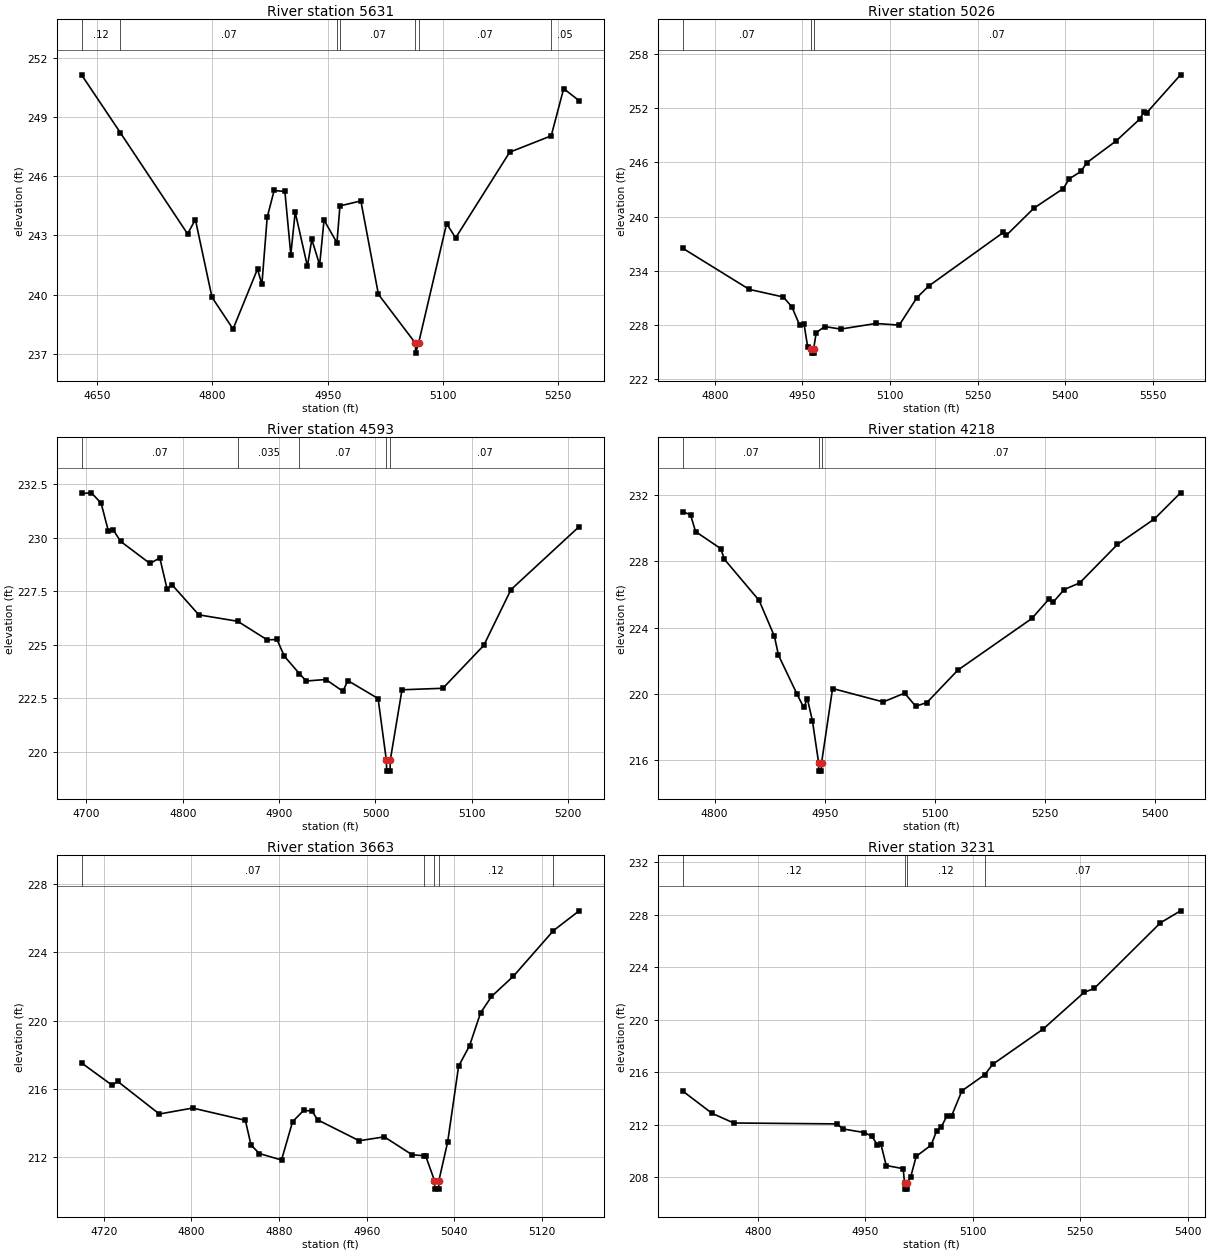
Type RM Length L Ch R = 1,5631,605,605,605
BEGIN DESCRIPTION:
Stream0828 12.0
END DESCRIPTION:
XS GIS Cut Line= 3
      2476674.97     13600074.98      2476982.06     13600248.88
      2477274.99     13600275.00
#Sta/Elev= 30
  4630.0  251.14  4680.4  248.21  4767.9  243.08  4778.0  243.81  4799.6  239.87
  4827.0  238.26  4858.8  241.30  4864.5  240.52  4871.4  243.92  4880.4  245.28
  4894.4  245.23  4902.1  242.03  4907.8  244.18  4923.7  241.44  4929.4  242.80
  4939.6  241.51  4945.3  243.78  4962.1  242.63  4966.0  244.50  4993.2  244.75
  5016.0  240.02  5064.2  237.54  5064.4  237.04  5068.2  237.54  5104.7  243.60
  5116.4  242.88  5186.7  247.22  5240.7  248.05  5256.9  250.44  5277.0  249.83
#Mann=7,-1,0
  4630.0    0.12       0  4680.4    0.07       0  4962.1    0.12       0
  4966.0    0.07       0  5064.2    0.05       0  5068.2    0.07       0
  5240.7    0.05       0
Bank Sta=5064.2,5068.2
Exp/Cntr=0.3,0.1

Type RM Length L Ch R = 1,5026,433,433,433
BEGIN DESCRIPTION:
Stream0828 11.0
END DESCRIPTION:
XS GIS Cut Line= 3
      2476574.98     13600624.98      2476775.00     13600775.00
      2477374.99     13600725.00
#Sta/Elev= 30
  4745.5  236.48  4859.1  231.94  4917.4  231.10  4932.0  230.01  4945.5  227.96
  4952.8  228.13  4959.1  225.57  4965.4  225.39  4965.7  224.89  4969.2  224.89
  4969.4  225.39  4973.7  227.15  4988.2  227.83  5015.6  227.55  5075.8  228.17
  5115.9  227.99  5146.1  231.02  5166.1  232.30  5294.1  238.24  5299.1  237.91
  5346.7  240.94  5396.9  243.10  5407.0  244.17  5427.0  244.99  5437.1  245.96
  5487.2  248.36  5527.4  250.76  5534.9  251.57  5539.9  251.50  5597.6  255.68
#Mann=3,-1,0
  4745.5    0.07       0  4965.4    0.05       0  4969.4    0.07       0
Bank Sta=4965.4,4969.4
Exp/Cntr=0.3,0.1

Type RM Length L Ch R = 1,4593,375,375,375
BEGIN DESCRIPTION:
Stream0828 10.0
END DESCRIPTION:
XS GIS Cut Line= 3
      2476524.95     13601225.01      2476825.00     13601175.00
      2476974.99     13601025.01
#Sta/Elev= 30
  4695.0  232.06  4705.2  232.09  4715.3  231.61  4722.9  230.29  4728.0  230.35
  4735.6  229.82  4766.0  228.79  4776.2  229.05  4783.8  227.59  4788.8  227.80
  4816.7  226.39  4857.0  226.09  4887.7  225.22  4897.8  225.24  4905.4  224.46
  4921.1  223.64  4928.2  223.30  4948.5  223.37  4966.2  222.82  4971.3  223.32
  5002.7  222.48  5011.3  219.59  5011.6  219.09  5015.1  219.09  5015.3  219.59
  5027.5  222.89  5069.9  222.96  5112.3  224.96  5140.6  227.57  5211.3  230.51
#Mann=5,-1,0
  4695.0    0.07       0  4857.0   0.035       0  4921.1    0.07       0
  5011.3    0.05       0  5015.3    0.07       0
Bank Sta=5011.3,5015.3
Exp/Cntr=0.3,0.1

Type RM Length L Ch R = 1,4218,555,555,555
BEGIN DESCRIPTION:
Stream0828 9.0
END DESCRIPTION:
XS GIS Cut Line= 3
      2476624.96     13601575.01      2476865.73     13601508.05
      2477224.96     13601275.02
#Sta/Elev= 30
  4756.8  231.01  4767.2  230.80  4774.0  229.80  4808.2  228.77  4813.4  228.12
  4860.6  225.64  4881.4  223.48  4887.0  222.33  4912.5  219.96  4921.3  219.18
  4926.4  219.69  4933.3  218.36  4941.7  215.83  4941.9  215.33  4945.4  215.33
  4945.7  215.83  4960.7  220.32  5029.7  219.51  5058.9  220.04  5074.0  219.25
  5089.2  219.47  5131.4  221.43  5232.3  224.55  5255.3  225.71  5261.2  225.53
  5276.4  226.30  5297.5  226.70  5348.9  229.02  5399.2  230.56  5434.9  232.14
#Mann=3,-1,0
  4756.8    0.07       0  4941.7    0.05       0  4945.7    0.07       0
Bank Sta=4941.7,4945.7
Exp/Cntr=0.3,0.1

Type RM Length L Ch R = 1,3663,432,432,432
BEGIN DESCRIPTION:
Stream0828 8.0
END DESCRIPTION:
XS GIS Cut Line= 3
      2476875.01     13601975.00      2477175.00     13601925.00
      2477324.97     13601925.00
#Sta/Elev= 30
  4699.7  217.51  4727.6  216.20  4732.6  216.43  4770.7  214.51  4801.1  214.86
  4849.2  214.14  4854.3  212.70  4861.9  212.19  4882.2  211.81  4892.3  214.06
  4902.5  214.73  4910.1  214.68  4915.1  214.17  4953.1  212.94  4976.0  213.17
  5001.3  212.12  5012.3  212.06  5013.8  212.04  5021.8  210.60  5022.1  210.10
  5025.6  210.10  5025.8  210.60  5033.8  212.86  5043.8  217.32  5053.8  218.52
  5063.8  220.44  5073.8  221.41  5093.8  222.60  5130.4  225.28  5153.8  226.44
#Mann=5,-1,0
  4699.7    0.07       0  5012.3    0.12       0  5021.8    0.05       0
  5025.8    0.12       0  5130.4    0.07       0
Bank Sta=5021.8,5025.8
Exp/Cntr=0.3,0.1

Type RM Length L Ch R = 1,3231,490,490,490
BEGIN DESCRIPTION:
Stream0828 7.0
END DESCRIPTION:
XS GIS Cut Line= 3
      2476875.04     13602275.01      2477175.00     13602325.00
      2477474.99     13602075.01
#Sta/Elev= 30
  4695.4  214.54  4735.9  212.86  4766.3  212.12  4910.8  212.05  4918.4  211.67
  4948.8  211.39  4959.0  211.11  4966.6  210.48  4971.6  210.53  4979.2  208.88
  5002.8  208.64  5004.7  207.58  5004.9  207.08  5008.4  207.08  5008.7  207.58
  5013.2  207.98  5021.0  209.58  5041.8  210.43  5049.6  211.53  5056.1  211.83
  5063.9  212.66  5070.4  212.66  5084.8  214.57  5116.9  215.81  5127.7  216.59
  5198.0  219.27  5255.3  222.07  5269.6  222.38  5362.0  227.38  5390.0  228.29
#Mann=4,-1,0
  4695.4    0.12       0  5004.7    0.05       0  5008.7    0.12       0
  5116.9    0.07       0
Bank Sta=5004.7,5008.7
Exp/Cntr=0.3,0.1

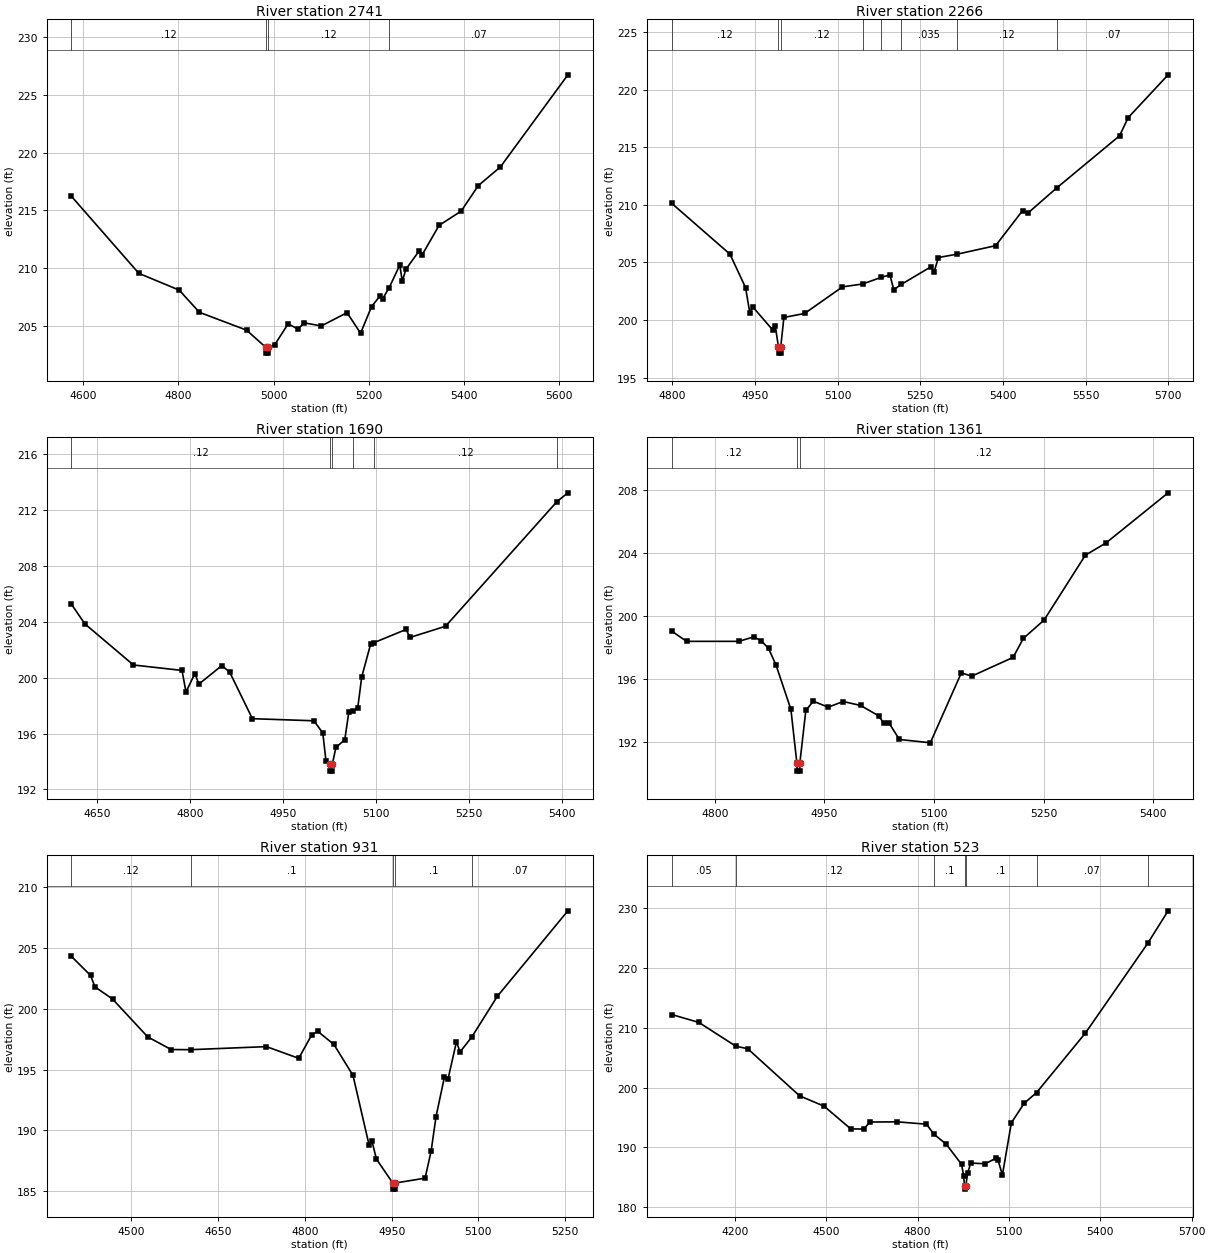
Type RM Length L Ch R = 1,2741,475,475,475
BEGIN DESCRIPTION:
Stream0828 6.0
END DESCRIPTION:
XS GIS Cut Line= 3
      2476774.98     13602474.98      2477075.00     13602775.00
      2477675.04     13602624.99
#Sta/Elev= 30
  4575.2  216.22  4716.7  209.56  4801.5  208.11  4843.9  206.19  4942.9  204.65
  4983.4  203.16  4983.6  202.66  4987.1  202.66  4987.4  203.16  5002.1  203.38
  5030.4  205.20  5051.0  204.73  5063.9  205.28  5100.0  205.01  5154.1  206.16
  5182.5  204.38  5205.6  206.69  5223.7  207.62  5228.8  207.35  5242.6  208.32
  5264.9  210.28  5270.1  208.88  5277.8  209.92  5306.1  211.53  5311.3  211.12
  5347.4  213.71  5393.8  214.94  5429.8  217.15  5476.2  218.76  5618.0  226.73
#Mann=4,-1,0
  4575.2    0.12       0  4983.4    0.05       0  4987.4    0.12       0
  5242.6    0.07       0
Bank Sta=4983.4,4987.4
Exp/Cntr=0.3,0.1

Type RM Length L Ch R = 1,2266,576,576,576
BEGIN DESCRIPTION:
Stream0828 5.0
END DESCRIPTION:
XS GIS Cut Line= 3
      2476775.01     13603125.00      2476975.00     13603075.00
      2477575.03     13602724.98
#Sta/Elev= 30
  4798.9  210.14  4904.5  205.73  4932.9  202.82  4940.6  200.64  4945.8  201.15
  4981.9  199.15  4987.0  199.45  4992.7  197.62  4993.0  197.12  4996.5  197.12
  4996.7  197.62  5002.5  200.22  5040.2  200.57  5108.8  202.88  5145.5  203.13
  5179.2  203.71  5194.8  203.92  5201.9  202.64  5215.7  203.10  5269.2  204.62
  5275.0  204.17  5282.9  205.43  5316.8  205.72  5386.7  206.46  5435.5  209.50
  5445.0  209.28  5497.6  211.48  5611.6  216.01  5627.3  217.59  5699.7  221.31
#Mann=8,-1,0
  4798.9    0.12       0  4992.7    0.05       0  4996.7    0.12       0
  5145.5   0.035       0  5179.2    0.12       0  5215.7   0.035       0
  5316.8    0.12       0  5497.6    0.07       0
Bank Sta=4992.7,4996.7
Exp/Cntr=0.3,0.1

Type RM Length L Ch R = 1,1690,329,329,329
BEGIN DESCRIPTION:
Stream0828 4.0
END DESCRIPTION:
XS GIS Cut Line= 3
      2476925.02     13603474.98      2477248.18     13603218.16
      2477497.42     13602919.07
#Sta/Elev= 30
  4608.0  205.24  4629.6  203.84  4708.1  200.90  4786.6  200.51  4793.0  198.97
  4807.4  200.29  4813.8  199.53  4850.7  200.85  4863.5  200.40  4900.3  197.06
  4999.7  196.91  5014.1  196.04  5019.3  194.00  5025.5  193.81  5025.8  193.31
  5029.3  193.31  5029.5  193.81  5035.3  195.01  5049.6  195.55  5056.1  197.52
  5063.2  197.62  5070.5  197.82  5077.0  200.05  5091.3  202.38  5097.0  202.50
  5148.6  203.44  5155.1  202.87  5212.4  203.67  5392.4  212.58  5410.1  213.21
#Mann=6,-1,0
  4608.0    0.12       0  5025.5    0.05       0  5029.5    0.12       0
  5063.2   0.035       0  5097.0    0.12       0  5392.4    0.07       0
Bank Sta=5025.5,5029.5
Exp/Cntr=0.3,0.1

Type RM Length L Ch R = 1,1361,430,430,430
BEGIN DESCRIPTION:
Stream0828 3.0
END DESCRIPTION:
XS GIS Cut Line= 3
      2477075.03     13603574.99      2477325.00     13603525.00
      2477625.01     13603224.99
#Sta/Elev= 30
  4741.0  199.03  4761.4  198.38  4832.8  198.38  4853.1  198.66  4863.3  198.43
  4873.5  197.93  4883.7  196.88  4904.1  194.06  4912.3  190.64  4912.6  190.14
  4916.1  190.14  4916.3  190.64  4924.5  193.99  4934.7  194.58  4955.1  194.20
  4975.5  194.56  4999.5  194.31  5024.2  193.65  5031.3  193.17  5038.3  193.20
  5052.5  192.15  5094.9  191.94  5137.3  196.38  5151.5  196.17  5208.1  197.36
  5222.2  198.57  5250.5  199.73  5307.0  203.85  5335.3  204.63  5420.2  207.81
#Mann=3,-1,0
  4741.0    0.12       0  4912.3    0.05       0  4916.3    0.12       0
Bank Sta=4912.3,4916.3
Exp/Cntr=0.3,0.1

Type RM Length L Ch R = 1,931,408,408,408
BEGIN DESCRIPTION:
Stream0828 2.0
END DESCRIPTION:
XS GIS Cut Line= 3
      2477024.96     13603825.01      2477625.00     13603725.00
      2477824.98     13603575.01
#Sta/Elev= 30
  4396.4  204.30  4429.4  202.74  4437.0  201.80  4467.4  200.80  4528.2  197.69
  4568.8  196.65  4602.4  196.64  4733.5  196.89  4789.3  195.93  4812.1  197.88
  4822.2  198.15  4850.1  197.07  4883.1  194.53  4910.9  188.82  4916.0  189.13
  4923.6  187.65  4952.0  185.68  4952.3  185.18  4955.8  185.18  4956.0  185.68
  5007.8  186.08  5018.3  188.32  5026.6  191.11  5041.2  194.38  5047.4  194.21
  5062.0  197.28  5068.3  196.45  5088.8  197.70  5132.8  201.03  5254.7  208.05
#Mann=5,-1,0
  4396.4    0.12       0  4602.4     0.1       0  4952.0    0.05       0
  4956.0     0.1       0  5088.8    0.07       0
Bank Sta=4952,4956
Exp/Cntr=0.3,0.1

Type RM Length L Ch R = 1,523,0,0,0
BEGIN DESCRIPTION:
Stream0828 1.0
END DESCRIPTION:
XS GIS Cut Line= 3
      2476756.24     13604157.78      2477775.00     13604075.00
      2478268.50     13603719.89
#Sta/Elev= 30
  3992.5  212.22  4081.5  210.90  4203.5  206.91  4242.1  206.50  4412.6  198.62
  4492.9  196.89  4580.3  193.10  4623.3  193.06  4643.4  194.24  4733.7  194.27
  4829.2  193.88  4853.9  192.19  4894.2  190.53  4944.4  187.16  4951.1  185.28
  4954.2  183.52  4954.4  183.02  4958.2  183.52  4964.4  185.71  4974.5  187.38
  5022.0  187.26  5057.6  188.19  5063.9  187.91  5078.5  185.38  5107.9  194.11
  5150.1  197.38  5190.6  199.16  5350.9  209.11  5555.5  224.11  5622.6  229.56
#Mann=7,-1,0
  3992.5    0.05       0  4203.5    0.12       0  4853.9     0.1       0
  4954.2    0.05       0  4958.2     0.1       0  5190.6    0.07       0
  5555.5    0.05       0
Bank Sta=4954.2,4958.2
Exp/Cntr=0.3,0.1

Chan Stop Cuts=-1