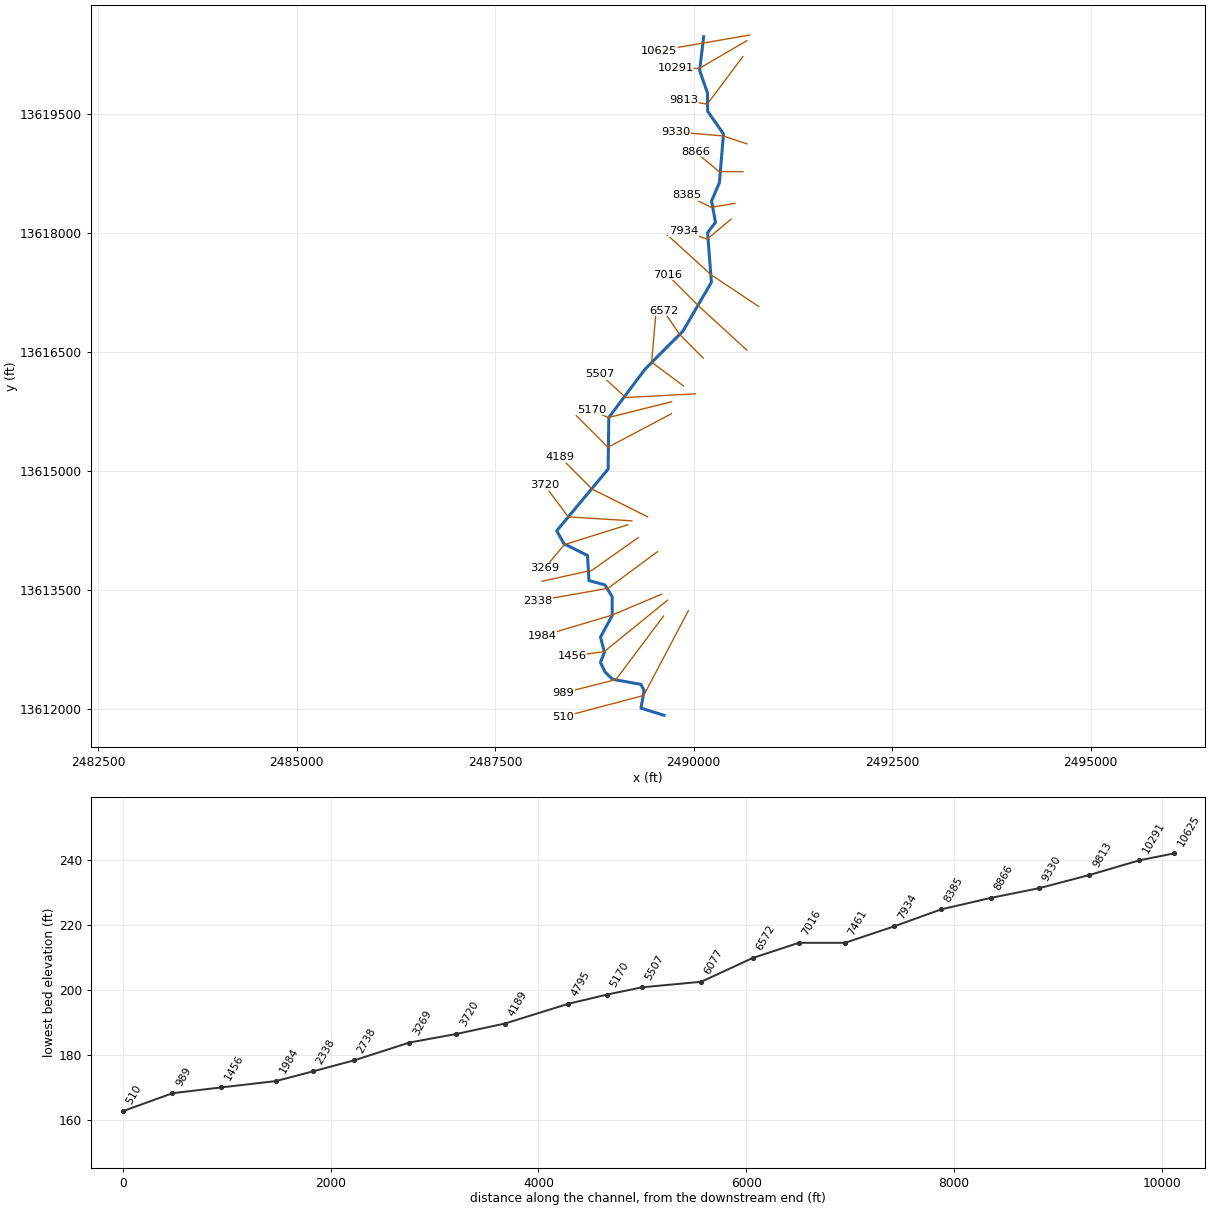
--- Stream0829.prj (project) ---

Proj Title=Stream0829 Base Level Engineering
Current Plan=p01
Default Exp/Contr=0.3,0.1
English Units
Geom File=g01
Flow File=f01
Plan File=p01
BEGIN DESCRIPTION:
Stream0829
END DESCRIPTION:

--- Stream0829.p01 (plan) ---

Plan Title=Multiple Run
Short Identifier=Multiple
Geom File=g01
Flow File=f01
Subcritical Flow
K Sum by GR= 0
Std Step Tol= 0.01
Critical Tol= 0.01
Num of Std Step Trials= 20
Max Error Tol= 0.3
Flow Tol Ratio= 0.001
Split Flow NTrial= 30
Split Flow Tol= 0.02
Split Flow Ratio= 0.02
Log Output Level= 0
Friction Slope Method= 1
Unsteady Friction Slope Method= 2
Unsteady Bridges Friction Slope Method= 1
Parabolic Critical Depth
Global Vel Dist=  1 , 1 , 1
Global Log Level= 0
CheckData=True
Encroach Param= -1, 0, 0, 0
BEGIN DESCRIPTION:
Multiple Run
END DESCRIPTION:

--- Stream0829.f01 (steady flow) ---

Flow Title=Multiple
Number of Profiles=7
Profile Names=10-year,25-year,50-year,1pct_min,100-year,1pct_plu,500-year
River Rch & RM= Stream0829,Reach-1,10625
     748    1216    1644    1076    2147    4284    3627
River Rch & RM= Stream0829,Reach-1,5507
    1138    1903    2619    1743    3478    6939    6079
Boundary for River Rch & Prof#=Stream0829,Reach-1,1
Up Type=0
Dn Type=3
Dn Slope=0.005
Boundary for River Rch & Prof#=Stream0829,Reach-1,2
Up Type=0
Dn Type=3
Dn Slope=0.005
Boundary for River Rch & Prof#=Stream0829,Reach-1,3
Up Type=0
Dn Type=3
Dn Slope=0.005
Boundary for River Rch & Prof#=Stream0829,Reach-1,4
Up Type=0
Dn Type=3
Dn Slope=0.005
Boundary for River Rch & Prof#=Stream0829,Reach-1,5
Up Type=0
Dn Type=3
Dn Slope=0.005
Boundary for River Rch & Prof#=Stream0829,Reach-1,6
Up Type=0
Dn Type=3
Dn Slope=0.005
Boundary for River Rch & Prof#=Stream0829,Reach-1,7
Up Type=0
Dn Type=3
Dn Slope=0.005

--- Stream0829.g01 (geometry) ---

Geom Title=Existing Conditions

River Reach=Stream0829,Reach-1
Reach XY= 30
      2490125.00     13620475.00      2490074.80     13620049.92
      2490173.78     13619764.50      2490176.05     13619535.44
      2490375.29     13619250.12      2490323.78     13618635.50
      2490225.07     13618404.97      2490274.40     13618135.62
      2490174.96     13618005.02      2490222.76     13617380.93
      2489864.22     13616765.32      2489388.63     13616288.21
      2488930.46     13615677.45      2488921.45     13615026.47
      2488274.49     13614250.03      2488365.29     13614085.75
      2488661.64     13613938.35      2488680.34     13613622.26
      2488881.48     13613567.30      2488972.76     13613419.07
      2488972.93     13613180.86      2488825.09     13612909.61
      2488875.50     13612719.84      2488825.08     13612590.39
      2488880.82     13612472.69      2488976.45     13612378.53
      2489335.06     13612314.39      2489375.57     13612235.23
      2489335.03     13612014.94      2489625.00     13611925.00

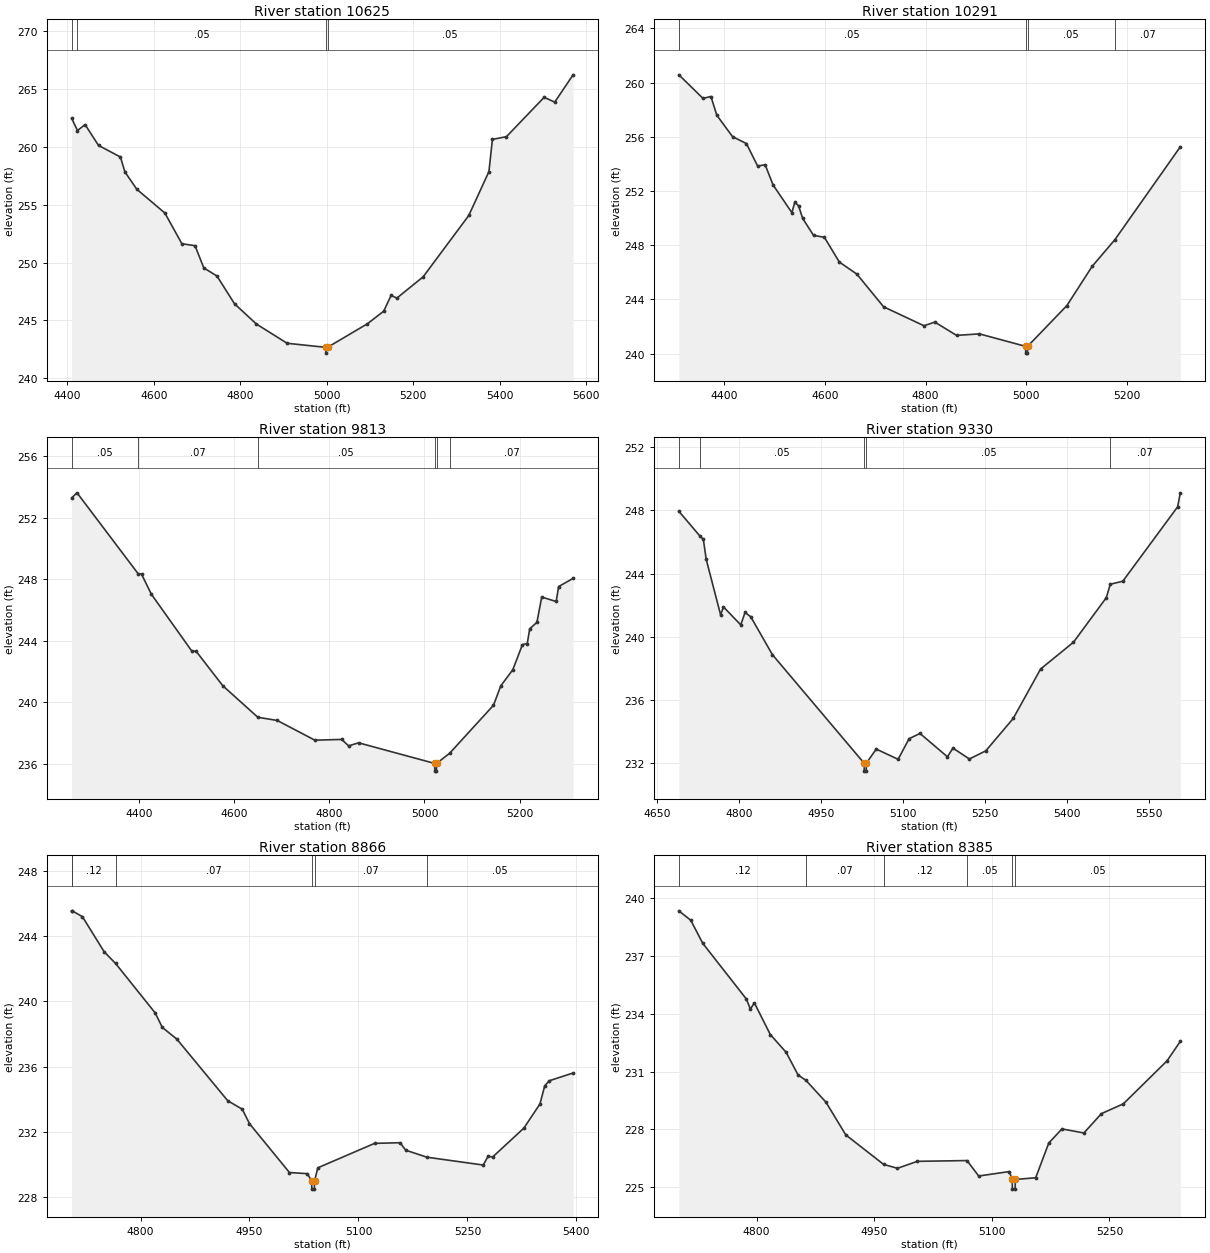
Type RM Length L Ch R = 1,10625,334,334,334
BEGIN DESCRIPTION:
XS7793
END DESCRIPTION:
XS GIS Cut Line= 2
      2490706.37     13620496.07      2489563.17     13620298.79
#Sta/Elev= 30
  4410.1  262.47  4423.7  261.41  4441.3  261.92  4472.4  260.12  4523.1  259.12
  4533.3  257.84  4561.0  256.33  4625.9  254.28  4665.2  251.63  4695.6  251.46
  4715.9  249.54  4746.4  248.84  4787.0  246.44  4837.7  244.69  4908.7  243.03
  4998.1  242.68  4998.3  242.18  5002.1  242.68  5094.6  244.72  5132.0  245.80
  5149.3  247.17  5162.4  246.93  5223.3  248.77  5328.9  254.07  5375.5  257.86
  5383.6  260.64  5416.1  260.88  5503.3  264.28  5527.7  263.86  5570.2  266.22
#Mann=4,-1,0
  4410.1    0.07       0  4423.7    0.05       0  4998.1    0.05       0
  5002.1    0.05       0
Bank Sta=4998.1,5002.1
Exp/Cntr=0.3,0.1

Type RM Length L Ch R = 1,10291,478,478,478
BEGIN DESCRIPTION:
Stream0829 22.0
END DESCRIPTION:
XS GIS Cut Line= 3
      2490669.94     13620425.00      2490069.94     13620075.00
      2489769.97     13620075.00
#Sta/Elev= 30
  4310.8  260.57  4358.7  258.83  4374.4  258.97  4386.0  257.59  4417.4  256.00
  4444.7  255.50  4467.0  253.84  4481.9  253.93  4497.7  252.44  4534.9  250.40
  4540.7  251.16  4548.1  250.91  4556.4  249.97  4577.9  248.72  4599.4  248.58
  4629.1  246.75  4663.9  245.86  4716.8  243.45  4797.0  242.05  4818.5  242.32
  4861.5  241.34  4907.0  241.45  4998.4  240.53  4998.7  240.03  5002.2  240.03
  5002.4  240.53  5080.4  243.54  5130.4  246.43  5175.5  248.40  5305.4  255.26
#Mann=4,-1,0
  4310.8    0.05       0  4998.4    0.05       0  5002.4    0.05       0
  5175.5    0.07       0
Bank Sta=4998.4,5002.4
Exp/Cntr=0.3,0.1

Type RM Length L Ch R = 1,9813,483,483,483
BEGIN DESCRIPTION:
Stream0829 21.0
END DESCRIPTION:
XS GIS Cut Line= 3
      2490619.96     13620225.02      2490169.94     13619625.00
      2489870.01     13619674.99
#Sta/Elev= 30
  4258.3  253.28  4269.7  253.61  4398.0  248.36  4405.2  248.33  4426.0  247.02
  4511.4  243.31  4519.7  243.33  4576.0  241.08  4649.7  239.03  4690.6  238.82
  4769.7  237.54  4826.0  237.59  4840.6  237.17  4861.4  237.37  5021.5  236.03
  5021.7  235.53  5025.2  235.53  5025.5  236.03  5052.9  236.69  5145.1  239.81
  5160.4  241.07  5185.7  242.12  5206.0  243.75  5216.1  243.82  5221.2  244.77
  5236.4  245.20  5246.5  246.84  5276.9  246.55  5282.0  247.52  5312.4  248.05
#Mann=6,-1,0
  4258.3    0.05       0  4398.0    0.07       0  4649.7    0.05       0
  5021.5    0.05       0  5025.5    0.05       0  5052.9    0.07       0
Bank Sta=5021.5,5025.5
Exp/Cntr=0.3,0.1

Type RM Length L Ch R = 1,9330,464,464,464
BEGIN DESCRIPTION:
Stream0829 20.0
END DESCRIPTION:
XS GIS Cut Line= 3
      2490669.98     13619124.99      2490369.94     13619225.00
      2489769.99     13619275.00
#Sta/Elev= 30
  4689.5  247.95  4728.5  246.36  4734.3  246.17  4739.6  244.89  4765.9  241.38
  4771.2  241.88  4802.8  240.74  4810.7  241.53  4821.2  241.25  4860.8  238.85
  5028.8  231.96  5029.0  231.46  5032.5  231.46  5032.8  231.96  5050.9  232.86
  5091.0  232.21  5111.1  233.52  5131.1  233.85  5181.3  232.37  5191.4  232.92
  5221.5  232.23  5251.6  232.75  5301.7  234.80  5351.9  237.94  5412.1  239.64
  5472.3  242.47  5479.5  243.32  5502.4  243.51  5602.8  248.23  5607.8  249.12
#Mann=5,-1,0
  4689.5    0.12       0  4728.5    0.05       0  5028.8    0.05       0
  5032.8    0.05       0  5479.5    0.07       0
Bank Sta=5028.8,5032.8
Exp/Cntr=0.3,0.1

Type RM Length L Ch R = 1,8866,481,481,481
BEGIN DESCRIPTION:
Stream0829 19.0
END DESCRIPTION:
XS GIS Cut Line= 3
      2490619.90     13618775.00      2490319.94     13618775.00
      2490019.99     13619024.96
#Sta/Elev= 30
  4705.1  245.56  4705.9  245.56  4720.0  245.20  4750.0  243.04  4765.6  242.33
  4820.0  239.30  4830.0  238.40  4850.0  237.68  4920.0  233.90  4940.0  233.38
  4950.0  232.49  5005.0  229.49  5029.7  229.42  5035.5  228.97  5035.8  228.47
  5039.3  228.47  5039.5  228.97  5044.1  229.78  5122.2  231.28  5157.3  231.32
  5165.1  230.86  5194.3  230.43  5271.8  229.95  5278.4  230.48  5284.9  230.45
  5327.8  232.22  5349.9  233.70  5356.5  234.82  5363.0  235.13  5395.5  235.60
#Mann=6,-1,0
  4705.1    0.07       0  4705.9    0.12       0  4765.6    0.07       0
  5035.5    0.05       0  5039.5    0.07       0  5194.3    0.05       0
Bank Sta=5035.5,5039.5
Exp/Cntr=0.3,0.1

Type RM Length L Ch R = 1,8385,451,451,451
BEGIN DESCRIPTION:
Stream0829 18.0
END DESCRIPTION:
XS GIS Cut Line= 3
      2490519.98     13618375.01      2490219.94     13618325.00
      2489919.93     13618475.01
#Sta/Elev= 30
  4700.8  239.33  4716.0  238.84  4731.2  237.65  4786.9  234.76  4792.0  234.24
  4797.1  234.56  4817.4  232.92  4837.6  232.00  4852.9  230.82  4862.8  230.55
  4888.3  229.42  4913.7  227.72  4962.0  226.19  4979.6  225.99  5004.9  226.35
  5068.3  226.39  5083.2  225.59  5122.3  225.82  5125.9  225.41  5126.2  224.91
  5129.7  224.91  5129.9  225.41  5155.9  225.50  5172.6  227.30  5189.4  228.03
  5217.4  227.82  5239.7  228.82  5267.7  229.33  5323.5  231.56  5340.4  232.57
#Mann=6,-1,0
  4700.8    0.12       0  4862.8    0.07       0  4962.0    0.12       0
  5068.3    0.05       0  5125.9    0.05       0  5129.9    0.05       0
Bank Sta=5125.9,5129.9
Exp/Cntr=0.3,0.1

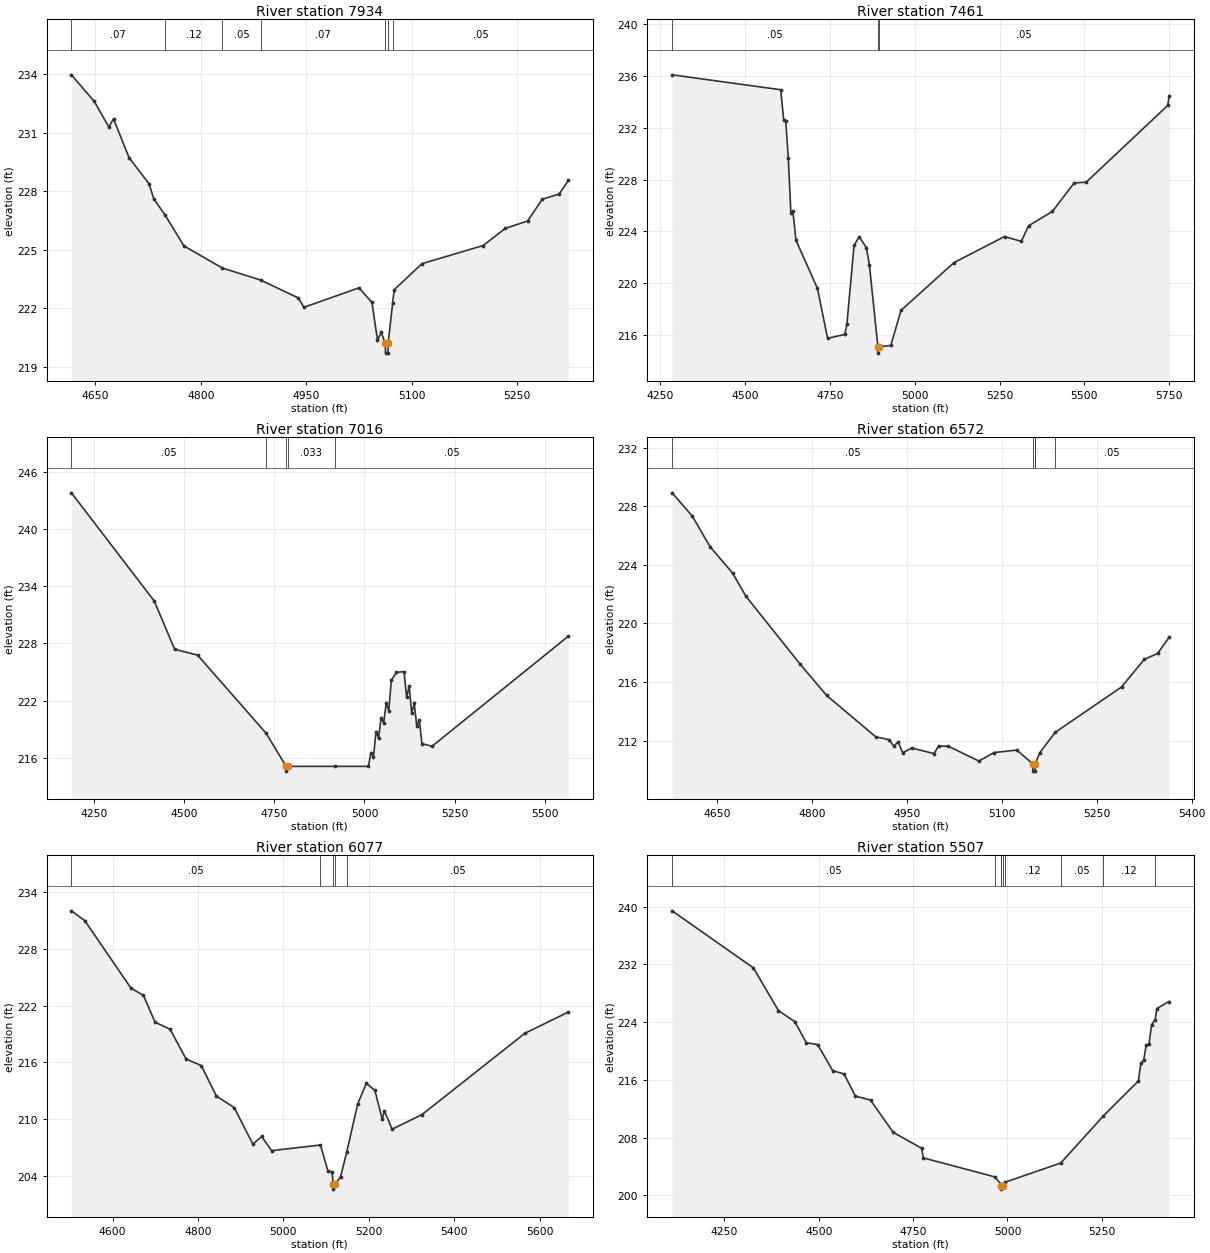
Type RM Length L Ch R = 1,7934,473,473,473
BEGIN DESCRIPTION:
Stream0829 17.0
END DESCRIPTION:
XS GIS Cut Line= 3
      2490469.95     13618175.01      2490169.94     13617925.00
      2489870.00     13618024.98
#Sta/Elev= 30
  4615.9  233.97  4648.4  232.61  4669.2  231.29  4675.8  231.71  4697.9  229.72
  4726.5  228.37  4733.0  227.61  4749.2  226.77  4776.0  225.19  4830.3  224.06
  4885.0  223.44  4938.7  222.52  4946.5  222.04  5024.8  223.04  5043.3  222.29
  5051.2  220.36  5056.5  220.75  5062.3  220.19  5062.6  219.69  5066.1  219.69
  5066.3  220.19  5072.7  222.24  5074.9  222.94  5114.4  224.28  5201.4  225.21
  5233.0  226.09  5264.6  226.47  5285.7  227.59  5309.5  227.85  5322.6  228.55
#Mann=7,-1,0
  4615.9    0.07       0  4749.2    0.12       0  4830.3    0.05       0
  4885.0    0.07       0  5062.3    0.05       0  5066.3    0.07       0
  5072.7    0.05       0
Bank Sta=5062.3,5066.3
Exp/Cntr=0.3,0.1

Type RM Length L Ch R = 1,7461,445,445,445
BEGIN DESCRIPTION:
Stream0829 16.0
END DESCRIPTION:
XS GIS Cut Line= 3
      2490819.93     13617075.01      2490219.94     13617475.00
      2489669.94     13617975.00
#Sta/Elev= 30
  4285.1  236.08  4605.0  234.93  4614.1  232.57  4620.1  232.48  4627.5  229.65
  4635.1  225.41  4641.1  225.54  4650.1  223.31  4713.2  219.61  4743.3  215.74
  4794.3  216.05  4800.3  216.87  4821.4  222.93  4836.4  223.58  4857.4  222.75
  4866.4  221.43  4891.5  215.10  4891.7  214.60  4895.5  215.10  4929.5  215.19
  4959.6  217.90  5116.0  221.59  5264.6  223.60  5314.0  223.23  5335.6  224.43
  5405.9  225.54  5470.0  227.74  5505.2  227.79  5745.7  233.72  5749.5  234.42
#Mann=3,-1,0
  4285.1    0.05       0  4891.5    0.05       0  4895.5    0.05       0
Bank Sta=4891.5,4895.5
Exp/Cntr=0.3,0.1

Type RM Length L Ch R = 1,7016,444,444,444
BEGIN DESCRIPTION:
Stream0829 15.0
END DESCRIPTION:
XS GIS Cut Line= 3
      2490669.91     13616525.03      2490069.94     13617075.00
      2489670.00     13617474.94
#Sta/Elev= 30
  4186.4  243.79  4416.3  232.45  4473.0  227.38  4536.6  226.77  4727.0  218.57
  4782.4  215.10  4782.7  214.60  4786.4  215.10  4917.2  215.10  5010.9  215.10
  5017.9  216.55  5025.0  216.10  5032.1  218.75  5039.1  218.09  5046.2  220.18
  5053.3  219.69  5060.4  221.73  5067.4  220.93  5074.5  224.12  5088.6  224.96
  5109.9  225.04  5116.9  222.35  5124.0  223.52  5131.1  220.68  5138.1  221.74
  5145.2  219.30  5152.3  219.97  5159.4  217.48  5187.6  217.21  5565.9  228.75
#Mann=5,-1,0
  4186.4    0.05       0  4727.0   0.033       0  4782.4    0.05       0
  4786.4   0.033       0  4917.2    0.05       0
Bank Sta=4782.4,4786.4
Exp/Cntr=0.3,0.1

Type RM Length L Ch R = 1,6572,495,495,495
BEGIN DESCRIPTION:
Stream0829 14.0
END DESCRIPTION:
XS GIS Cut Line= 3
      2490119.95     13616424.99      2489819.94     13616725.00
      2489619.96     13617024.98
#Sta/Elev= 30
  4579.5  228.93  4611.3  227.34  4639.6  225.24  4674.9  223.45  4696.1  221.86
  4781.0  217.26  4823.4  215.09  4901.2  212.25  4922.4  212.06  4929.5  211.62
  4936.6  211.91  4943.6  211.16  4957.8  211.49  4993.1  211.11  5000.2  211.62
  5015.7  211.61  5063.9  210.60  5087.9  211.18  5123.9  211.35  5148.9  210.41
  5149.2  209.91  5152.7  209.91  5152.9  210.41  5153.1  210.43  5160.0  211.16
  5184.5  212.56  5289.2  215.66  5325.2  217.55  5346.2  217.95  5364.3  219.05
#Mann=5,-1,0
  4579.5    0.05       0  5148.9    0.05       0  5152.9    0.05       0
  5153.1    0.07       0  5184.5    0.05       0
Bank Sta=5148.9,5152.9
Exp/Cntr=0.3,0.1

Type RM Length L Ch R = 1,6077,570,570,570
BEGIN DESCRIPTION:
Stream0829 13.0
END DESCRIPTION:
XS GIS Cut Line= 3
      2489869.94     13616075.00      2489469.94     13616375.00
      2489527.80     13617036.28
#Sta/Elev= 30
  4503.6  232.03  4534.8  231.00  4643.1  223.85  4672.3  223.08  4699.4  220.25
  4734.8  219.50  4772.3  216.34  4807.7  215.66  4843.1  212.43  4884.8  211.21
  4928.6  207.34  4949.4  208.15  4972.3  206.65  5086.8  207.25  5104.0  204.55
  5114.0  204.36  5117.0  203.08  5117.2  202.58  5121.1  203.08  5134.1  203.91
  5148.5  206.51  5174.2  211.61  5194.3  213.77  5214.4  213.03  5231.6  209.96
  5236.6  210.88  5254.6  208.92  5324.8  210.47  5565.7  219.07  5667.4  221.32
#Mann=5,-1,0
  4503.6    0.05       0  5086.8    0.12       0  5117.0    0.05       0
  5121.1    0.12       0  5148.5    0.05       0
Bank Sta=5117,5121.1
Exp/Cntr=0.3,0.1

Type RM Length L Ch R = 1,5507,337,337,337
BEGIN DESCRIPTION:
Stream0829 12.0
END DESCRIPTION:
XS GIS Cut Line= 3
      2490019.97     13615975.00      2489143.37     13615928.49
      2488819.94     13616225.00
#Sta/Elev= 30
  4111.5  239.42  4326.8  231.52  4393.3  225.60  4436.9  224.05  4467.0  221.15
  4497.0  220.90  4537.1  217.28  4567.1  216.82  4597.1  213.76  4637.2  213.20
  4697.3  208.73  4772.3  206.54  4777.4  205.19  4967.0  202.56  4981.6  201.61
  4983.6  201.37  4984.0  200.87  4988.5  201.37  4993.2  201.82  5141.3  204.49
  5254.4  211.03  5346.7  215.84  5353.5  218.32  5360.9  218.74  5367.6  220.82
  5375.0  220.99  5381.8  223.64  5391.4  224.36  5396.0  225.89  5428.1  226.86
#Mann=9,-1,0
  4111.5    0.05       0  4967.0    0.12       0  4981.6    0.05       0
  4983.6    0.05       0  4988.5    0.05       0  4993.2    0.12       0
  5141.3    0.05       0  5254.4    0.12       0  5391.4    0.07       0
Bank Sta=4983.6,4988.5
Exp/Cntr=0.3,0.1

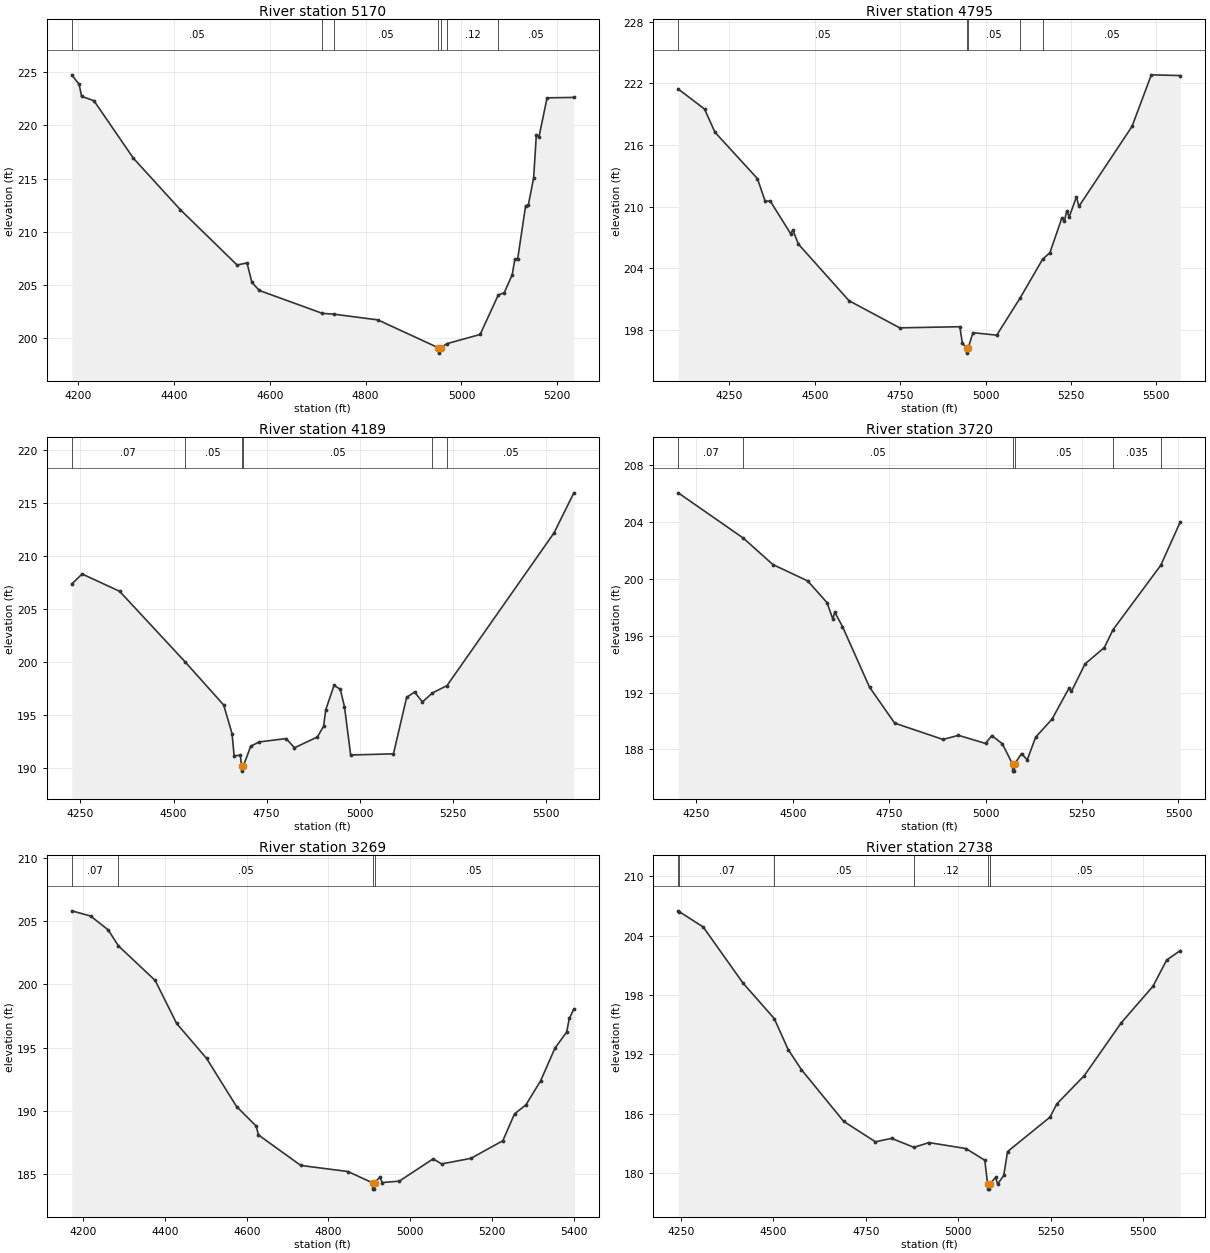
Type RM Length L Ch R = 1,5170,375,375,375
BEGIN DESCRIPTION:
Stream0829 11.0
END DESCRIPTION:
XS GIS Cut Line= 3
      2489719.90     13615874.99      2488919.94     13615675.00
      2488719.93     13615775.01
#Sta/Elev= 30
  4186.4  224.74  4201.8  223.84  4206.9  222.72  4232.7  222.31  4315.1  216.91
  4413.1  212.08  4531.6  206.89  4552.2  207.09  4562.5  205.26  4578.0  204.50
  4709.7  202.35  4733.2  202.28  4825.4  201.74  4951.8  199.12  4952.2  198.62
  4956.7  199.12  4969.7  199.51  5038.9  200.37  5076.8  204.07  5089.2  204.29
  5105.9  205.97  5111.6  207.47  5117.2  207.42  5133.9  212.45  5139.5  212.51
  5150.7  215.07  5156.3  219.12  5161.9  218.94  5178.7  222.58  5234.6  222.62
#Mann=7,-1,0
  4186.4    0.05       0  4709.7    0.12       0  4733.2    0.05       0
  4951.8    0.05       0  4956.7    0.05       0  4969.7    0.12       0
  5076.8    0.05       0
Bank Sta=4951.8,4956.7
Exp/Cntr=0.3,0.1

Type RM Length L Ch R = 1,4795,606,606,606
BEGIN DESCRIPTION:
Stream0829 10.0
END DESCRIPTION:
XS GIS Cut Line= 3
      2489719.96     13615725.01      2488919.94     13615301.46
      2488520.72     13615700.67
#Sta/Elev= 30
  4100.5  221.46  4177.5  219.51  4207.9  217.26  4332.4  212.74  4355.0  210.54
  4369.8  210.56  4430.2  207.35  4435.8  207.77  4452.2  206.37  4600.5  200.86
  4748.9  198.22  4924.9  198.33  4932.1  196.75  4944.4  196.26  4944.8  195.76
  4949.3  196.26  4963.2  197.75  5032.9  197.51  5101.6  201.14  5167.4  204.91
  5188.5  205.53  5223.9  208.94  5230.9  208.61  5238.0  209.61  5245.1  209.02
  5266.3  210.97  5273.4  210.04  5428.9  217.82  5485.5  222.84  5570.3  222.77
#Mann=5,-1,0
  4100.5    0.05       0  4944.4    0.05       0  4949.3    0.05       0
  5101.6    0.12       0  5167.4    0.05       0
Bank Sta=4944.4,4949.3
Exp/Cntr=0.3,0.1

Type RM Length L Ch R = 1,4189,469,469,469
BEGIN DESCRIPTION:
Stream0829 9.0
END DESCRIPTION:
XS GIS Cut Line= 3
      2489419.93     13614425.01      2488719.94     13614775.00
      2488319.94     13615175.00
#Sta/Elev= 30
  4226.6  207.34  4254.5  208.28  4355.1  206.65  4530.2  200.03  4634.6  195.93
  4657.0  193.24  4662.6  191.15  4679.3  191.19  4682.4  190.20  4682.8  189.70
  4687.4  190.20  4707.3  192.05  4729.7  192.45  4802.3  192.77  4824.7  191.90
  4886.2  192.92  4902.9  193.93  4908.6  195.48  4930.9  197.78  4947.7  197.42
  4958.9  195.78  4975.6  191.22  5090.5  191.33  5125.8  196.65  5147.1  197.16
  5168.3  196.22  5195.1  197.07  5234.2  197.76  5521.8  212.16  5574.9  215.93
#Mann=6,-1,0
  4226.6    0.07       0  4530.2    0.05       0  4682.4    0.05       0
  4687.4    0.05       0  5195.1   0.035       0  5234.2    0.05       0
Bank Sta=4682.4,4687.4
Exp/Cntr=0.3,0.1

Type RM Length L Ch R = 1,3720,451,451,451
BEGIN DESCRIPTION:
Stream0829 8.0
END DESCRIPTION:
XS GIS Cut Line= 3
      2489219.92     13614375.00      2488419.94     13614425.00
      2488119.97     13614824.97
#Sta/Elev= 30
  4203.2  206.06  4372.0  202.87  4448.6  201.01  4538.8  199.86  4588.9  198.33
  4603.9  197.18  4608.9  197.66  4628.9  196.65  4699.1  192.38  4764.2  189.85
  4889.5  188.70  4929.6  188.99  4999.7  188.42  5016.1  188.97  5043.2  188.40
  5069.8  186.97  5070.2  186.47  5074.6  186.47  5075.0  186.97  5093.2  187.71
  5107.8  187.26  5129.7  188.86  5172.4  190.14  5216.1  192.31  5222.4  192.08
  5257.8  194.02  5307.8  195.17  5330.4  196.43  5454.0  200.96  5504.7  204.02
#Mann=6,-1,0
  4203.2    0.07       0  4372.0    0.05       0  5069.8    0.05       0
  5075.0    0.05       0  5330.4   0.035       0  5454.0    0.05       0
Bank Sta=5069.8,5075
Exp/Cntr=0.3,0.1

Type RM Length L Ch R = 1,3269,531,531,531
BEGIN DESCRIPTION:
Stream0829 7.0
END DESCRIPTION:
XS GIS Cut Line= 3
      2489169.91     13614324.99      2488369.94     13614075.00
      2488119.96     13613775.03
#Sta/Elev= 30
  4171.9  205.80  4217.9  205.39  4260.9  204.30  4286.2  203.03  4376.1  200.30
  4428.5  196.91  4501.8  194.15  4575.2  190.35  4623.4  188.80  4628.6  188.11
  4732.3  185.70  4847.6  185.22  4907.8  184.33  4908.2  183.83  4912.6  183.83
  4913.0  184.33  4926.2  184.79  4931.4  184.35  4973.3  184.46  5056.2  186.22
  5077.0  185.82  5148.6  186.26  5226.7  187.65  5255.3  189.77  5283.4  190.49
  5319.1  192.38  5354.3  194.96  5382.9  196.23  5389.4  197.30  5400.5  198.05
#Mann=4,-1,0
  4171.9    0.07       0  4286.2    0.05       0  4907.8    0.05       0
  4913.0    0.05       0
Bank Sta=4907.8,4913
Exp/Cntr=0.3,0.1

Type RM Length L Ch R = 1,2738,400,400,400
BEGIN DESCRIPTION:
Stream0829 6.0
END DESCRIPTION:
XS GIS Cut Line= 3
      2489300.19     13614163.18      2488718.08     13613751.89
      2488088.97     13613613.97
#Sta/Elev= 30
  4243.1  206.52  4245.4  206.45  4310.7  204.88  4418.3  199.20  4502.5  195.62
  4540.2  192.48  4575.9  190.45  4690.2  185.21  4776.0  183.14  4819.6  183.49
  4880.1  182.58  4920.6  183.06  5020.4  182.46  5071.6  181.27  5079.2  178.85
  5079.6  178.35  5084.1  178.35  5084.5  178.85  5084.6  178.85  5101.0  179.55
  5106.1  178.85  5122.8  179.74  5133.0  182.15  5247.8  185.64  5266.1  186.97
  5340.6  189.85  5440.2  195.18  5526.1  198.89  5563.0  201.54  5599.9  202.50
#Mann=7,-1,0
  4243.1    0.05       0  4245.4    0.07       0  4502.5    0.05       0
  4880.1    0.12       0  5079.2    0.05       0  5084.5    0.12       0
  5084.6    0.05       0
Bank Sta=5079.2,5084.5
Exp/Cntr=0.3,0.1

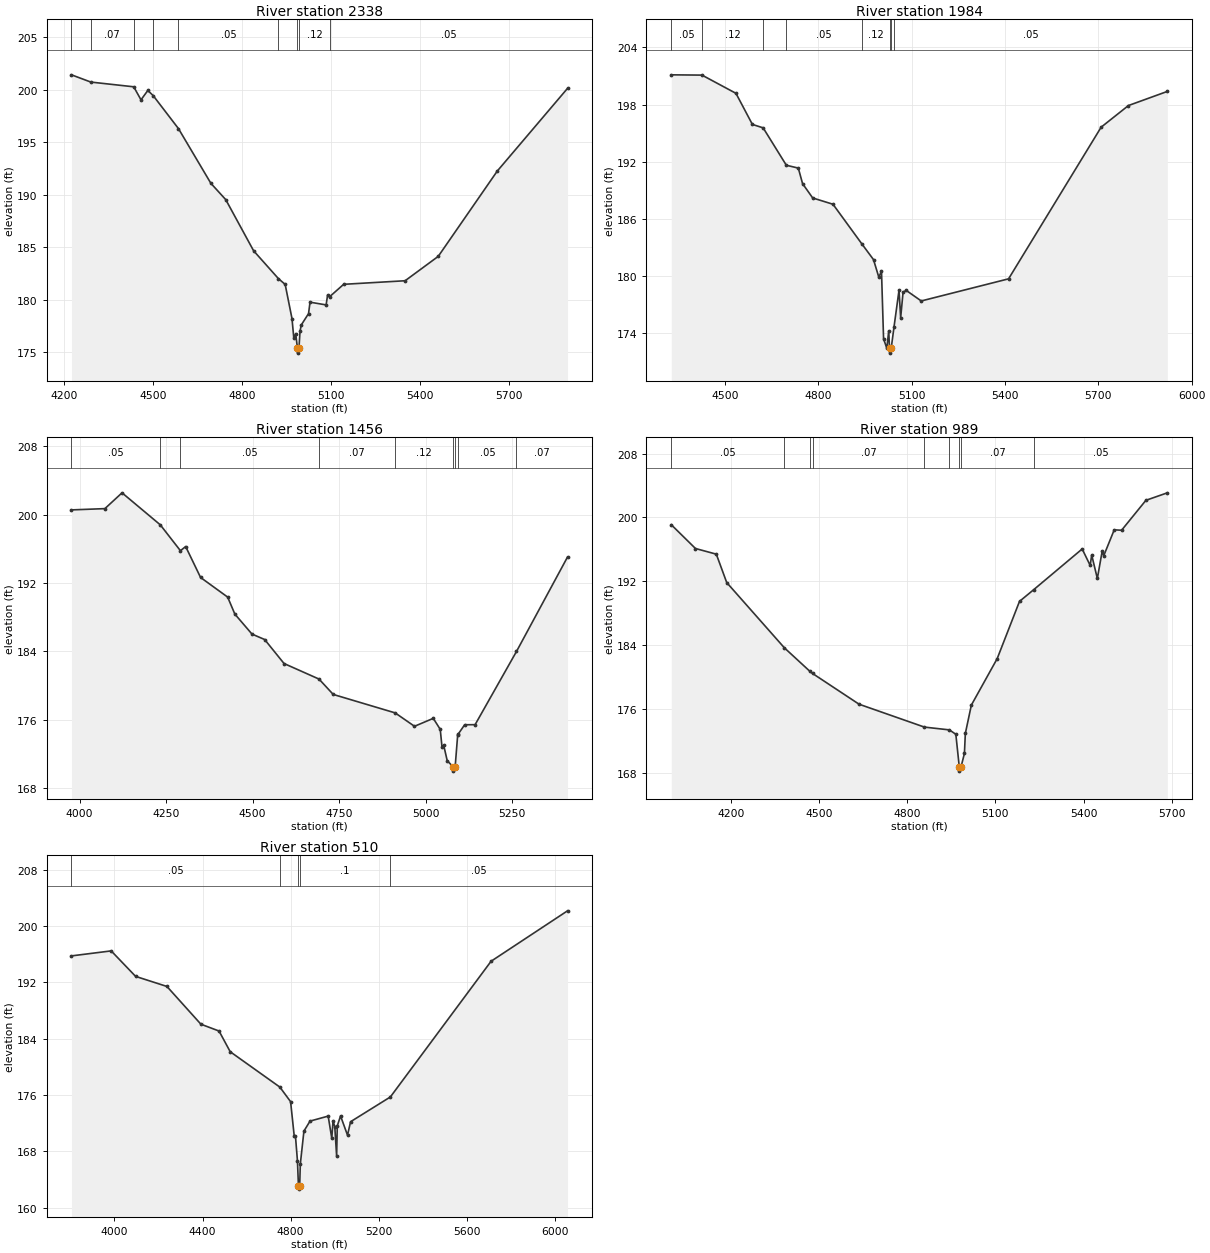
Type RM Length L Ch R = 1,2338,354,354,354
BEGIN DESCRIPTION:
Stream0829 5.0
END DESCRIPTION:
XS GIS Cut Line= 3
      2489542.97     13613986.14      2488919.94     13613525.00
      2488035.61     13613369.03
#Sta/Elev= 30
  4225.4  201.40  4290.8  200.71  4435.4  200.26  4459.9  199.02  4482.9  199.91
  4500.8  199.43  4586.3  196.28  4695.7  191.07  4745.8  189.52  4839.8  184.65
  4923.2  182.01  4946.2  181.45  4969.2  178.20  4975.4  176.32  4981.8  176.77
  4987.4  175.41  4987.8  174.91  4992.8  175.41  4996.3  176.99  5000.5  177.59
  5025.0  178.67  5030.1  179.76  5084.3  179.50  5089.4  180.45  5097.0  180.30
  5143.5  181.46  5350.8  181.80  5462.5  184.12  5661.6  192.24  5898.5  200.11
#Mann=9,-1,0
  4225.4    0.05       0  4290.8    0.07       0  4435.4    0.05       0
  4500.8    0.07       0  4586.3    0.05       0  4923.2    0.12       0
  4987.4    0.05       0  4992.8    0.12       0  5097.0    0.05       0
Bank Sta=4987.4,4992.8
Exp/Cntr=0.3,0.1

Type RM Length L Ch R = 1,1984,528,528,528
BEGIN DESCRIPTION:
Stream0829 4.0
END DESCRIPTION:
XS GIS Cut Line= 3
      2489593.57     13613449.97      2488971.39     13613186.94
      2488091.25     13612923.91
#Sta/Elev= 30
  4327.7  201.12  4426.4  201.09  4535.5  199.18  4588.3  195.92  4622.9  195.56
  4697.4  191.64  4735.9  191.34  4749.6  189.71  4782.1  188.21  4847.3  187.55
  4939.5  183.42  4977.6  181.74  4994.6  179.90  5003.2  180.54  5009.9  173.44
  5020.3  172.45  5026.5  174.29  5029.0  172.44  5029.4  171.94  5034.4  172.44
  5043.6  174.72  5059.6  178.55  5064.8  175.64  5072.5  178.32  5082.9  178.51
  5131.0  177.41  5411.6  179.73  5709.1  195.63  5796.8  197.90  5921.8  199.38
#Mann=8,-1,0
  4327.7    0.05       0  4426.4    0.12       0  4622.9    0.07       0
  4697.4    0.05       0  4939.5    0.12       0  5029.0    0.05       0
  5034.4    0.12       0  5043.6    0.05       0
Bank Sta=5029,5034.4
Exp/Cntr=0.3,0.1

Type RM Length L Ch R = 1,1456,467,467,467
BEGIN DESCRIPTION:
Stream0829 3.0
END DESCRIPTION:
XS GIS Cut Line= 3
      2489669.97     13613375.03      2488869.94     13612725.00
      2488469.97     13612675.00
#Sta/Elev= 30
  3976.3  200.57  4072.9  200.72  4122.5  202.57  4233.1  198.82  4291.3  195.79
  4306.4  196.28  4349.5  192.66  4427.8  190.36  4448.6  188.37  4498.1  186.03
  4534.8  185.39  4590.8  182.58  4691.9  180.76  4733.0  178.96  4912.0  176.80
  4967.9  175.23  5022.2  176.16  5042.3  174.87  5047.4  172.83  5052.4  172.99
  5062.5  171.20  5079.8  170.48  5080.3  169.98  5085.4  170.48  5092.7  174.20
  5094.8  174.35  5112.9  175.41  5143.1  175.42  5262.7  183.99  5410.2  195.05
#Mann=9,-1,0
  3976.3    0.05       0  4233.1    0.12       0  4291.3    0.05       0
  4691.9    0.07       0  4912.0    0.12       0  5079.8    0.05       0
  5085.4    0.12       0  5094.8    0.05       0  5262.7    0.07       0
Bank Sta=5079.8,5085.4
Exp/Cntr=0.3,0.1

Type RM Length L Ch R = 1,989,479,479,479
BEGIN DESCRIPTION:
Stream0829 2.0
END DESCRIPTION:
XS GIS Cut Line= 3
      2489619.93     13613174.98      2489019.94     13612375.00
      2488354.33     13612205.65
#Sta/Elev= 30
  3998.1  199.09  4080.3  196.11  4151.2  195.40  4186.6  191.84  4382.6  183.66
  4469.8  180.70  4478.6  180.44  4636.6  176.59  4858.8  173.72  4943.8  173.37
  4965.7  172.82  4977.5  168.70  4978.0  168.20  4983.1  168.70  4994.9  170.41
  4998.0  172.92  5018.5  176.48  5106.4  182.31  5182.2  189.48  5231.2  190.97
  5395.3  196.05  5422.5  193.99  5427.7  195.29  5446.9  192.35  5463.4  195.79
  5468.6  195.20  5504.3  198.45  5529.4  198.40  5612.0  202.15  5684.9  203.09
#Mann=9,-1,0
  3998.1    0.05       0  4382.6    0.07       0  4469.8    0.05       0
  4478.6    0.07       0  4858.8     0.1       0  4943.8    0.07       0
  4977.5    0.05       0  4983.1    0.07       0  5231.2    0.05       0
Bank Sta=4977.5,4983.1
Exp/Cntr=0.3,0.1

Type RM Length L Ch R = 1,510,0,0,0
BEGIN DESCRIPTION:
Stream0829 1.0
END DESCRIPTION:
XS GIS Cut Line= 3
      2489932.46     13613242.59      2489369.94     13612175.00
      2488359.63     13611907.28
#Sta/Elev= 30
  3805.1  195.76  3985.4  196.47  4096.3  192.85  4238.5  191.42  4392.7  186.06
  4475.1  185.09  4525.8  182.15  4751.1  177.13  4799.9  175.06  4816.3  170.20
  4822.0  170.15  4831.0  166.67  4835.5  163.14  4835.9  162.64  4841.2  163.14
  4844.0  166.19  4860.4  170.88  4888.1  172.30  4970.5  173.01  4986.9  169.85
  4992.5  172.34  5000.5  171.50  5008.9  167.33  5011.8  171.62  5026.7  173.03
  5058.3  170.30  5072.1  172.21  5252.9  175.73  5710.1  195.00  6057.0  202.16
#Mann=5,-1,0
  3805.1    0.05       0  4751.1     0.1       0  4835.5    0.05       0
  4841.2     0.1       0  5252.9    0.05       0
Bank Sta=4835.5,4841.2
Exp/Cntr=0.3,0.1

Chan Stop Cuts=-1