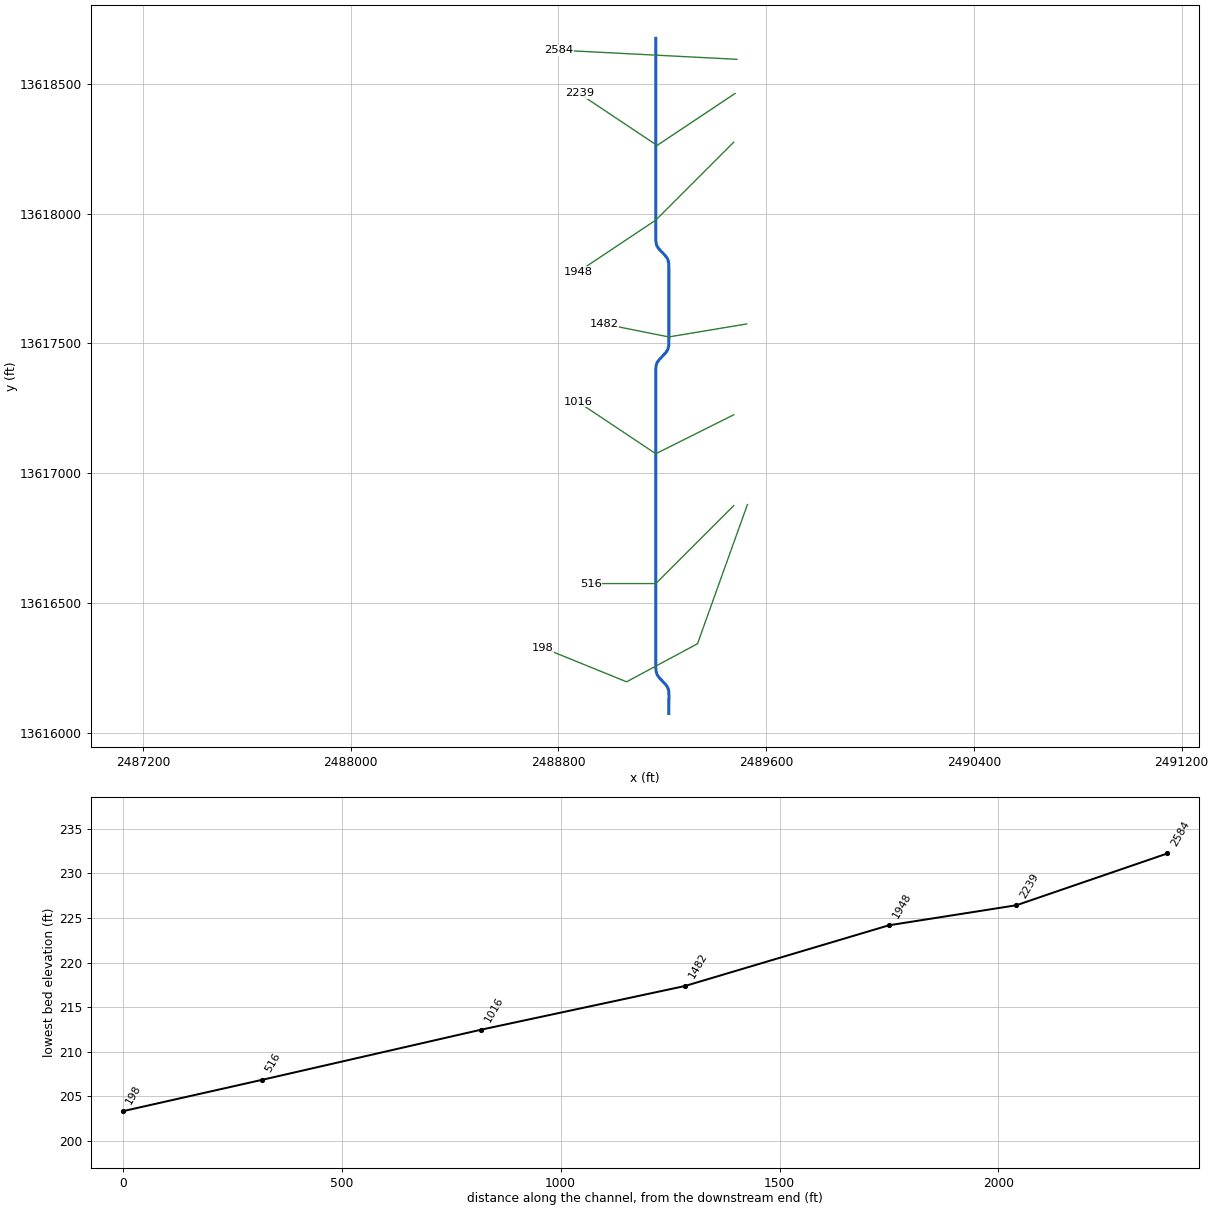
--- Stream0830.prj (project) ---

Proj Title=Stream0830 Base Level Engineering
Current Plan=p01
Default Exp/Contr=0.3,0.1
English Units
Geom File=g01
Flow File=f01
Plan File=p01
BEGIN DESCRIPTION:
Stream0830
END DESCRIPTION:

--- Stream0830.p01 (plan) ---

Plan Title=Multiple Run
Short Identifier=Multiple
Geom File=g01
Flow File=f01
Subcritical Flow
K Sum by GR= 0
Std Step Tol= 0.01
Critical Tol= 0.01
Num of Std Step Trials= 20
Max Error Tol= 0.3
Flow Tol Ratio= 0.001
Split Flow NTrial= 30
Split Flow Tol= 0.02
Split Flow Ratio= 0.02
Log Output Level= 0
Friction Slope Method= 1
Unsteady Friction Slope Method= 2
Unsteady Bridges Friction Slope Method= 1
Parabolic Critical Depth
Global Vel Dist=  1 , 1 , 1
Global Log Level= 0
CheckData=True
Encroach Param= -1, 0, 0, 0
BEGIN DESCRIPTION:
Multiple Run
END DESCRIPTION:

--- Stream0830.f01 (steady flow) ---

Flow Title=Multiple
Number of Profiles=7
Profile Names=10-year,25-year,50-year,1pct_min,100-year,1pct_plu,500-year
River Rch & RM= Stream0830,Reach-1,2584
     364     570     751     481     960    1915    1550
Boundary for River Rch & Prof#=Stream0830,Reach-1,1
Up Type=0
Dn Type=3
Dn Slope=0.005
Boundary for River Rch & Prof#=Stream0830,Reach-1,2
Up Type=0
Dn Type=3
Dn Slope=0.005
Boundary for River Rch & Prof#=Stream0830,Reach-1,3
Up Type=0
Dn Type=3
Dn Slope=0.005
Boundary for River Rch & Prof#=Stream0830,Reach-1,4
Up Type=0
Dn Type=3
Dn Slope=0.005
Boundary for River Rch & Prof#=Stream0830,Reach-1,5
Up Type=0
Dn Type=3
Dn Slope=0.005
Boundary for River Rch & Prof#=Stream0830,Reach-1,6
Up Type=0
Dn Type=3
Dn Slope=0.005
Boundary for River Rch & Prof#=Stream0830,Reach-1,7
Up Type=0
Dn Type=3
Dn Slope=0.005

--- Stream0830.g01 (geometry) ---

Geom Title=Existing Conditions

River Reach=Stream0830,Reach-1
Reach XY= 30
      2489175.00     13618675.00      2489174.80     13617899.92
      2489176.22     13617885.50      2489178.78     13617876.57
      2489180.75     13617872.67      2489188.79     13617861.86
      2489208.11     13617841.57      2489216.86     13617831.06
      2489221.22     13617823.43      2489224.48     13617809.78
      2489225.45     13617785.19      2489225.45     13617514.81
      2489224.48     13617490.22      2489221.22     13617476.57
      2489214.15     13617465.35      2489188.79     13617438.14
      2489180.75     13617427.33      2489178.78     13617423.43
      2489176.22     13617414.50      2489174.80     13617400.08
      2489174.64     13616254.85      2489176.20     13616235.50
      2489180.71     13616222.65      2489188.74     13616211.83
      2489214.14     13616184.64      2489219.32     13616177.36
      2489222.90     13616169.13      2489224.71     13616159.88
      2489225.63     13616145.26      2489225.00     13616075.00

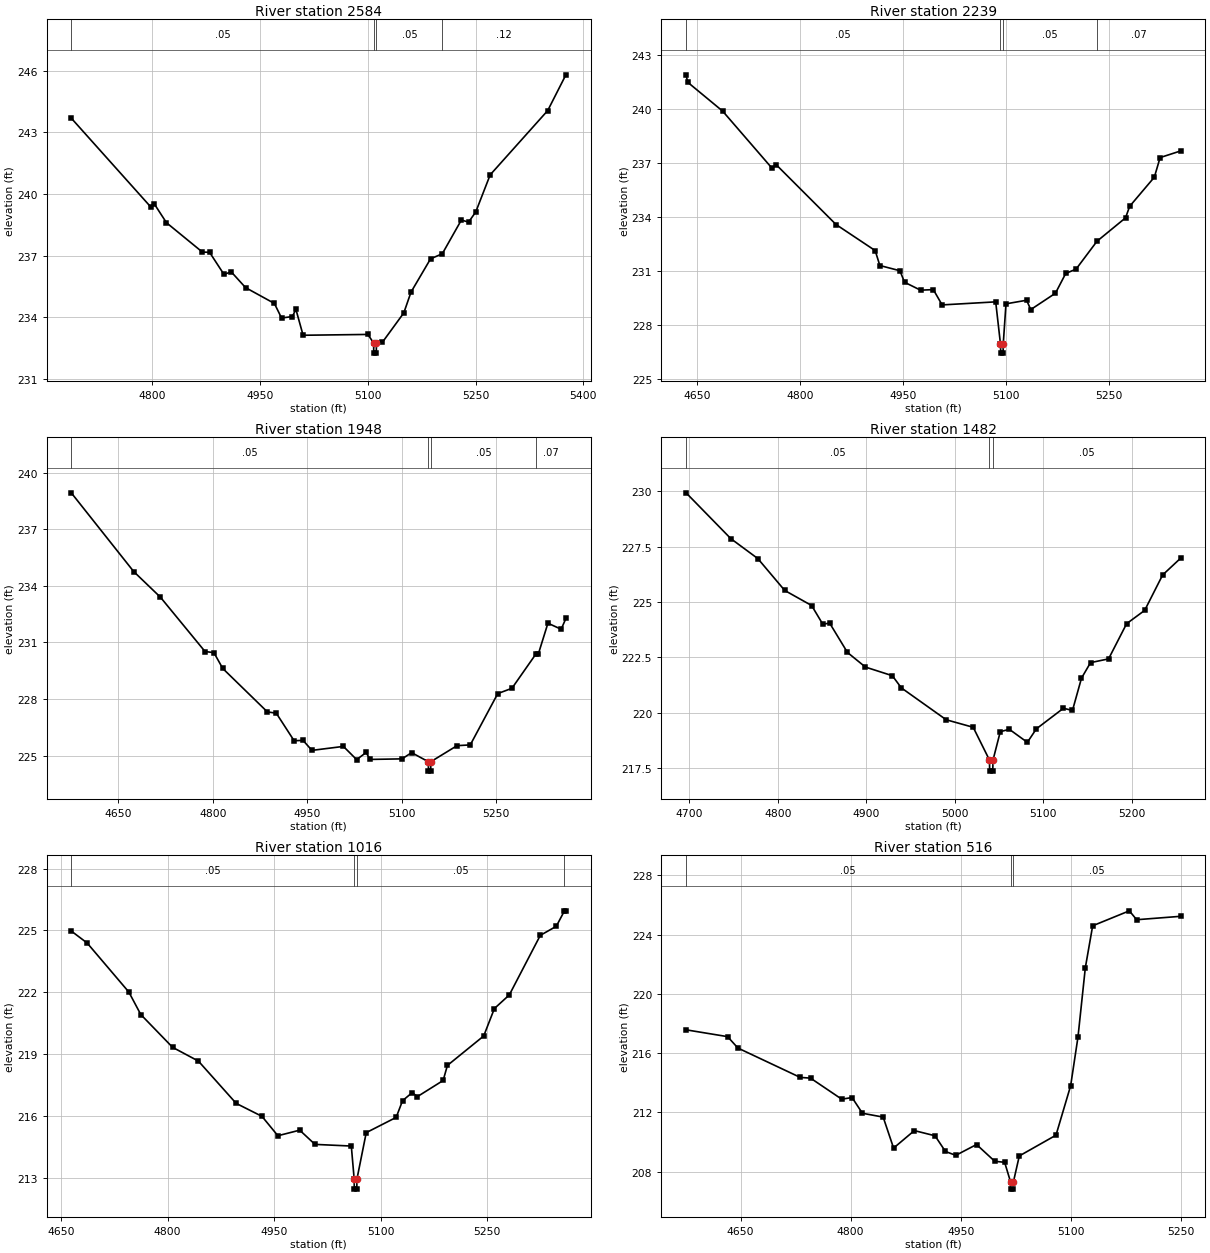
Type RM Length L Ch R = 1,2584,345,345,345
BEGIN DESCRIPTION:
XS7792
END DESCRIPTION:
XS GIS Cut Line= 2
      2489487.29     13618594.18      2488799.70     13618629.57
#Sta/Elev= 30
  4687.3  243.69  4797.6  239.38  4802.6  239.53  4819.8  238.60  4869.8  237.17
  4879.8  237.16  4899.9  236.08  4909.9  236.21  4929.9  235.44  4970.0  234.67
  4980.0  233.96  4995.0  234.03  5000.0  234.38  5010.0  233.12  5100.1  233.16
  5108.1  232.75  5108.4  232.25  5111.9  232.25  5112.1  232.75  5120.2  232.77
  5150.2  234.21  5160.2  235.22  5187.4  236.84  5203.8  237.09  5230.3  238.73
  5240.3  238.63  5250.3  239.12  5270.4  240.93  5350.5  244.06  5375.8  245.80
#Mann=4,-1,0
  4687.3    0.05       0  5108.1    0.05       0  5112.1    0.05       0
  5203.8    0.12       0
Bank Sta=5108.1,5112.1
Exp/Cntr=0.3,0.1

Type RM Length L Ch R = 1,2239,291,291,291
BEGIN DESCRIPTION:
Stream0830 5.0
END DESCRIPTION:
XS GIS Cut Line= 3
      2489480.02     13618462.53      2489180.06     13618262.55
      2488880.03     13618462.57
#Sta/Elev= 30
  4633.4  241.90  4635.7  241.49  4686.8  239.88  4758.9  236.70  4764.9  236.90
  4852.0  233.58  4909.1  232.13  4915.9  231.30  4945.2  231.01  4951.9  230.37
  4975.2  229.93  4993.9  229.96  5006.7  229.11  5084.8  229.28  5091.8  226.93
  5092.1  226.43  5095.6  226.43  5095.8  226.93  5099.8  229.17  5129.9  229.37
  5135.9  228.85  5171.9  229.76  5186.9  230.86  5202.0  231.10  5232.5  232.65
  5274.1  233.95  5280.1  234.59  5316.1  236.21  5324.5  237.30  5354.5  237.67
#Mann=4,-1,0
  4633.4    0.05       0  5091.8    0.05       0  5095.8    0.05       0
  5232.5    0.07       0
Bank Sta=5091.8,5095.8
Exp/Cntr=0.3,0.1

Type RM Length L Ch R = 1,1948,466,466,466
BEGIN DESCRIPTION:
Stream0830 4.0
END DESCRIPTION:
XS GIS Cut Line= 3
      2489475.02     13618275.02      2489175.00     13617975.00
      2488875.04     13617775.02
#Sta/Elev= 30
  4575.6  238.93  4674.6  234.76  4717.0  233.40  4787.8  230.52  4801.9  230.46
  4816.0  229.62  4886.7  227.32  4900.9  227.25  4929.2  225.79  4943.3  225.81
  4957.5  225.28  5007.4  225.49  5028.4  224.79  5043.5  225.17  5049.5  224.80
  5100.5  224.83  5115.6  225.16  5142.1  224.68  5142.4  224.18  5145.9  224.18
  5146.1  224.68  5187.7  225.53  5208.7  225.57  5252.3  228.29  5274.8  228.57
  5313.1  230.40  5316.9  230.41  5331.9  232.02  5352.9  231.70  5360.4  232.27
#Mann=4,-1,0
  4575.6    0.05       0  5142.1    0.05       0  5146.1    0.05       0
  5313.1    0.07       0
Bank Sta=5142.1,5146.1
Exp/Cntr=0.3,0.1

Type RM Length L Ch R = 1,1482,466,466,466
BEGIN DESCRIPTION:
Stream0830 3.0
END DESCRIPTION:
XS GIS Cut Line= 3
      2489524.95     13617574.99      2489225.00     13617525.00
      2488975.04     13617574.99
#Sta/Elev= 30
  4696.3  229.93  4746.9  227.86  4777.4  226.96  4807.8  225.52  4838.2  224.84
  4850.9  223.99  4858.5  224.05  4878.7  222.72  4899.0  222.06  4929.4  221.67
  4939.6  221.12  4990.3  219.68  5020.8  219.34  5039.2  217.86  5039.4  217.36
  5042.9  217.36  5043.2  217.86  5051.4  219.14  5061.6  219.25  5082.0  218.66
  5092.2  219.27  5122.8  220.20  5133.0  220.10  5143.2  221.56  5153.4  222.26
  5173.8  222.43  5194.2  224.02  5214.6  224.62  5234.9  226.22  5255.3  226.98
#Mann=3,-1,0
  4696.3    0.05       0  5039.2    0.05       0  5043.2    0.05       0
Bank Sta=5039.2,5043.2
Exp/Cntr=0.3,0.1

Type RM Length L Ch R = 1,1016,500,500,500
BEGIN DESCRIPTION:
Stream0830 2.0
END DESCRIPTION:
XS GIS Cut Line= 3
      2489474.98     13617224.99      2489175.00     13617075.00
      2488875.04     13617274.97
#Sta/Elev= 30
  4664.6  224.97  4686.9  224.39  4745.6  222.01  4762.4  220.92  4807.1  219.33
  4843.5  218.66  4896.6  216.61  4932.9  215.98  4955.3  215.04  4986.0  215.31
  5007.5  214.62  5058.6  214.54  5062.6  212.95  5062.8  212.45  5066.3  212.45
  5066.6  212.95  5079.6  215.19  5121.7  215.93  5130.7  216.74  5144.2  217.13
  5151.7  216.94  5187.8  217.72  5193.8  218.45  5244.9  219.88  5259.9  221.21
  5280.9  221.87  5324.5  224.76  5347.0  225.20  5358.5  225.95  5360.5  225.95
#Mann=4,-1,0
  4664.6    0.05       0  5062.6    0.05       0  5066.6    0.05       0
  5358.5    0.07       0
Bank Sta=5062.6,5066.6
Exp/Cntr=0.3,0.1

Type RM Length L Ch R = 1,516,318,318,318
BEGIN DESCRIPTION:
Stream0830 1.0
END DESCRIPTION:
XS GIS Cut Line= 3
      2489475.02     13616875.02      2489175.00     13616575.00
      2488925.00     13616575.00
#Sta/Elev= 30
  4575.7  217.57  4632.3  217.11  4646.4  216.34  4731.3  214.36  4745.4  214.31
  4787.9  212.89  4802.0  213.00  4816.1  211.94  4844.4  211.68  4858.6  209.59
  4886.9  210.77  4915.1  210.42  4929.3  209.36  4943.4  209.10  4971.7  209.83
  4996.5  208.70  5010.0  208.63  5018.0  207.32  5018.2  206.82  5021.7  206.82
  5022.0  207.32  5030.0  209.06  5080.0  210.46  5100.0  213.80  5110.0  217.09
  5120.0  221.76  5130.0  224.59  5180.0  225.60  5190.0  225.00  5250.0  225.23
#Mann=3,-1,0
  4575.7    0.05       0  5018.0    0.05       0  5022.0    0.05       0
Bank Sta=5018,5022
Exp/Cntr=0.3,0.1

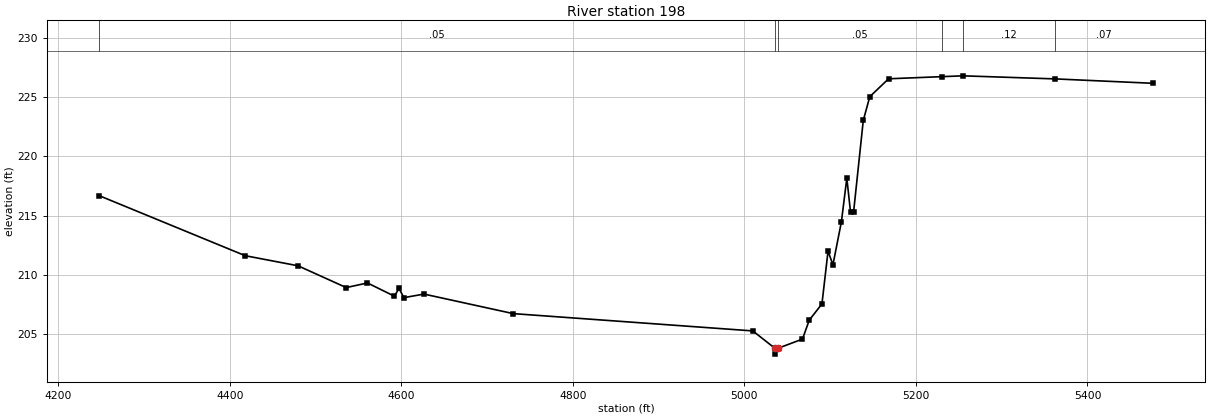
Type RM Length L Ch R = 1,198,0,0,0
BEGIN DESCRIPTION:
XS7791
END DESCRIPTION:
XS GIS Cut Line= 4
      2489527.80     13616879.46      2489335.58     13616343.27
      2489062.44     13616196.58      2488739.33     13616327.84
#Sta/Elev= 30
  4247.7  216.68  4418.0  211.61  4479.5  210.76  4535.7  208.92  4560.5  209.31
  4591.9  208.19  4597.2  208.85  4603.0  208.07  4626.4  208.37  4730.5  206.72
  5009.8  205.26  5035.4  203.80  5035.7  203.30  5039.4  203.80  5067.7  204.57
  5075.6  206.17  5090.4  207.54  5097.5  212.00  5103.2  210.84  5113.1  214.48
  5119.4  218.16  5123.7  215.31  5127.3  215.31  5138.6  223.04  5146.2  225.04
  5168.1  226.55  5230.2  226.73  5255.1  226.80  5362.5  226.54  5476.1  226.17
#Mann=6,-1,0
  4247.7    0.05       0  5035.4    0.05       0  5039.4    0.05       0
  5230.2    0.07       0  5255.1    0.12       0  5362.5    0.07       0
Bank Sta=5035.4,5039.4
Exp/Cntr=0.3,0.1

Chan Stop Cuts=-1