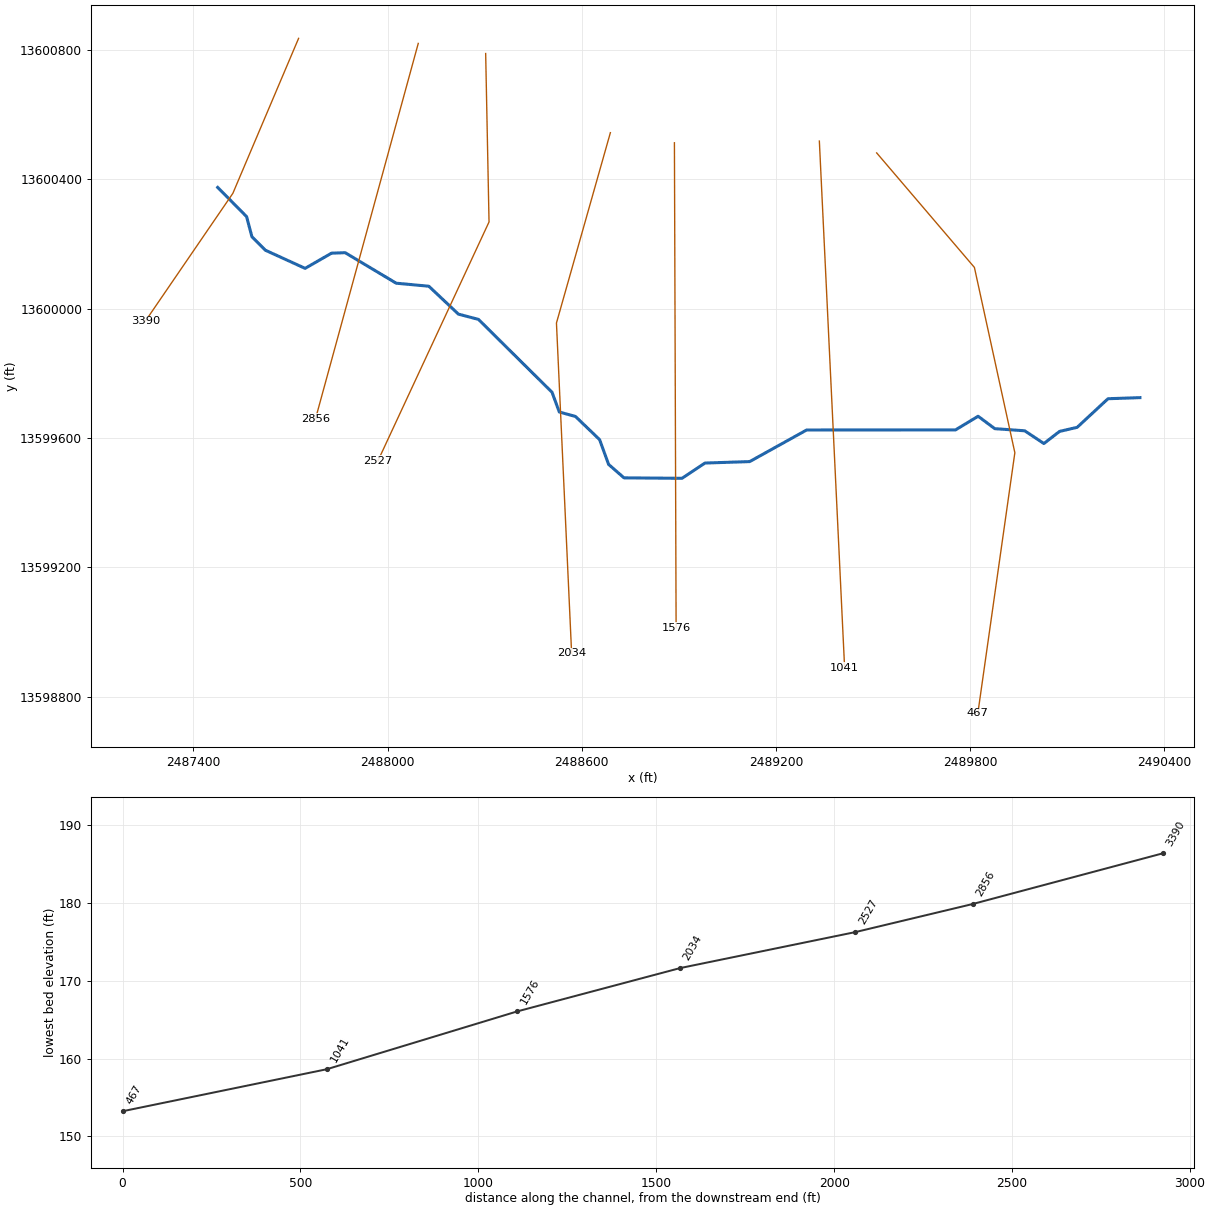
--- Stream0833.prj (project) ---

Proj Title=Stream0833 Base Level Engineering
Current Plan=p01
Default Exp/Contr=0.3,0.1
English Units
Geom File=g01
Flow File=f01
Plan File=p01
BEGIN DESCRIPTION:
Stream0833
END DESCRIPTION:

--- Stream0833.p01 (plan) ---

Plan Title=Multiple Run
Short Identifier=Multiple
Geom File=g01
Flow File=f01
Subcritical Flow
K Sum by GR= 0
Std Step Tol= 0.01
Critical Tol= 0.01
Num of Std Step Trials= 20
Max Error Tol= 0.3
Flow Tol Ratio= 0.001
Split Flow NTrial= 30
Split Flow Tol= 0.02
Split Flow Ratio= 0.02
Log Output Level= 0
Friction Slope Method= 1
Unsteady Friction Slope Method= 2
Unsteady Bridges Friction Slope Method= 1
Parabolic Critical Depth
Global Vel Dist=  1 , 1 , 1
Global Log Level= 0
CheckData=True
Encroach Param= -1, 0, 0, 0
BEGIN DESCRIPTION:
Multiple Run
END DESCRIPTION:

--- Stream0833.f01 (steady flow) ---

Flow Title=Multiple
Number of Profiles=7
Profile Names=10-year,25-year,50-year,1pct_min,100-year,1pct_plu,500-year
River Rch & RM= Stream0833,Reach-1,3390
     507     812    1086     705    1407    2808    2338
River Rch & RM= Stream0833,Reach-1,1576
     700    1144    1550    1018    2032    4054    3456
Boundary for River Rch & Prof#=Stream0833,Reach-1,1
Up Type=0
Dn Type=3
Dn Slope=0.005
Boundary for River Rch & Prof#=Stream0833,Reach-1,2
Up Type=0
Dn Type=3
Dn Slope=0.005
Boundary for River Rch & Prof#=Stream0833,Reach-1,3
Up Type=0
Dn Type=3
Dn Slope=0.005
Boundary for River Rch & Prof#=Stream0833,Reach-1,4
Up Type=0
Dn Type=3
Dn Slope=0.005
Boundary for River Rch & Prof#=Stream0833,Reach-1,5
Up Type=0
Dn Type=3
Dn Slope=0.005
Boundary for River Rch & Prof#=Stream0833,Reach-1,6
Up Type=0
Dn Type=3
Dn Slope=0.005
Boundary for River Rch & Prof#=Stream0833,Reach-1,7
Up Type=0
Dn Type=3
Dn Slope=0.005

--- Stream0833.g01 (geometry) ---

Geom Title=Existing Conditions

River Reach=Stream0833,Reach-1
Reach XY= 30
      2487475.00     13600375.00      2487564.28     13600284.69
      2487580.74     13600222.46      2487622.45     13600180.73
      2487745.18     13600124.71      2487826.72     13600171.60
      2487868.89     13600173.20      2488026.59     13600078.83
      2488127.42     13600069.46      2488218.96     13599983.18
      2488281.05     13599966.84      2488508.27     13599741.48
      2488530.62     13599680.62      2488580.77     13599666.72
      2488655.22     13599595.12      2488683.02     13599518.62
      2488730.67     13599476.98      2488909.78     13599475.52
      2488980.94     13599522.73      2489119.07     13599527.25
      2489295.03     13599624.94      2489755.02     13599625.18
      2489825.00     13599667.44      2489876.50     13599629.09
      2489969.10     13599622.45      2490028.32     13599583.04
      2490076.65     13599620.55      2490131.04     13599633.14
      2490226.41     13599721.61      2490325.00     13599725.00

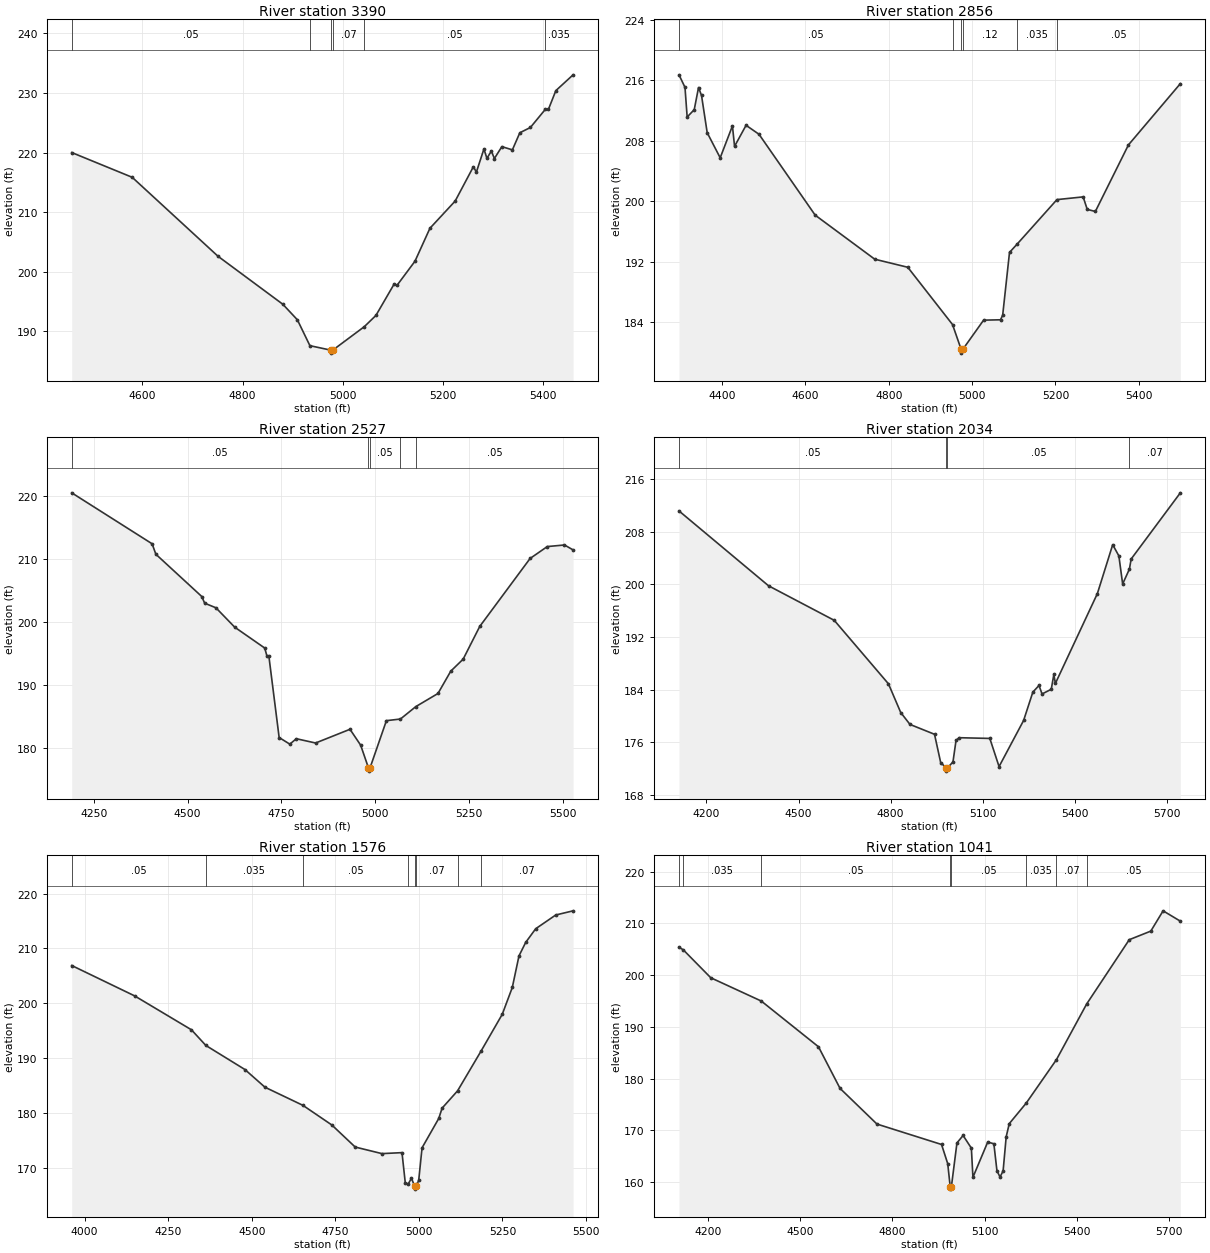
Type RM Length L Ch R = 1,3390,534,534,534
BEGIN DESCRIPTION:
XS7804
END DESCRIPTION:
XS GIS Cut Line= 3
      2487725.01     13600835.95      2487521.88     13600356.77
      2487251.03     13599960.92
#Sta/Elev= 30
  4459.1  220.00  4579.7  215.85  4750.9  202.61  4880.1  194.57  4909.2  191.96
  4934.2  187.62  4975.8  186.87  4976.1  186.37  4979.8  186.87  5042.8  190.81
  5065.9  192.69  5101.8  197.89  5107.9  197.73  5143.8  201.78  5173.6  207.30
  5224.0  211.87  5260.3  217.62  5266.3  216.72  5281.3  220.59  5287.3  219.04
  5296.2  220.24  5302.2  219.00  5317.1  220.99  5338.1  220.45  5353.0  223.32
  5374.0  224.20  5403.6  227.22  5409.9  227.22  5424.8  230.38  5459.2  233.03
#Mann=6,-1,0
  4459.1    0.05       0  4934.2    0.07       0  4975.8    0.05       0
  4979.8    0.07       0  5042.8    0.05       0  5403.6   0.035       0
Bank Sta=4975.8,4979.8
Exp/Cntr=0.3,0.1

Type RM Length L Ch R = 1,2856,329,329,329
BEGIN DESCRIPTION:
XS7803
END DESCRIPTION:
XS GIS Cut Line= 2
      2488094.78     13600820.27      2487777.24     13599659.42
#Sta/Elev= 30
  4296.4  216.75  4310.8  215.09  4316.0  211.16  4333.0  212.13  4343.3  215.07
  4350.5  214.01  4364.1  209.08  4395.3  205.75  4424.7  209.98  4429.8  207.27
  4457.4  210.06  4488.5  208.87  4623.3  198.15  4766.3  192.31  4845.6  191.24
  4953.0  183.65  4973.7  180.36  4974.0  179.86  4977.7  180.36  5027.6  184.23
  5068.2  184.28  5073.4  184.88  5089.8  193.21  5108.4  194.33  5203.7  200.21
  5266.6  200.57  5276.4  198.91  5295.9  198.64  5375.3  207.46  5499.9  215.58
#Mann=6,-1,0
  4296.4    0.05       0  4953.0    0.12       0  4973.7    0.05       0
  4977.7    0.12       0  5108.4   0.035       0  5203.7    0.05       0
Bank Sta=4973.7,4977.7
Exp/Cntr=0.3,0.1

Type RM Length L Ch R = 1,2527,493,493,493
BEGIN DESCRIPTION:
XS7802
END DESCRIPTION:
XS GIS Cut Line= 3
      2488303.13     13600789.02      2488313.54     13600268.23
      2487970.20     13599529.52
#Sta/Elev= 30
  4191.4  220.49  4405.5  212.39  4415.5  210.73  4537.8  204.01  4545.5  202.95
  4575.5  202.22  4625.5  199.14  4705.5  195.82  4711.4  194.55  4716.5  194.55
  4743.9  181.60  4772.3  180.55  4789.7  181.41  4841.0  180.73  4932.6  182.91
  4961.0  180.39  4981.9  176.76  4982.1  176.26  4985.9  176.76  5029.6  184.28
  5067.0  184.54  5108.1  186.52  5167.0  188.60  5201.1  192.15  5234.1  194.06
  5278.3  199.26  5412.4  210.06  5458.2  211.95  5504.0  212.20  5526.9  211.42
#Mann=5,-1,0
  4191.4    0.05       0  4981.9    0.05       0  4985.9    0.05       0
  5067.0   0.035       0  5108.1    0.05       0
Bank Sta=4981.9,4985.9
Exp/Cntr=0.3,0.1

Type RM Length L Ch R = 1,2034,458,458,458
BEGIN DESCRIPTION:
XS7801
END DESCRIPTION:
XS GIS Cut Line= 3
      2488688.54     13600544.26      2488521.88     13599955.73
      2488568.75     13598934.88
#Sta/Elev= 30
  4110.4  211.18  4402.2  199.80  4616.3  194.55  4792.9  184.90  4832.9  180.54
  4863.0  178.73  4943.0  177.23  4963.1  172.93  4981.1  172.13  4981.3  171.63
  4985.1  172.13  5003.1  173.02  5013.1  176.29  5023.1  176.71  5123.2  176.60
  5153.3  172.32  5233.3  179.33  5263.4  183.64  5283.4  184.65  5293.4  183.36
  5323.4  184.07  5331.8  186.32  5336.8  184.96  5473.6  198.61  5523.6  206.05
  5543.7  204.34  5556.0  200.08  5578.1  202.34  5583.7  203.87  5744.0  213.93
#Mann=4,-1,0
  4110.4    0.05       0  4981.1    0.05       0  4985.1    0.05       0
  5578.1    0.07       0
Bank Sta=4981.1,4985.1
Exp/Cntr=0.3,0.1

Type RM Length L Ch R = 1,1576,535,535,535
BEGIN DESCRIPTION:
XS7800
END DESCRIPTION:
XS GIS Cut Line= 2
      2488886.46     13600513.06      2488891.67     13599013.07
#Sta/Elev= 30
  3961.5  206.87  4149.6  201.33  4319.6  195.14  4362.8  192.28  4479.6  187.89
  4539.6  184.66  4653.2  181.35  4739.6  177.77  4809.6  173.74  4889.6  172.54
  4949.6  172.72  4959.6  167.10  4968.7  167.06  4978.0  168.05  4987.6  166.56
  4987.8  166.06  4991.6  166.56  4999.6  167.65  5009.6  173.60  5059.6  178.96
  5069.6  180.84  5115.9  184.00  5186.7  191.31  5249.6  197.97  5279.6  202.86
  5299.6  208.62  5319.6  211.08  5349.6  213.58  5409.6  216.09  5461.5  216.85
#Mann=8,-1,0
  3961.5    0.05       0  4362.8   0.035       0  4653.2    0.05       0
  4968.7    0.07       0  4987.6    0.05       0  4991.6    0.07       0
  5115.9    0.05       0  5186.7    0.07       0
Bank Sta=4987.6,4991.6
Exp/Cntr=0.3,0.1

Type RM Length L Ch R = 1,1041,574,574,574
BEGIN DESCRIPTION:
XS7799
END DESCRIPTION:
XS GIS Cut Line= 2
      2489334.37     13600518.25      2489412.45     13598889.02
#Sta/Elev= 30
  4105.8  205.39  4119.6  204.90  4209.2  199.49  4373.5  194.99  4559.6  186.15
  4629.7  178.11  4749.8  171.21  4960.0  167.26  4980.1  163.55  4988.1  159.13
  4988.3  158.63  4992.1  159.13  5010.1  167.56  5030.1  169.00  5057.0  166.55
  5062.1  160.92  5110.2  167.73  5130.2  167.40  5140.2  162.20  5150.2  160.97
  5160.3  162.15  5170.3  168.75  5180.3  171.29  5235.2  175.24  5333.7  183.65
  5432.2  194.43  5570.7  206.85  5640.8  208.51  5680.8  212.43  5736.9  210.43
#Mann=8,-1,0
  4105.8    0.05       0  4119.6   0.035       0  4373.5    0.05       0
  4988.1    0.05       0  4992.1    0.05       0  5235.2   0.035       0
  5333.7    0.07       0  5432.2    0.05       0
Bank Sta=4988.1,4992.1
Exp/Cntr=0.3,0.1

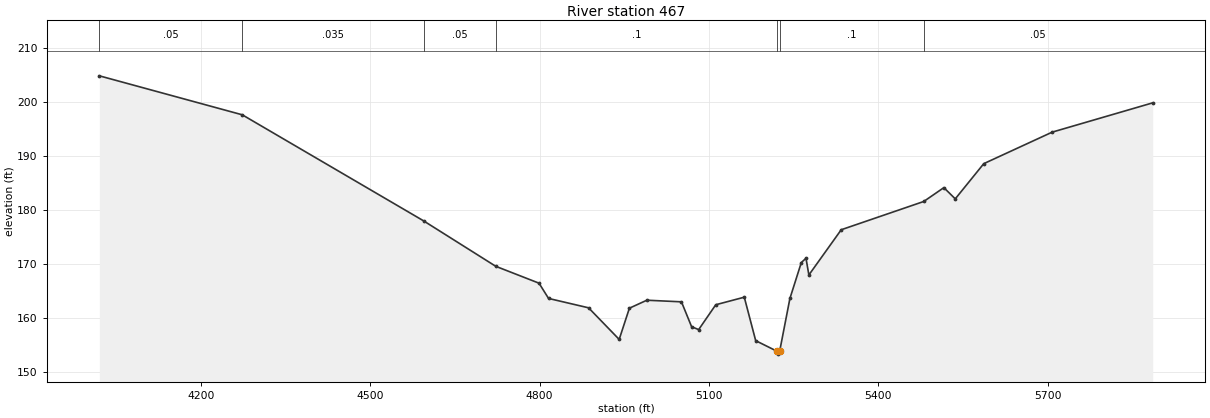
Type RM Length L Ch R = 1,467,0,0,0
BEGIN DESCRIPTION:
XS7798
END DESCRIPTION:
XS GIS Cut Line= 4
      2489511.48     13600481.74      2489813.54     13600127.60
      2489938.54     13599554.69      2489824.15     13598748.72
#Sta/Elev= 30
  4020.1  204.85  4273.3  197.62  4594.3  177.96  4722.3  169.52  4798.9  166.39
  4815.8  163.56  4886.7  161.82  4940.9  155.96  4959.0  161.75  4989.9  163.23
  5051.2  162.93  5069.2  158.31  5081.7  157.78  5112.0  162.39  5162.5  163.79
  5182.7  155.73  5221.1  153.73  5221.4  153.23  5225.1  153.73  5243.3  163.55
  5263.5  170.21  5271.8  171.02  5276.9  167.91  5334.2  176.30  5480.3  181.54
  5516.0  184.11  5536.2  182.03  5586.7  188.56  5708.0  194.41  5886.0  199.84
#Mann=7,-1,0
  4020.1    0.05       0  4273.3   0.035       0  4594.3    0.05       0
  4722.3     0.1       0  5221.1    0.05       0  5225.1     0.1       0
  5480.3    0.05       0
Bank Sta=5221.1,5225.1
Exp/Cntr=0.3,0.1

Chan Stop Cuts=-1