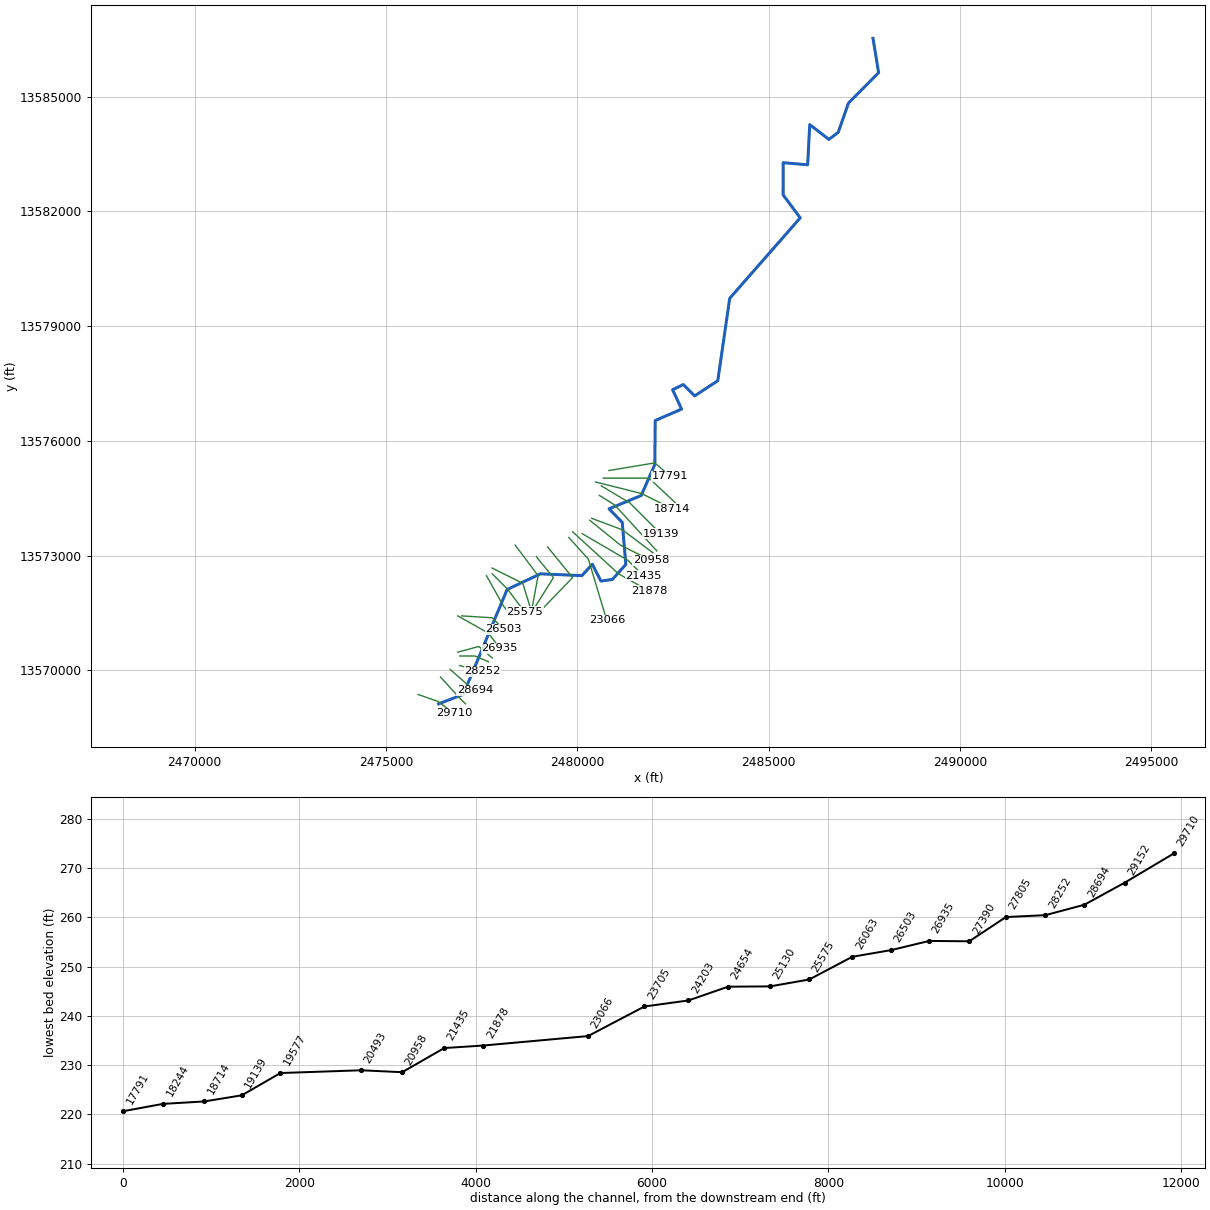
--- Stream0834.prj (project) ---

Proj Title=Stream0834 Base Level Engineering
Current Plan=p01
Default Exp/Contr=0.3,0.1
English Units
Geom File=g01
Flow File=f01
Plan File=p01
Y Axis Title=Elevation
X Axis Title(PF)=Main Channel Distance
X Axis Title(XS)=Station
BEGIN DESCRIPTION:
Stream0834
END DESCRIPTION:
DSS Export Rating Curves= 0
DSS Export Rating Curve Sorted= 0
DSS Export Volume Flow Curves= 0
DXF OffsetX= 0
DXF OffsetY= 0
DXF ScaleX= 1
DXF ScaleY= 10

--- Stream0834.p01 (plan) ---

Plan Title=Multiple Run
Program Version=4.10
Short Identifier=Multiple
Geom File=g01
Flow File=f01
Subcritical Flow
K Sum by GR= 0
Std Step Tol= 0.01
Critical Tol= 0.01
Num of Std Step Trials= 20
Max Error Tol= 0.3
Flow Tol Ratio= 0.001
Split Flow NTrial= 30
Split Flow Tol= 0.02
Split Flow Ratio= 0.02
Log Output Level= 0
Friction Slope Method= 1
Unsteady Friction Slope Method= 2
Unsteady Bridges Friction Slope Method= 1
Parabolic Critical Depth
Global Vel Dist= 1 , 1 , 1
Global Log Level= 0
CheckData=True
Encroach Param=-1 ,0,0, 0
BEGIN DESCRIPTION:
Multiple Run
END DESCRIPTION:
Computation Interval=1HOUR
Output Interval=1HOUR
Run HTab= 0
Run UNet= 0
Run PostProcess= 0
Run WQNet= 0
UNET Theta= 1
UNET Theta Warmup= 1
UNET ZTol= 0.02
UNET ZSATol= 0.05
UNET MxIter= 20
UNET MaxInSteps= 0
UNET DtIC= 0
UNET DtMin= 0
UNET MaxCRTS= 20
UNET WFStab= 2
UNET SFStab= 1
UNET WFX= 1
UNET SFX= 1
UNET DSS MLevel= 4
UNET DZMax Abort= 100
UNET Convert EG Bridges= 0
UNET Use Existing IB Tables=-1
UNET Froude Reduction=False
UNET Froude Limit= 1
UNET Froude Power= 10
UNET Time Slicing=0,0, 5
UNET Junction Losses=0
Instantaneous Interval=1HOUR
Write IC File= 0
Write IC File at Sim End=0
Echo Input=False
Echo Parameters=False
Echo Output=False
Write Detailed= 0
WQ AD Non Conservative
WQ ULTIMATE=-1
WQ Max Comp Step=1HOUR
WQ Output Interval=15MIN
WQ Output Selected Increments= 0
WQ Output face flow=0
WQ Output face velocity=0
WQ Output face area=0
WQ Output face dispersion=0
WQ Output cell volume=0
WQ Output cell surface area=0
WQ Output cell continuity=0
WQ Output cumulative cell continuity=0
WQ Output face conc=0
WQ Output face dconc_dx=0
WQ Output face courant=0
WQ Output face peclet=0
WQ Output face adv mass=0
WQ Output face disp mass=0
WQ Output cell mass=0
WQ Output cell source sink temp=0
WQ Output cell source sink nsm=0
WQ Output MaxMinRange=-1
WQ Daily Max Min Mean=-1
WQ Daily Range=0
WQ Daily Time=0
WQ Create Restart=0
WQ Fixed Restart=0
WQ System Summary=0
WQ Use Fixed Temperature=0
Sorting and Armoring Iterations= 10
XS Update Threshold= 0.02
Hydraulics Update Threshold= 0.02
Energy Slope Method= 1
Volume Change Method= 0
XS Weighting Method= 0
Number of US Weighted Cross Sections= 1
Number of DS Weighted Cross Sections= 1
Upstream XS Weight=0.25
Main XS Weight=0.5
Downstream XS Weight=0.25
Number of DS XS's Weighted with US Boundary= 1
Upstream Boundary Weight= 1
Weight of XSs Associated with US Boundary= 0
Number of US XS's Weighted with DS Boundary= 1
Downstream Boundary Weight= 0.5
Weight of XSs Associated with DS Boundary= 0.5
Sediment Output Level= 4
Mass or Volume Output= 0
Output Increment Type= 1
Profile and TS Output Increment= 10
XS Output Flag= 0
XS Output Increment= 10
Disregard all LS=0
Disregard all Conn=0
Disregard all Breaches=0
Disregard all Pumps=0

--- Stream0834.f01 (steady flow) ---

Flow Title=Multiple
Number of Profiles=7
Profile Names=10-year,25-year,50-year,1pct_min,100-year,1pct_plu,500-year
River Rch & RM= Stream0834,Reach-1,29710
     773    1267    1722    1133    2261    4512    3864
River Rch & RM= Stream0834,Reach-1,28694
    1067    1773    2429    1610    3212    6408    5563
River Rch & RM= Stream0834,Reach-1,21878
    1808    3062    4247    2842    5671   11316   10028
River Rch & RM= Stream0834,Reach-1,12193
    2863    4927    6909    4667    9311   18578   16773
River Rch & RM= Stream0834,Reach-1,8654
    3092    5339    7503    5080   10135   20222   18338
River Rch & RM= Stream0834,Reach-1,6694
    3082    5296    7417    5002    9980   19912   17918
River Rch & RM= Stream0834,Reach-1,578
    3031    5197    7269    4895    9767   19488   17486
Boundary for River Rch & Prof#=Stream0834,Reach-1,1
Up Type=0
Dn Type=3
Dn Slope=0.005
Boundary for River Rch & Prof#=Stream0834,Reach-1,2
Up Type=0
Dn Type=3
Dn Slope=0.005
Boundary for River Rch & Prof#=Stream0834,Reach-1,3
Up Type=0
Dn Type=3
Dn Slope=0.005
Boundary for River Rch & Prof#=Stream0834,Reach-1,4
Up Type=0
Dn Type=3
Dn Slope=0.005
Boundary for River Rch & Prof#=Stream0834,Reach-1,5
Up Type=0
Dn Type=3
Dn Slope=0.005
Boundary for River Rch & Prof#=Stream0834,Reach-1,6
Up Type=0
Dn Type=3
Dn Slope=0.005
Boundary for River Rch & Prof#=Stream0834,Reach-1,7
Up Type=0
Dn Type=3
Dn Slope=0.005

--- Stream0834.g01 (geometry) ---

Geom Title=Existing Conditions
Program Version=4.10

River Reach=Stream0834      ,Reach-1
Reach XY= 30
        2476375.       13569125.      2477019.55     13569372.53
      2478164.82     13572114.68      2479035.68     13572524.25
      2480119.07     13572477.24      2480390.36     13572775.11
      2480615.31     13572335.18      2480914.59     13572375.99
      2481266.84     13572768.95      2481172.94     13573869.15
      2480828.08     13574223.34      2481669.17      13574572.7
       2482024.3      13575385.7      2482034.41     13576531.62
      2482723.04     13576830.89      2482488.34     13577338.31
      2482769.14     13577472.95      2483064.36     13577175.55
      2483669.17      13577572.7      2483980.83      13579727.3
      2485822.95     13581830.84      2485377.05     13582430.86
       2485378.1     13583273.82      2486017.25     13583218.45
      2486072.33     13584269.71      2486571.67     13583882.59
      2486817.25     13584068.55      2487082.81     13584831.19
      2487871.47     13585626.46        2487725.       13586525.

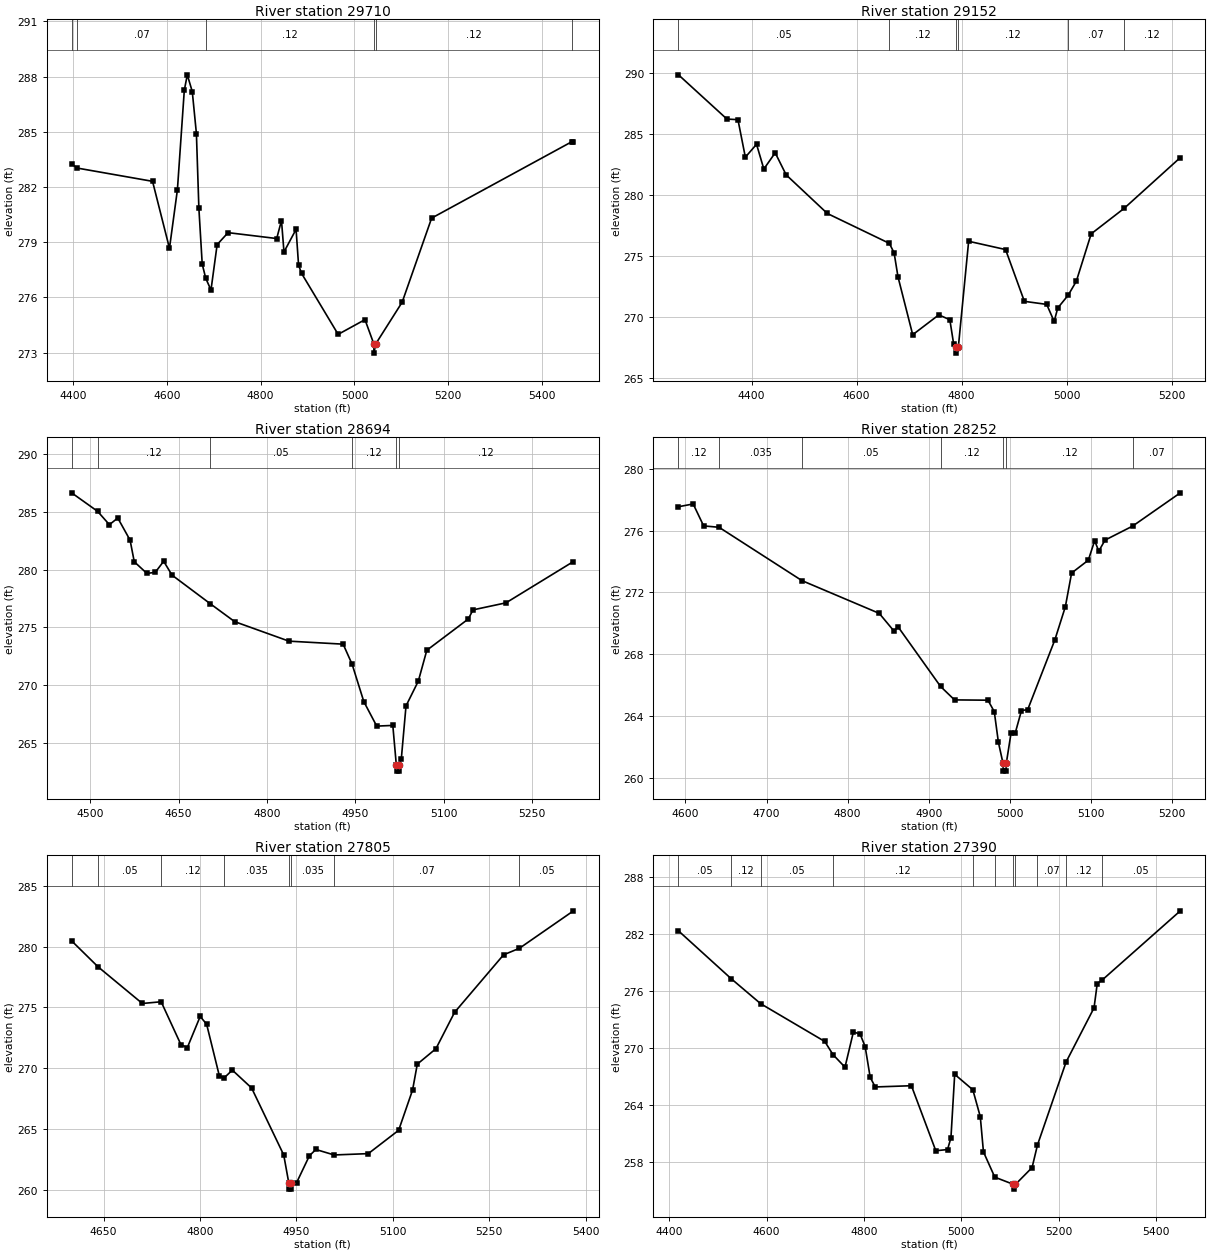
Type RM Length L Ch R = 1 ,29710   ,558,558,558
BEGIN DESCRIPTION:
Stream0834 51.0
END DESCRIPTION:
XS GIS Cut Line= 3
      2475842.03     13569368.49      2476353.59     13569190.69
      2476777.74     13568875.69
#Sta/Elev= 30
    4397  283.25  4409.1  283.03  4569.5  282.31  4605.6  278.67  4622.5  281.85
  4637.2  287.26  4643.6   288.1  4654.2  287.19    4663  284.91  4668.3  280.84
  4675.4  277.81  4682.9  277.04  4694.1   276.4  4707.2  278.87  4730.5  279.52
  4834.2   279.2  4844.4  280.18  4849.7  278.47  4875.5   279.7  4880.8  277.76
  4887.1  277.31  4965.2  273.99  5022.4  274.79  5041.3  273.47  5041.5  272.97
  5045.3  273.47  5101.7  275.74  5164.5  280.31  5463.9  284.47  5466.9  284.47
#Mann= 6 ,-1 , 0
    4397     .12       0  4409.1     .07       0  4682.9     .12       0
  5041.3     .05       0  5045.3     .12       0  5463.9     .07       0
Bank Sta=5041.3,5045.3
XS Rating Curve= 0 ,0
Exp/Cntr=0.3,0.1

Type RM Length L Ch R = 1 ,29152   ,458,458,458
BEGIN DESCRIPTION:
Stream0834 50.0
END DESCRIPTION:
XS GIS Cut Line= 3
      2476425.02     13569824.97        2476925.       13569275.
        2477075.       13569125.
#Sta/Elev= 30
  4260.9  289.87  4353.1  286.24  4374.1  286.19  4388.2  283.11  4409.5  284.17
  4423.4  282.14    4445  283.47  4465.9  281.66  4544.3  278.49  4662.3  276.04
  4671.4  275.26  4678.8  273.29  4706.8  268.54  4756.5  270.17  4777.5  269.77
  4784.9  267.74  4789.7  267.53  4789.9  267.03  4793.7  267.53  4813.3  276.21
  4883.6  275.53  4919.4  271.28  4961.9  271.03  4976.1  269.63  4982.9  270.73
  5002.9  271.79  5018.3  272.93  5046.6  276.82  5109.3  278.91  5216.3  283.08
#Mann= 6 ,-1 , 0
  4260.9     .05       0  4662.3     .12       0  4789.7     .05       0
  4793.7     .12       0  5002.9     .07       0  5109.3     .12       0
Bank Sta=4789.7,4793.7
XS Rating Curve= 0 ,0
Exp/Cntr=0.3,0.1

Type RM Length L Ch R = 1 ,28694   ,442,442,442
BEGIN DESCRIPTION:
Stream0834 49.0
END DESCRIPTION:
XS GIS Cut Line= 3
      2476674.98     13570025.01        2477075.       13569675.
      2477325.01     13569474.99
#Sta/Elev= 30
  4468.5  286.66  4512.5  285.06  4532.6   283.9  4546.8  284.48  4567.7  282.56
  4574.8  280.69  4596.2  279.68  4610.4  279.77  4624.7  280.73  4638.9  279.53
  4704.1  277.04  4745.2   275.5  4837.3  273.81  4929.3  273.55  4944.6   271.8
  4964.4  268.57  4986.3  266.45  5013.6  266.51  5019.6  263.05  5019.9  262.55
  5023.4  262.55  5023.6  263.05    5028   263.6    5036   268.2  5056.9  270.35
  5071.3  273.02  5141.7  275.73  5149.7  276.52  5205.7  277.13  5320.2  280.71
#Mann= 6 ,-1 , 0
  4468.5     .05       0  4512.5     .12       0  4704.1     .05       0
  4944.6     .12       0  5019.6     .05       0  5023.6     .12       0
Bank Sta=5019.6,5023.6
XS Rating Curve= 0 ,0
Exp/Cntr=0.3,0.1

Type RM Length L Ch R = 1 ,28252   ,447,447,447
BEGIN DESCRIPTION:
Stream0834 48.0
END DESCRIPTION:
XS GIS Cut Line= 3
      2476924.96     13570125.01        2477325.       13570025.
      2477524.99       13569975.
#Sta/Elev= 30
  4591.5  277.55  4609.6  277.73  4622.5  276.31  4641.5  276.22  4743.6  272.77
  4838.9  270.65    4857  269.51  4862.1  269.78  4914.5  265.92  4931.7  265.05
  4972.9  265.03  4980.7  264.29  4985.8   262.3  4991.5  260.94  4991.8  260.44
  4995.3  260.44  4995.5  260.94  5001.3  262.88  5006.4  262.88  5014.2  264.36
  5021.9  264.42  5055.4  268.94  5068.3  271.08    5076  273.26  5096.6  274.09
  5104.4  275.35  5109.5  274.68  5117.2  275.39  5151.3   276.3    5210  278.45
#Mann= 7 ,-1 , 0
  4591.5     .12       0  4641.5    .035       0  4743.6     .05       0
  4914.5     .12       0  4991.5     .05       0  4995.5     .12       0
  5151.3     .07       0
Bank Sta=4991.5,4995.5
XS Rating Curve= 0 ,0
Exp/Cntr=0.3,0.1

Type RM Length L Ch R = 1 ,27805   ,415,415,415
BEGIN DESCRIPTION:
Stream0834 47.0
END DESCRIPTION:
XS GIS Cut Line= 3
      2476925.03       13570375.        2477325.       13570375.
      2477675.04     13570224.98
#Sta/Elev= 30
  4600.4  280.48  4641.4  278.35  4710.4  275.33  4739.7  275.47  4770.4  271.95
  4780.4   271.7  4800.4  274.26  4810.4  273.63  4830.4  269.34  4838.1  269.23
  4850.4  269.85  4880.4  268.38  4930.4  262.87  4938.3  260.56  4938.6  260.06
  4942.1  260.06  4942.4  260.56  4950.4  260.59  4970.4  262.81  4980.4  263.32
  5008.9  262.87    5062  262.98  5109.2   264.9  5130.9  268.22  5138.2  270.34
  5167.2  271.61  5196.2   274.6  5272.4  279.33  5297.1  279.87  5381.2  282.95
#Mann= 8 ,-1 , 0
  4600.4     .12       0  4641.4     .05       0  4739.7     .12       0
  4838.1    .035       0  4938.3    .035       0  4942.4    .035       0
  5008.9     .07       0  5297.1     .05       0
Bank Sta=4938.3,4942.4
XS Rating Curve= 0 ,0
Exp/Cntr=0.3,0.1

Type RM Length L Ch R = 1 ,27390   ,455,455,455
BEGIN DESCRIPTION:
Stream0834 46.0
END DESCRIPTION:
XS GIS Cut Line= 3
      2476874.97     13570474.99        2477425.       13570625.
        2477775.       13570325.
#Sta/Elev= 30
    4419  282.34  4527.1  277.31  4587.8  274.67  4719.6  270.69  4736.4  269.31
  4761.1  267.98  4778.4   271.7  4792.2  271.46  4802.5  270.16  4812.9  266.91
  4823.3   265.9  4897.6  266.03  4947.7  259.18  4971.8  259.31  4978.8  260.55
  4986.5  267.23  5023.8   265.6  5039.1  262.77  5045.6  259.06  5068.9   256.4
  5107.3  255.64  5107.5  255.14  5111.4  255.64  5145.5  257.41  5156.6  259.79
  5215.4  268.53  5272.8  274.23  5279.4  276.79  5289.3  277.15  5450.1  284.45
#Mann= 11 ,-1 , 0
    4419     .05       0  4527.1     .12       0  4587.8     .05       0
  4736.4     .12       0  5023.8    .035       0  5068.9     .12       0
  5107.3     .05       0  5111.4     .12       0  5156.6     .07       0
  5215.4     .12       0  5289.3     .05       0
Bank Sta=5107.3,5111.4
XS Rating Curve= 0 ,0
Exp/Cntr=0.3,0.1

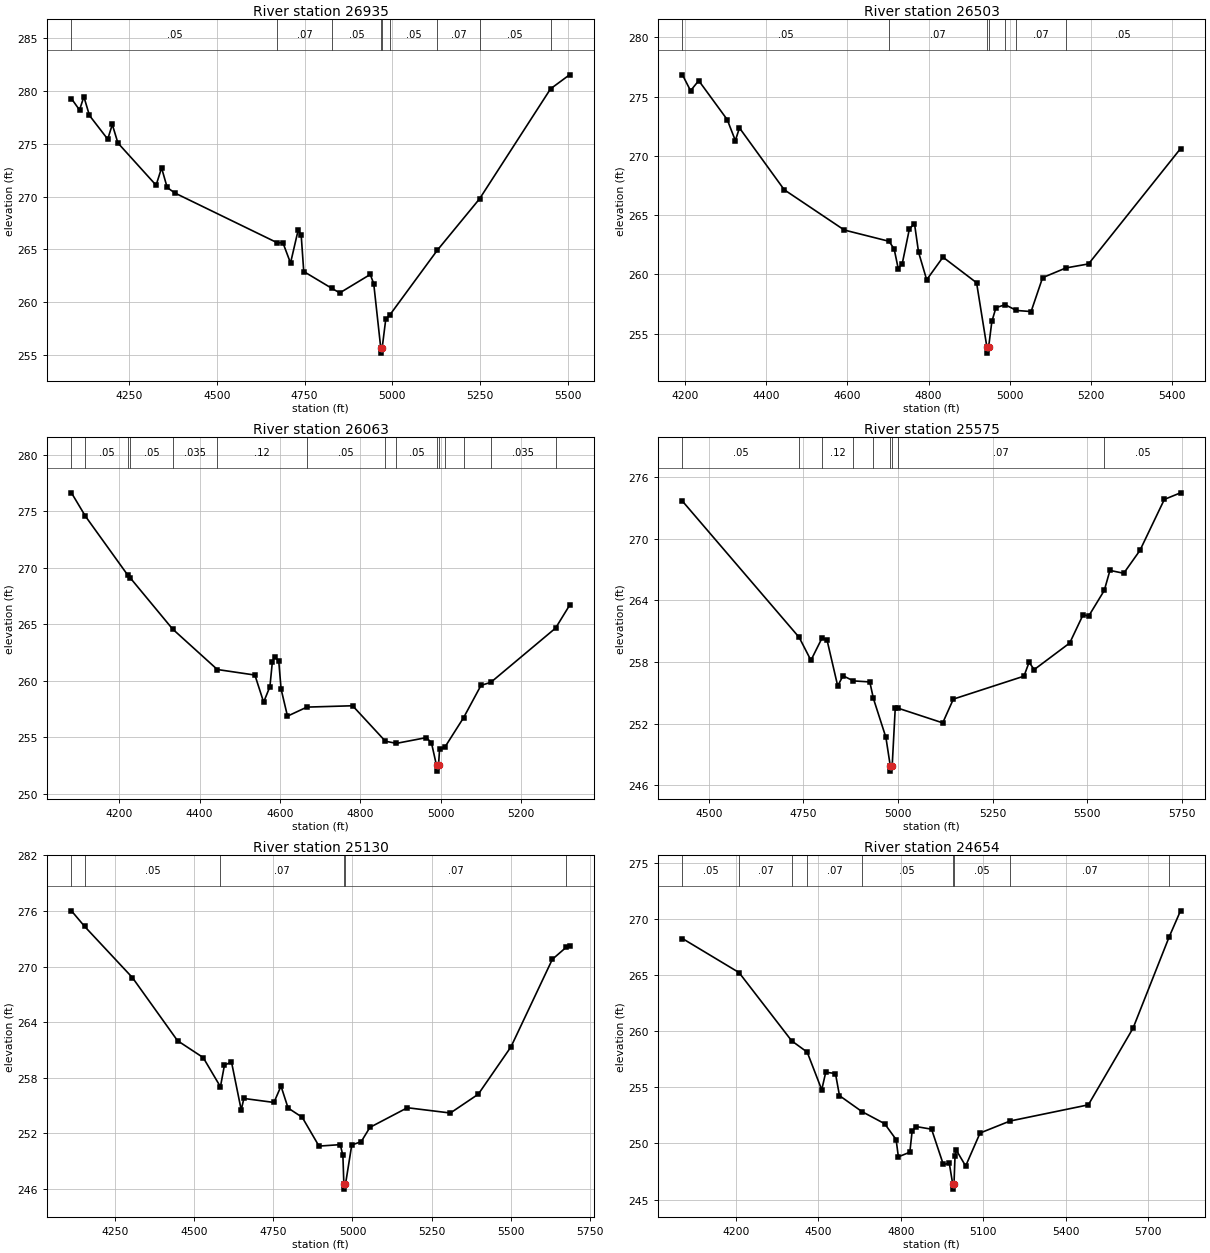
Type RM Length L Ch R = 1 ,26935   ,432,432,432
BEGIN DESCRIPTION:
Stream0834 45.0
END DESCRIPTION:
XS GIS Cut Line= 3
      2476874.99       13571425.        2477675.       13570975.
      2477975.01     13570574.99
#Sta/Elev= 30
  4086.5  279.25  4109.5  278.18  4121.9  279.43  4137.8  277.66  4189.8  275.42
  4202.8  276.81  4218.8  275.06  4327.5  271.07  4343.1  272.71    4359  270.86
  4380.7  270.34  4672.7  265.63  4688.5  265.64  4710.2  263.72  4731.9  266.83
  4740.5  266.37  4747.8  262.92  4828.3  261.32  4850.4   260.9  4937.1  262.64
    4947  261.78    4967  255.71  4967.2  255.21  4971.1  255.71  4981.4  258.44
  4993.4  258.84  5127.8  264.92  5248.4  269.79  5450.5  280.18  5504.4   281.5
#Mann= 9 ,-1 , 0
  4086.5     .05       0  4672.7     .07       0  4828.3     .05       0
    4967     .05       0  4971.1     .05       0  4993.4     .05       0
  5127.8     .07       0  5248.4     .05       0  5450.5    .035       0
Bank Sta=4967,4971.1
XS Rating Curve= 0 ,0
Exp/Cntr=0.3,0.1

Type RM Length L Ch R = 1 ,26503   ,440,440,440
BEGIN DESCRIPTION:
Stream0834 44.0
END DESCRIPTION:
XS GIS Cut Line= 3
      2476975.02       13571425.        2477775.       13571375.
        2478075.       13571075.
#Sta/Elev= 30
  4194.2  276.84  4214.2   275.5  4234.3  276.35  4304.4  273.06  4324.4  271.29
  4334.5  272.36  4444.7  267.14  4592.5  263.74  4702.5  262.79  4715.2  262.15
  4725.2  260.49  4735.2  260.91  4752.8  263.84  4765.3  264.28  4775.3  261.87
  4795.3  259.54  4835.4  261.45  4918.1  259.29  4943.5  253.85  4943.8  253.35
  4947.7  253.85  4955.7  256.02  4965.7  257.18  4988.4  257.44  5016.2  256.95
  5052.3  256.86  5080.6  259.72    5138  260.54  5193.7  260.88    5420  270.61
#Mann= 7 ,-1 , 0
  4194.2     .05       0  4702.5     .07       0  4943.5     .05       0
  4947.7     .07       0  4988.4     .05       0  5016.2     .07       0
    5138     .05       0
Bank Sta=4943.5,4947.7
XS Rating Curve= 0 ,0
Exp/Cntr=0.3,0.1

Type RM Length L Ch R = 1 ,26063   ,488,488,488
BEGIN DESCRIPTION:
Stream0834 43.0
END DESCRIPTION:
XS GIS Cut Line= 3
      2477625.01     13572474.97        2478075.       13571675.
        2478275.       13571425.
#Sta/Elev= 30
  4081.7  276.65  4116.6  274.57  4221.7  269.36  4228.2   269.1    4333  264.59
  4444.3     261  4537.7  260.51  4559.4  258.11    4575  259.48  4581.1  261.68
  4586.8  262.13    4597  261.73  4602.8  259.27  4618.7  256.87  4666.9  257.67
  4780.6  257.79    4862  254.65  4889.4  254.46  4964.2  254.97  4976.6   254.5
  4989.1   252.5  4989.5     252  4994.1   252.5  4996.7  253.94  5009.5   254.1
  5056.5  256.74  5099.6  259.59  5124.3  259.87  5285.1  264.67  5319.7  266.68
#Mann= 15 ,-1 , 0
  4081.7     .07       0  4116.6     .05       0  4221.7     .07       0
  4228.2     .05       0    4333    .035       0  4444.3     .12       0
  4666.9     .05       0    4862     .07       0  4889.4     .05       0
  4989.1     .05       0  4994.1     .05       0  5009.5     .07       0
  5056.5     .05       0  5124.3    .035       0  5285.1     .05       0
Bank Sta=4989.1,4994.1
XS Rating Curve= 0 ,0
Exp/Cntr=0.3,0.1

Type RM Length L Ch R = 1 ,25575   ,445,445,445
BEGIN DESCRIPTION:
Stream0834 42.0
END DESCRIPTION:
XS GIS Cut Line= 3
      2477775.03     13572524.97        2478175.       13572125.
      2478624.97     13571525.04
#Sta/Elev= 30
  4430.5  273.63  4738.8  260.39  4769.9  258.16  4799.4  260.34  4812.3  260.15
  4840.6  255.67  4854.7  256.66    4882  256.16  4925.4  256.06  4934.9  254.45
  4967.9  250.67  4979.5  247.89  4979.9  247.39  4984.5  247.89  4992.6  253.52
    4999  253.52    5118  252.08  5146.1  254.39  5332.6  256.62  5346.1  257.97
  5359.7  257.26  5453.4  259.84  5488.9   262.6  5503.4  262.45  5544.7  264.95
  5559.7   266.9  5596.1  266.62  5638.9  268.84  5703.4   273.8  5746.1  274.44
#Mann= 9 ,-1 , 0
  4430.5     .05       0  4738.8     .07       0  4799.4     .12       0
    4882     .07       0  4934.9     .05       0  4979.5     .05       0
  4984.5     .05       0    4999     .07       0  5544.7     .05       0
Bank Sta=4979.5,4984.5
XS Rating Curve= 0 ,0
Exp/Cntr=0.3,0.1

Type RM Length L Ch R = 1 ,25130   ,476,476,476
BEGIN DESCRIPTION:
Stream0834 41.0
END DESCRIPTION:
XS GIS Cut Line= 3
      2477774.98     13572675.01        2478575.       13572275.
      2478774.99     13571625.02
#Sta/Elev= 30
  4111.6  276.01  4152.9  274.34  4304.5   268.8    4447     262  4528.1  260.18
  4582.6  257.03  4595.2  259.35  4617.5  259.72  4648.3  254.53  4656.7  255.77
  4751.7  255.34  4774.1   257.1  4796.4  254.74  4841.1  253.74  4894.2  250.63
  4961.3  250.79  4969.7  249.63  4972.8  246.49  4973.2  245.99  4977.8  246.49
  4997.7  250.75  5027.6  251.11  5055.1  252.65  5173.5  254.77  5309.5   254.2
  5397.7  256.23  5501.1  261.34  5631.8  270.78  5675.3  272.07  5686.1  272.26
#Mann= 6 ,-1 , 0
  4111.6     .07       0  4152.9     .05       0  4582.6     .07       0
  4972.8     .05       0  4977.8     .07       0  5675.3     .05       0
Bank Sta=4972.8,4977.8
XS Rating Curve= 0 ,0
Exp/Cntr=0.3,0.1

Type RM Length L Ch R = 1 ,24654   ,451,451,451
BEGIN DESCRIPTION:
Stream0834 40.0
END DESCRIPTION:
XS GIS Cut Line= 3
      2478375.01     13573274.99        2478975.       13572475.
        2478825.     13571675.03
#Sta/Elev= 30
  4004.8  268.26  4210.8  265.23  4402.8  259.14  4459.1  258.14  4512.1  254.78
  4526.7  256.35  4562.1  256.23  4576.7  254.26  4658.5  252.84  4741.2  251.76
  4782.9  250.35  4791.2  248.81  4832.9  249.22  4841.2  251.08  4854.8  251.51
  4912.1  251.27  4954.8  248.13  4976.7  248.23  4988.7  246.43  4989.1  245.93
  4993.8  246.43  4997.5  248.88  5001.7  249.42  5036.2  247.99  5088.7  250.93
    5198     252    5483  253.44  5645.8  260.27  5776.9  268.38  5818.7  270.73
#Mann= 9 ,-1 , 0
  4004.8     .05       0  4210.8     .07       0  4402.8     .05       0
  4459.1     .07       0  4658.5     .05       0  4988.7     .05       0
  4993.8     .05       0    5198     .07       0  5776.9     .05       0
Bank Sta=4988.7,4993.8
XS Rating Curve= 0 ,0
Exp/Cntr=0.3,0.1

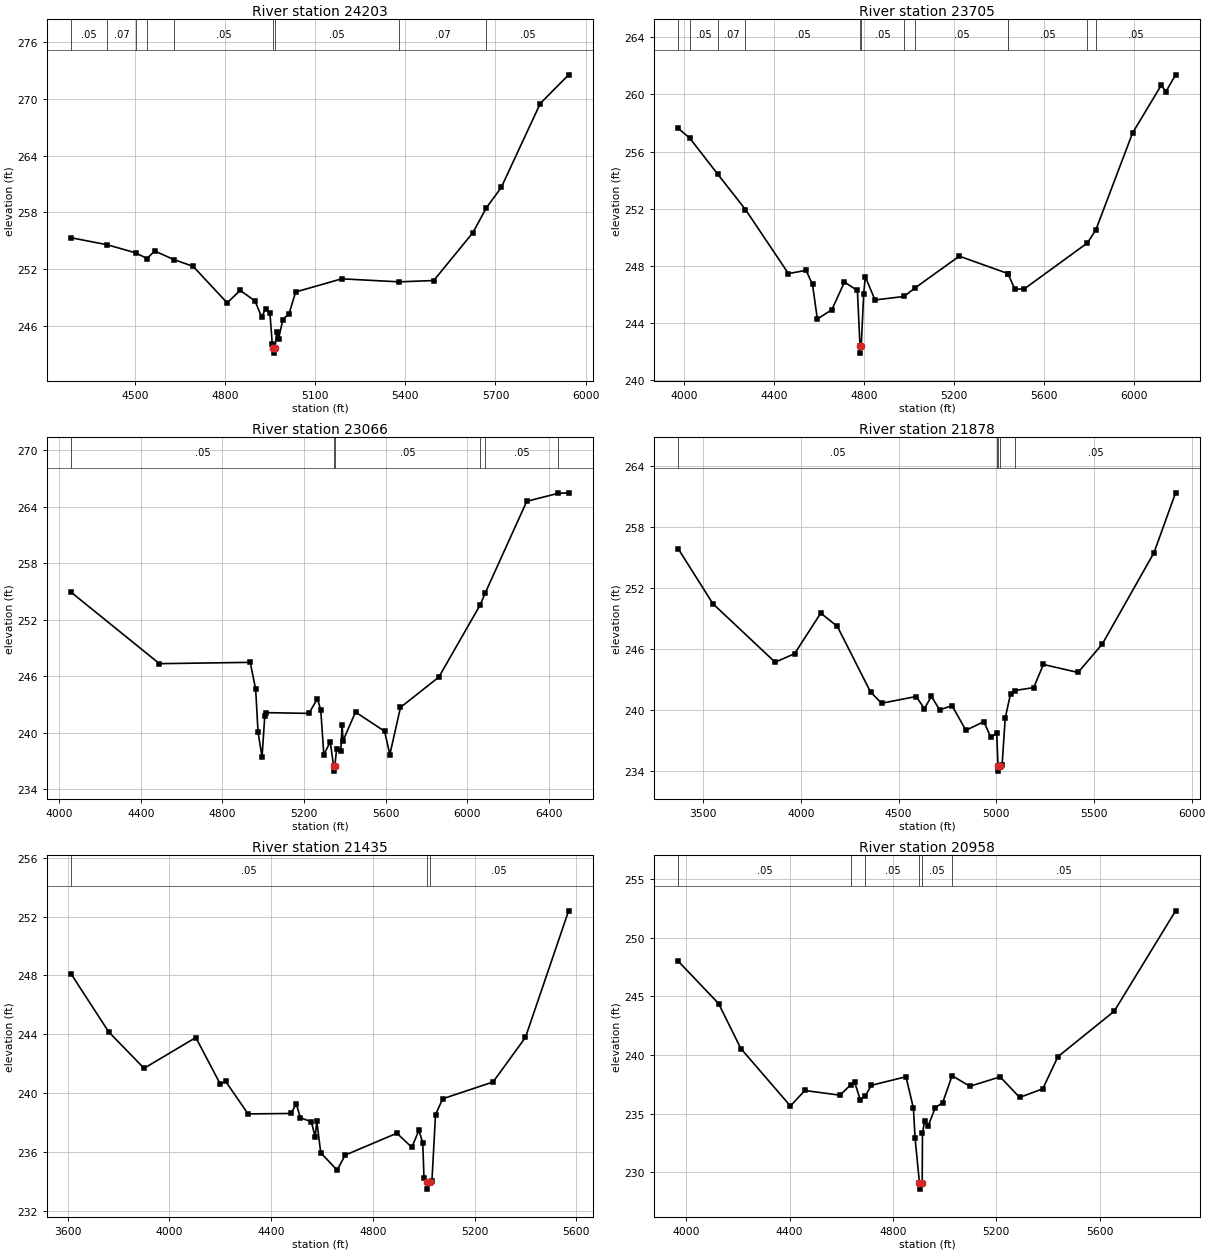
Type RM Length L Ch R = 1 ,24203   ,498,498,498
BEGIN DESCRIPTION:
Stream0834 39.0
END DESCRIPTION:
XS GIS Cut Line= 3
      2478925.03     13572974.96        2479375.       13572425.
      2478874.99     13571624.99
#Sta/Elev= 30
  4289.3  255.31  4408.3  254.58  4503.5  253.72  4540.8  253.12  4566.3  253.92
  4629.5  253.02  4694.1   252.3  4807.5  248.44  4850.6  249.76  4900.1  248.64
  4922.4  246.92  4935.3  247.84  4949.6  247.38  4957.5   244.1  4961.3  243.63
  4961.7  243.13  4966.7  243.63  4971.9   245.4  4978.4  244.62  4992.7  246.68
  5013.4   247.3  5035.3  249.59  5188.6  250.98  5379.1  250.66  5494.6   250.8
  5624.9  255.86  5669.6  258.48  5719.2  260.63  5848.9   269.5  5943.3  272.53
#Mann= 9 ,-1 , 0
  4289.3     .05       0  4408.3     .07       0  4503.5     .05       0
  4540.8     .07       0  4629.5     .05       0  4961.3     .05       0
  4966.7     .05       0  5379.1     .07       0  5669.6     .05       0
Bank Sta=4961.3,4966.7
XS Rating Curve= 0 ,0
Exp/Cntr=0.3,0.1

Type RM Length L Ch R = 1 ,23705   ,639,639,639
BEGIN DESCRIPTION:
Stream0834 38.0
END DESCRIPTION:
XS GIS Cut Line= 3
      2479225.02     13573224.98        2479875.       13572425.
      2479054.81     13571574.49
#Sta/Elev= 30
  3973.6  257.62    4024  256.95  4148.1  254.44  4272.3  251.95  4463.4  247.47
  4541.7   247.7  4570.5  246.71    4592  244.29  4656.5  244.95  4712.7  246.88
  4770.2  246.29  4781.8  242.41  4782.3  241.91  4787.3  242.41  4798.2  246.05
  4805.4  247.25  4848.5  245.63  4977.1  245.87  5027.6  246.48  5223.7  248.69
  5440.3  247.47  5440.8  247.44  5471.1  246.37  5513.6  246.41  5793.2  249.61
  5830.7  250.51  5994.4   257.3  6121.7  260.63  6143.1   260.2  6185.9  261.37
#Mann= 12 ,-1 , 0
  3973.6    .035       0    4024     .05       0  4148.1     .07       0
  4272.3     .05       0  4781.8    .035       0  4787.3     .05       0
  4977.1    .035       0  5027.6     .05       0  5440.3     .07       0
  5440.8     .05       0  5793.2     .07       0  5830.7     .05       0
Bank Sta=4781.8,4787.3
XS Rating Curve= 0 ,0
Exp/Cntr=0.3,0.1

Type RM Length L Ch R = 1 ,23066   ,1188,1188,1188
BEGIN DESCRIPTION:
Stream0834 37.0
END DESCRIPTION:
XS GIS Cut Line= 3
      2479774.97     13573475.04      2480287.77     13572908.33
      2480769.74      13571305.5
#Sta/Elev= 30
  4059.3  254.88  4490.9  247.32  4936.1  247.46  4962.8   244.6  4974.4  240.06
  4994.1  237.42  5007.4  241.73    5015  242.12  5223.9  242.04  5265.6   243.6
    5282  242.39    5297  237.65  5328.3  239.02  5345.3  236.41  5345.7  235.91
  5350.9  236.41  5359.6  238.25  5380.5  238.09  5386.3  240.82  5391.6  239.16
  5452.4  242.18  5594.9  240.14  5620.7  237.67  5672.9  242.68  5860.8  245.89
  6063.7  253.56  6088.7  254.84    6292  264.56  6444.6   265.4  6497.3  265.46
#Mann= 6 ,-1 , 0
  4059.3     .05       0  5345.3     .05       0  5350.9     .05       0
  6063.7     .07       0  6088.7     .05       0  6444.6    .035       0
Bank Sta=5345.3,5350.9
XS Rating Curve= 0 ,0
Exp/Cntr=0.3,0.1

Type RM Length L Ch R = 1 ,21878   ,443,443,443
BEGIN DESCRIPTION:
Stream0834 36.0
END DESCRIPTION:
XS GIS Cut Line= 3
      2479875.01     13573624.99        2481075.       13572525.
      2481874.96     13572075.02
#Sta/Elev= 30
  3372.1  255.81  3548.7  250.44  3867.5  244.69  3966.8  245.52  4101.2  249.51
    4186  248.21  4355.9  241.77  4412.6  240.66  4589.6  241.32  4632.1  240.12
  4667.3  241.34  4709.8  240.01  4773.4  240.42  4844.3     238  4936.1  238.85
  4971.9  237.31    5002  237.71  5008.7  234.49  5009.2  233.99  5018.7  234.49
  5029.6   234.6  5045.5  239.19  5072.9   241.6  5096.3  241.91  5191.5   242.2
  5240.9  244.47  5418.4  243.68  5542.7  246.48  5807.3  255.45  5917.8  261.33
#Mann= 5 ,-1 , 0
  3372.1     .05       0    5002     .07       0  5008.7     .05       0
  5018.7     .07       0  5096.3     .05       0
Bank Sta=5008.7,5018.7
XS Rating Curve= 0 ,0
Exp/Cntr=0.3,0.1

Type RM Length L Ch R = 1 ,21435   ,477,477,477
BEGIN DESCRIPTION:
Stream0834 35.0
END DESCRIPTION:
XS GIS Cut Line= 3
      2480125.02     13573574.99        2481325.       13572875.
      2481724.99     13572475.01
#Sta/Elev= 30
  3614.9  248.07  3761.7  244.16  3900.6  241.69    4104  243.78  4199.9  240.63
  4221.4   240.8  4309.5  238.59  4477.8  238.62  4499.3  239.27    4515  238.33
    4558  238.06  4573.7  237.03  4579.5  238.13  4595.2  235.95  4659.7  234.77
  4691.1  235.79  4894.6  237.28  4953.3  236.32    4981  237.47  4996.3  236.64
  5001.2  234.21  5013.1  233.98  5013.6  233.48  5023.5  233.98  5032.4  234.05
  5046.5  238.54  5074.8  239.62  5272.8  240.76  5400.1  243.79  5569.8  252.39
#Mann= 3 ,-1 , 0
  3614.9     .05       0  5013.1     .05       0  5023.5     .05       0
Bank Sta=5013.1,5023.5
XS Rating Curve= 0 ,0
Exp/Cntr=0.3,0.1

Type RM Length L Ch R = 1 ,20958   ,465,465,465
BEGIN DESCRIPTION:
Stream0834 34.0
END DESCRIPTION:
XS GIS Cut Line= 3
      2480325.04     13573924.97        2481125.       13573275.
      2481925.04     13572874.98
#Sta/Elev= 30
  3969.2  247.98    4125  244.38  4211.2  240.55    4403  235.66    4459  236.98
  4594.8  236.58  4637.9  237.49    4652  237.68  4673.1  236.21  4692.5  236.48
  4716.2  237.42  4850.5  238.15  4879.3  235.48  4885.7  232.92  4902.8  229.08
  4903.3  228.58  4913.3  229.08  4914.4  233.33  4922.4  234.39  4935.5  233.92
    4964  235.51  4992.7  235.95  5029.2  238.24  5097.8  237.34  5215.2  238.14
  5290.6  236.39  5380.1  237.12  5438.8  239.86  5656.8  243.73  5894.4  252.28
#Mann= 6 ,-1 , 0
  3969.2     .05       0  4637.9    .035       0  4692.5     .05       0
  4902.8    .035       0  4913.3     .05       0  5029.2     .05       0
Bank Sta=4902.8,4913.3
XS Rating Curve= 0 ,0
Exp/Cntr=0.3,0.1

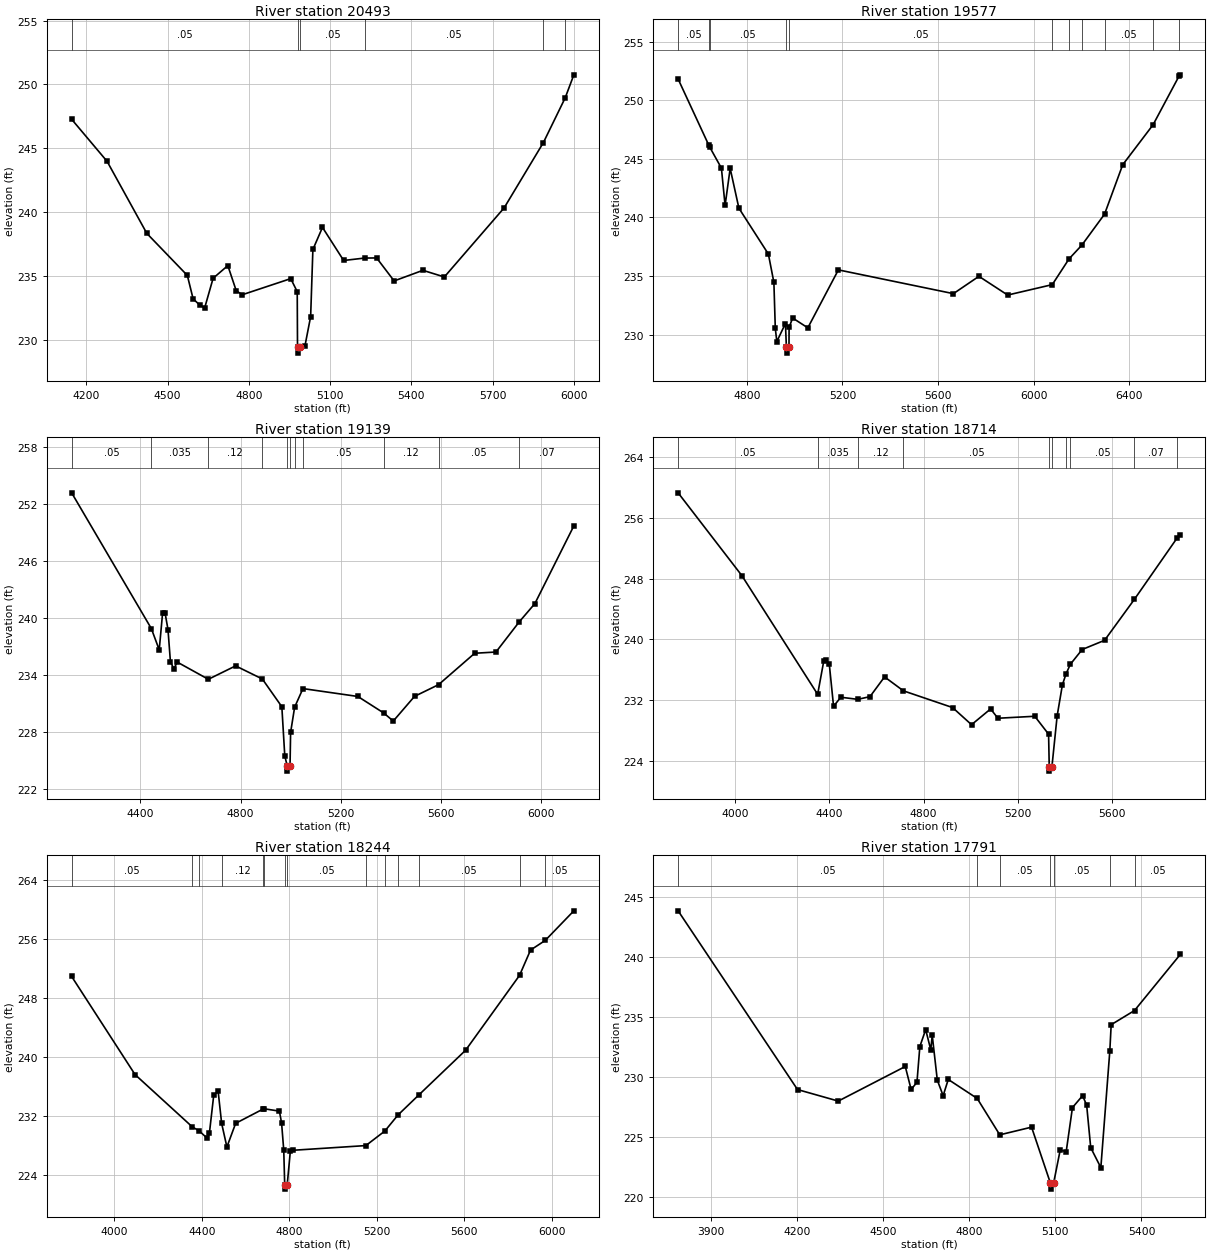
Type RM Length L Ch R = 1 ,20493   ,916,916,916
BEGIN DESCRIPTION:
Stream0834 33.0
END DESCRIPTION:
XS GIS Cut Line= 3
      2480375.04     13573974.99        2481175.       13573675.
      2481975.03     13573074.98
#Sta/Elev= 30
  4145.6  247.27  4276.4  243.98  4423.2  238.34  4572.8  235.05  4594.1  233.22
  4618.1  232.74  4636.8  232.51    4668  234.83  4722.3  235.82  4753.4  233.85
  4775.7  233.54  4954.6   234.8  4978.6  233.78  4979.6  229.47  4980.1  228.97
  4990.1  229.47  5007.3  229.56  5028.1  231.83  5036.4  237.08  5071.8  238.81
    5150  236.22  5227.3  236.41  5271.8  236.42  5336.4  234.62  5442.7  235.45
  5521.8  234.93  5742.7  240.34  5887.6  245.45  5968.1  248.95    6000  250.75
#Mann= 6 ,-1 , 0
  4145.6     .05       0  4979.6    .035       0  4990.1     .05       0
  5227.3     .05       0  5887.6     .07       0  5968.1     .05       0
Bank Sta=4979.6,4990.1
XS Rating Curve= 0 ,0
Exp/Cntr=0.3,0.1

Type RM Length L Ch R = 1 ,19577   ,438,438,438
BEGIN DESCRIPTION:
Stream0834 32.0
END DESCRIPTION:
XS GIS Cut Line= 3
      2480574.99       13574575.        2480975.       13574325.
      2482075.01     13573124.99
#Sta/Elev= 30
  4513.2  251.82  4641.9  246.15  4645.3  246.01  4694.2  244.21  4709.6  241.02
  4730.8  244.19  4767.3  240.79  4890.6  236.87  4913.6  234.45  4919.5  230.52
  4925.9   229.4  4961.9  230.94  4965.9  228.91  4966.4  228.41  4976.7  228.91
  4977.2  230.61    4992  231.41  5055.5  230.57  5183.2  235.52  5664.1  233.49
  5770.8  234.97    5891  233.37  6077.5  234.26  6147.6  236.46  6201.4  237.64
  6296.1  240.28    6372   244.5  6499.1  247.92  6607.2  252.06  6612.8  252.18
#Mann= 11 ,-1 , 0
  4513.2     .05       0  4641.9    .035       0  4645.3     .05       0
  4965.9     .05       0  4976.7     .05       0  6077.5     .07       0
  6147.6     .05       0  6201.4     .07       0  6296.1     .05       0
  6499.1     .07       0  6607.2     .05       0
Bank Sta=4965.9,4976.7
XS Rating Curve= 0 ,0
Exp/Cntr=0.3,0.1

Type RM Length L Ch R = 1 ,19139   ,425,425,425
BEGIN DESCRIPTION:
Stream0834 31.0
END DESCRIPTION:
XS GIS Cut Line= 3
      2480625.03     13574824.98        2481375.       13574375.
      2482175.01     13573574.99
#Sta/Elev= 30
  4125.4  253.19  4443.7   238.9  4475.2  236.66  4488.8  240.57  4498.6  240.53
  4510.2   238.8  4519.9  235.43  4533.5  234.65  4547.1  235.37  4671.4  233.56
  4780.4  234.97  4887.1  233.59    4965  230.67  4976.7  225.51  4986.8  224.39
  4987.3  223.89  4997.7  224.39    5000  227.96  5016.1  230.62  5049.3  232.58
  5268.7  231.75    5372  230.01  5410.1  229.16    5495  231.76  5590.9  232.99
  5735.4   236.3  5820.3  236.43  5913.1   239.6  5975.8  241.53  6131.4  249.71
#Mann= 11 ,-1 , 0
  4125.4     .05       0  4443.7    .035       0  4671.4     .12       0
  4887.1     .05       0  4986.8     .05       0  4997.7     .05       0
  5016.1     .07       0  5049.3     .05       0    5372     .12       0
  5590.9     .05       0  5913.1     .07       0
Bank Sta=4986.8,4997.7
XS Rating Curve= 0 ,0
Exp/Cntr=0.3,0.1

Type RM Length L Ch R = 1 ,18714   ,470,470,470
BEGIN DESCRIPTION:
Stream0834 30.0
END DESCRIPTION:
XS GIS Cut Line= 3
      2480475.03     13574924.99        2481675.       13574625.
      2482474.97     13574225.01
#Sta/Elev= 30
  3758.5  259.33    4029  248.42  4350.7  232.77  4376.9  237.21  4387.2  237.26
  4400.1  236.74  4418.2   231.2  4449.1  232.39  4520.9  232.11  4572.8  232.47
  4634.6  235.07  4714.8  233.23  4923.2  231.03  5003.8  228.77  5084.8  230.85
  5115.6  229.62  5272.1  229.88  5330.8  227.52  5333.6  223.15  5334.1  222.65
  5344.7  223.15  5367.1  229.93  5389.5  234.04  5404.8  235.46  5423.1  236.73
  5473.4  238.68  5568.4  239.89  5695.1   245.3  5876.1  253.37  5889.8  253.79
#Mann= 10 ,-1 , 0
  3758.5     .05       0  4350.7    .035       0  4520.9     .12       0
  4714.8     .05       0  5333.6     .05       0  5344.7     .05       0
  5404.8     .12       0  5423.1     .05       0  5695.1     .07       0
  5876.1     .05       0
Bank Sta=5333.6,5344.7
XS Rating Curve= 0 ,0
Exp/Cntr=0.3,0.1

Type RM Length L Ch R = 1 ,18244   ,453,453,453
BEGIN DESCRIPTION:
Stream0834 29.0
END DESCRIPTION:
XS GIS Cut Line= 3
      2480675.02       13575025.        2481875.       13575025.
      2482675.03     13574274.98
#Sta/Elev= 30
  3804.3  250.91  4094.3  237.64  4356.4  230.56  4386.9  230.04  4424.3  229.03
  4434.3  229.73  4454.3  234.91  4474.3  235.36  4490.3  231.03  4514.3  227.85
  4554.3  231.05    4681     233  4684.3  233.02  4754.3   232.7  4764.3  231.12
  4774.3   227.4  4778.7  222.65  4779.2  222.15  4789.8  222.65  4804.3  227.25
  4814.3   227.4  5149.8  228.04  5236.7  230.01  5296.8  232.18  5392.8  234.91
  5605.8  240.93  5852.6  251.06  5902.8  254.48  5970.2  255.79  6100.9  259.79
#Mann= 14 ,-1 , 0
  3804.3     .05       0  4356.4     .12       0  4386.9     .05       0
  4490.3     .12       0    4681    .035       0  4684.3     .05       0
  4778.7     .05       0  4789.8     .05       0  5149.8     .07       0
  5236.7     .05       0  5296.8     .07       0  5392.8     .05       0
  5852.6     .07       0  5970.2     .05       0
Bank Sta=4778.7,4789.8
XS Rating Curve= 0 ,0
Exp/Cntr=0.3,0.1

Type RM Length L Ch R = 1 ,17791   ,453,453,453
BEGIN DESCRIPTION:
Stream0834 28.0
END DESCRIPTION:
XS GIS Cut Line= 3
      2480825.04     13575225.01        2482025.       13575425.
      2482424.99     13575075.01
#Sta/Elev= 30
  3787.2  243.83  4202.8  228.95  4344.7  227.99  4577.9  230.87  4598.2  228.96
  4618.5  229.55  4628.6  232.53  4648.9  233.94  4666.6  232.26  4671.7  233.47
  4689.4  229.73  4709.7  228.44  4727.5  229.79  4828.2  228.21  4906.8  225.18
  5017.5  225.82  5083.1  221.16  5083.6  220.66  5094.2  221.16  5117.1  223.91
    5138  223.78  5159.8  227.45    5195  228.44  5209.2  227.66  5223.4  224.11
  5258.6  222.45  5289.8  232.15  5294.6  234.35  5375.8  235.53  5535.2   240.2
#Mann= 7 ,-1 , 0
  3787.2     .05       0  4828.2    .035       0  4906.8     .05       0
  5083.1     .05       0  5094.2     .05       0  5289.8     .07       0
  5375.8     .05       0
Bank Sta=5083.1,5094.2
XS Rating Curve= 0 ,0
Exp/Cntr=0.3,0.1