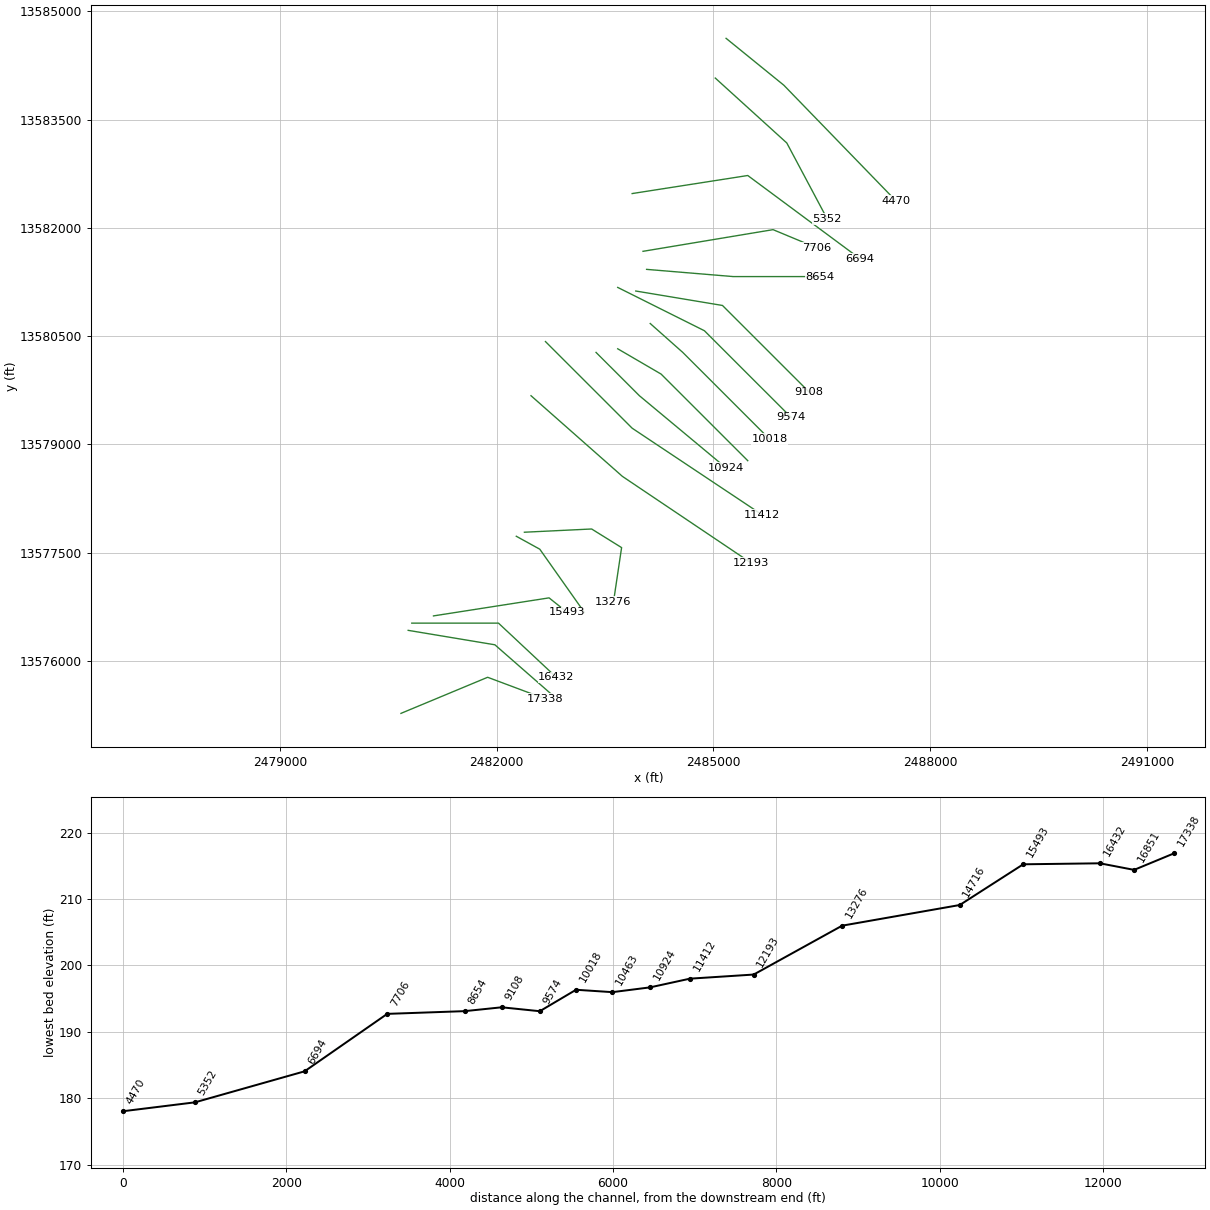
HEC-RAS study Stream0834.prj: Stream0834 Base Level Engineering

--- Stream0834.g01 (geometry) --- (continued)

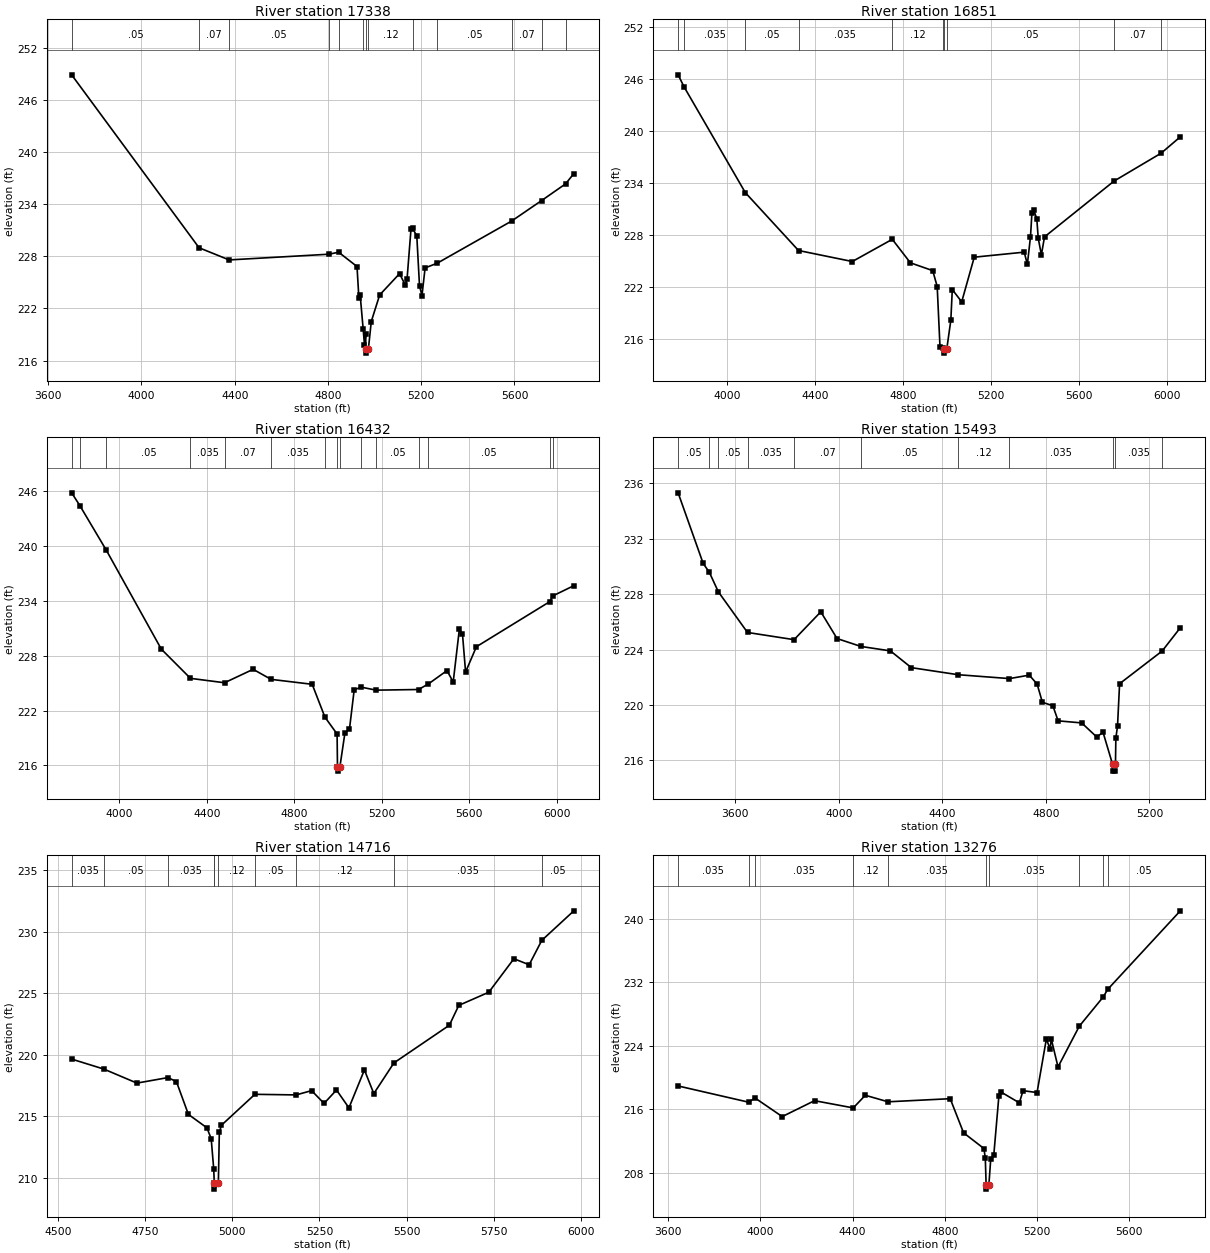
Type RM Length L Ch R = 1 ,17338   ,487,487,487
BEGIN DESCRIPTION:
Stream0834 27.0
END DESCRIPTION:
XS GIS Cut Line= 3
      2480674.97     13575274.99        2481875.       13575775.
      2482674.97     13575475.01
#Sta/Elev= 30
  3700.4   248.9    4247  228.99  4376.2  227.59  4805.1  228.25  4845.6  228.48
  4924.6  226.83  4932.7  223.17  4938.1  223.55    4951  219.64  4956.6   217.8
    4962  219.05  4962.3  217.36  4962.8  216.86  4973.5  217.36  4985.8   220.5
  5021.8  223.56  5107.2  226.01  5131.3  224.71  5139.3  225.39  5156.2  231.14
  5162.9  231.23  5181.1  230.35  5192.7   224.6  5203.3  223.49  5216.7  226.67
  5269.1  227.22  5587.6  232.06  5716.8  234.43  5819.5  236.35  5854.8  237.53
#Mann= 13 ,-1 , 0
  3700.4     .05       0    4247     .07       0  4376.2     .05       0
  4805.1     .12       0  4845.6    .035       0    4951     .12       0
  4962.3     .05       0  4973.5     .12       0  5162.9     .07       0
  5269.1     .05       0  5587.6     .07       0  5716.8     .05       0
  5819.5     .07       0
Bank Sta=4962.3,4973.5
XS Rating Curve= 0 ,0
Exp/Cntr=0.3,0.1

Type RM Length L Ch R = 1 ,16851   ,419,419,419
BEGIN DESCRIPTION:
Stream0834 26.0
END DESCRIPTION:
XS GIS Cut Line= 3
      2480775.02       13576425.        2481975.       13576225.
      2482774.96     13575525.03
#Sta/Elev= 30
  3778.7  246.46  3805.8  245.07  4083.8  232.88  4325.2  226.21  4569.4  224.94
  4750.8   227.5    4833  224.79  4934.4  223.89  4954.7  222.06  4967.4  215.09
    4979  214.97  4987.1  214.88  4987.6  214.38  4998.3  214.88  5016.6  218.17
  5023.2  221.71  5065.9  220.29  5122.9  225.44  5349.7  226.02    5364  224.61
  5378.2  227.81  5384.8  230.58  5392.4  230.88  5406.7  229.89  5413.3  227.63
  5427.6  225.71  5441.8  227.78  5757.3  234.21  5971.3  237.43  6058.2  239.31
#Mann= 10 ,-1 , 0
  3778.7     .05       0  3805.8    .035       0  4083.8     .05       0
  4325.2    .035       0  4750.8     .12       0    4979     .05       0
  4987.1     .05       0  4998.3     .05       0  5757.3     .07       0
  5971.3     .05       0
Bank Sta=4987.1,4998.3
XS Rating Curve= 0 ,0
Exp/Cntr=0.3,0.1

Type RM Length L Ch R = 1 ,16432   ,939,939,939
BEGIN DESCRIPTION:
Stream0834 25.0
END DESCRIPTION:
XS GIS Cut Line= 3
        2480825.       13576525.        2482025.       13576525.
      2482825.01     13575774.99
#Sta/Elev= 30
  3781.4  245.82  3818.7  244.43  3940.2  239.53  4191.4  228.72  4324.8  225.52
  4480.6  225.04  4611.4  226.51  4693.4  225.41  4881.4  224.87  4939.6  221.28
  4995.3  219.43  4997.1  215.87  4997.6  215.37  5008.3  215.87    5031  219.53
    5052  219.99  5073.5  224.26  5105.2  224.56    5174  224.23  5367.7   224.3
  5412.8  224.91  5497.9  226.37  5526.3  225.12  5554.6  230.92  5568.8  230.36
  5582.9  226.21  5632.3  228.98    5967   233.9  5982.4  234.55    6078  235.66
#Mann= 15 ,-1 , 0
  3781.4     .05       0  3818.7    .035       0  3940.2     .05       0
  4324.8    .035       0  4480.6     .07       0  4693.4    .035       0
  4939.6     .05       0  4997.1     .05       0  5008.3     .05       0
  5105.2    .035       0    5174     .05       0  5367.7     .07       0
  5412.8     .05       0    5967     .07       0  5982.4     .05       0
Bank Sta=4997.1,5008.3
XS Rating Curve= 0 ,0
Exp/Cntr=0.3,0.1

Type RM Length L Ch R = 1 ,15493   ,777,777,777
BEGIN DESCRIPTION:
Stream0834 24.0
END DESCRIPTION:
XS GIS Cut Line= 3
      2481125.02       13576625.        2482725.       13576875.
      2482974.96     13576675.03
#Sta/Elev= 30
  3379.5  235.31  3476.1  230.22  3500.1  229.57    3535  228.16  3647.5  225.23
  3827.3  224.71  3930.6  226.72  3993.3  224.79  4085.6  224.22  4199.3   223.9
  4280.3  222.69  4460.8  222.18  4659.3   221.9  4735.7  222.15  4766.1   221.5
  4786.3  220.19  4826.8  219.94  4847.1  218.85  4938.2   218.7  4996.4  217.68
  5020.5  218.03  5057.3  215.72  5057.8  215.22  5068.1  215.22  5068.6  215.72
  5070.1  217.62  5076.5  218.46  5084.5  221.53  5248.9  223.89    5319  225.57
#Mann= 11 ,-1 , 0
  3379.5     .05       0  3500.1    .035       0    3535     .05       0
  3647.5    .035       0  3827.3     .07       0  4085.6     .05       0
  4460.8     .12       0  4659.3    .035       0  5057.3    .035       0
  5068.6    .035       0  5248.9     .05       0
Bank Sta=5057.3,5068.6
XS Rating Curve= 0 ,0
Exp/Cntr=0.3,0.1

Type RM Length L Ch R = 1 ,14716   ,1440,1440,1440
BEGIN DESCRIPTION:
Stream0834 23.0
END DESCRIPTION:
XS GIS Cut Line= 3
      2482271.67     13577728.09      2482596.76     13577548.73
      2483213.26     13576674.42
#Sta/Elev= 30
  4538.8  219.65  4631.1  218.84  4726.1   217.7  4815.5  218.15  4839.6  217.81
  4873.8  215.16  4926.9  214.07  4939.2  213.19  4946.5  210.72  4948.1  209.59
  4948.6  209.09  4959.8  209.59  4962.6  213.71  4968.7  214.28  5064.7  216.79
  5182.9  216.74  5227.4  217.09  5263.1  216.05  5298.8  217.14  5334.5  215.69
  5378.9  218.77  5405.9  216.85  5463.6  219.34  5622.7   222.4  5649.7  224.01
  5735.9  225.08  5807.9   227.8  5851.7  227.31  5887.9  229.29  5979.9  231.69
#Mann= 10 ,-1 , 0
  4538.8    .035       0  4631.1     .05       0  4815.5    .035       0
  4946.5     .12       0  4948.1     .05       0  4959.8     .12       0
  5064.7     .05       0  5182.9     .12       0  5463.6    .035       0
  5887.9     .05       0
Bank Sta=4948.1,4959.8
XS Rating Curve= 0 ,0
Exp/Cntr=0.3,0.1

Type RM Length L Ch R = 1 ,13276   ,1083,1083,1083
BEGIN DESCRIPTION:
Stream0834 21.0
END DESCRIPTION:
XS GIS Cut Line= 4
      2482383.77     13577784.11      2483314.12     13577828.95
      2483728.84     13577571.15      2483616.76     13576820.21
#Sta/Elev= 30
  3643.1  218.95  3949.1  216.91  3976.8  217.44  4094.9   215.1    4235   217.1
  4403.1  216.19  4455.3  217.78    4554  216.96  4823.7  217.35  4881.7  213.06
  4970.2  211.08    4976  209.85  4979.6  206.48  4980.1  205.98  4991.4  206.48
  4999.5  209.74  5012.7  210.23  5034.8  217.65  5043.4   218.2  5123.7  216.83
  5139.8  218.36  5200.5  218.12  5240.9  224.86  5257.2  223.59  5262.2  224.86
  5291.5  221.34  5383.9  226.47  5487.3  230.13  5507.6  231.11  5822.1  240.97
#Mann= 10 ,-1 , 0
  3643.1    .035       0  3949.1     .07       0  3976.8    .035       0
  4403.1     .12       0    4554    .035       0  4979.6    .035       0
  4991.4    .035       0  5383.9     .05       0  5487.3     .07       0
  5507.6     .05       0
Bank Sta=4979.6,4991.4
XS Rating Curve= 0 ,0
Exp/Cntr=0.3,0.1

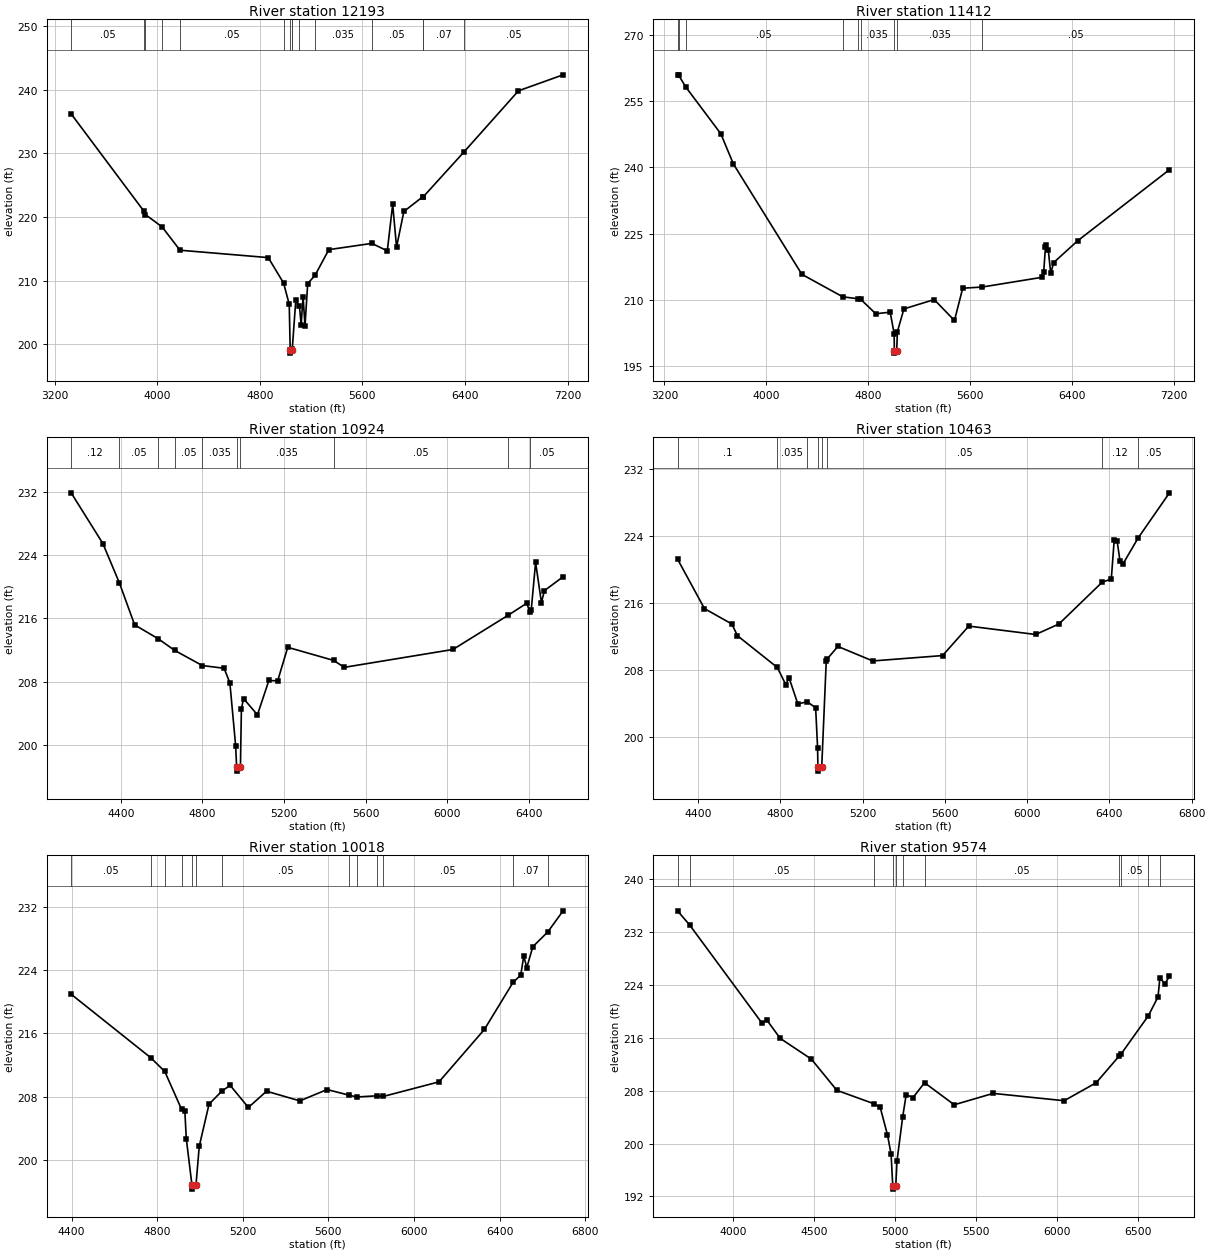
Type RM Length L Ch R = 1 ,12193   ,781,781,781
BEGIN DESCRIPTION:
Stream0834 19.0
END DESCRIPTION:
XS GIS Cut Line= 3
      2482475.02     13579674.98      2483740.05     13578557.51
      2485522.26     13577358.16
#Sta/Elev= 30
  3329.1  236.19  3894.3  220.97  3908.6  220.37  4038.5  218.44  4177.8  214.78
  4866.2  213.62  4985.5  209.63  5029.7  206.29  5037.3  199.12  5037.8  198.62
  5052.1  199.12  5053.3  199.22  5080.7  206.89  5109.5  205.98  5122.7  203.07
  5137.7  207.48  5152.7  202.92  5173.7  209.54  5230.4  210.82  5338.7  214.87
  5673.9  215.85  5794.4  214.68  5836.5  221.99  5866.5  215.27  5923.5  220.86
  6069.5  223.15  6076.4   223.2  6392.4  230.21  6817.3  239.81  7165.2  242.32
#Mann= 15 ,-1 , 0
  3329.1     .05       0  3894.3    .035       0  3908.6     .05       0
  4038.5     .12       0  4177.8     .05       0  4985.5     .12       0
  5037.3     .05       0  5052.1     .12       0  5053.3     .05       0
  5109.5     .12       0  5230.4    .035       0  5673.9     .05       0
  6069.5    .035       0  6076.4     .07       0  6392.4     .05       0
Bank Sta=5037.3,5052.1
XS Rating Curve= 0 ,0
Exp/Cntr=0.3,0.1

Type RM Length L Ch R = 1 ,11412   ,488,488,488
BEGIN DESCRIPTION:
Stream0834 17.0
END DESCRIPTION:
XS GIS Cut Line= 3
      2482675.03     13580424.97        2483875.       13579225.
      2485674.97     13578025.02
#Sta/Elev= 30
  3302.7  260.94  3310.6   260.9  3366.6  258.22  3642.1  247.63  3741.1  240.78
  4278.5  215.82    4599  210.74  4721.8  210.28  4738.6  210.21  4858.3  206.91
  4971.4  207.26  5002.7  202.41    5004   198.5  5004.5     198  5022.5   198.5
  5028.3  202.88  5079.3     208  5316.7  210.11  5475.9  205.38  5540.5  212.68
    5694  212.95    6161  215.14    6176  216.25  6189.5  221.91  6197.1  222.48
  6212.1  221.25  6231.6  216.01  6254.1  218.48  6441.9  223.39    7163  239.49
#Mann= 9 ,-1 , 0
  3302.7     .05       0  3310.6     .07       0  3366.6     .05       0
    4599    .035       0  4721.8     .07       0  4738.6    .035       0
    5004    .035       0  5022.5    .035       0    5694     .05       0
Bank Sta=5004,5022.5
XS Rating Curve= 0 ,0
Exp/Cntr=0.3,0.1

Type RM Length L Ch R = 1 ,10924   ,461,461,461
BEGIN DESCRIPTION:
Stream0834 16.0
END DESCRIPTION:
XS GIS Cut Line= 3
      2483375.03     13580274.97        2483975.       13579675.
      2485174.97     13578675.02
#Sta/Elev= 30
  4156.6  231.87  4312.1  225.46  4393.4  220.46  4467.7  215.18  4583.4  213.42
  4664.5  211.94  4799.1  210.04  4906.1  209.69  4934.4  207.84  4962.7  199.88
  4967.5  197.19    4968  196.69  4986.1  197.19  4990.9   204.6  5001.6  205.85
  5069.5  203.81  5125.5  208.15  5168.5   208.1  5217.9  212.34  5442.3  210.69
  5495.2  209.81  6027.6  212.07  6299.4  216.42  6389.5  217.92  6403.7   216.8
  6410.9  217.03  6432.4  223.08    6461  217.99  6475.4   219.5  6567.1  221.26
#Mann= 10 ,-1 , 0
  4156.6     .12       0  4393.4     .05       0  4583.4     .12       0
  4664.5     .05       0  4799.1    .035       0  4967.5    .035       0
  4986.1    .035       0  5442.3     .05       0  6299.4     .12       0
  6403.7     .05       0
Bank Sta=4967.5,4986.1
XS Rating Curve= 0 ,0
Exp/Cntr=0.3,0.1

Type RM Length L Ch R = 1 ,10463   ,445,445,445
BEGIN DESCRIPTION:
Stream0834 15.0
END DESCRIPTION:
XS GIS Cut Line= 3
      2483674.96     13580325.02        2484275.       13579975.
      2485474.98     13578775.02
#Sta/Elev= 30
  4300.4  221.22  4431.5  215.32  4564.6  213.49  4591.9  212.09  4785.8  208.31
  4826.8  206.27  4842.5   207.1  4885.5  203.96  4930.7  204.24  4971.9  203.51
  4981.4  198.75  4982.9  196.47  4983.4  195.97  5001.5  196.47  5023.4  209.05
  5027.3   209.3  5079.9  210.82  5249.6  209.09    5589  209.73  5716.3  213.24
  6041.6  212.24  6154.7  213.49  6365.5  218.48  6409.3  218.84  6423.4  223.48
  6437.6  223.36  6451.7  220.99  6465.8  220.63  6539.1  223.71  6692.1  229.11
#Mann= 8 ,-1 , 0
  4300.4      .1       0  4785.8    .035       0  4930.7     .12       0
  4982.9     .05       0  5001.5     .12       0  5027.3     .05       0
  6365.5     .12       0  6539.1     .05       0
Bank Sta=4982.9,5001.5
XS Rating Curve= 0 ,0
Exp/Cntr=0.3,0.1

Type RM Length L Ch R = 1 ,10018   ,444,444,444
BEGIN DESCRIPTION:
Stream0834 14.0
END DESCRIPTION:
XS GIS Cut Line= 3
      2484124.98     13580675.01        2484575.       13580275.
      2485775.03     13579074.97
#Sta/Elev= 30
  4397.9  220.93  4770.3  212.91  4835.5  211.18    4914   206.4  4929.3   206.2
    4936  202.72  4962.6  196.83  4963.1  196.33  4981.3  196.83  4996.7  201.75
  5042.4  207.05  5103.1  208.73  5141.4  209.42  5226.3  206.64  5311.1  208.69
  5466.7  207.47    5594   208.9  5698.4  208.18    5732  207.96  5827.7  208.11
  5856.8  208.03  6117.2  209.87  6329.4  216.49  6463.8  222.45  6499.1  223.33
  6513.2  225.75  6527.4   224.3  6555.6  226.93  6625.8   228.8  6697.1  231.46
#Mann= 13 ,-1 , 0
  4397.9     .05       0  4770.3     .12       0  4835.5    .035       0
    4914     .12       0  4962.6     .05       0  4981.3     .12       0
  5103.1     .05       0  5698.4    .035       0    5732     .05       0
  5827.7    .035       0  5856.8     .05       0  6463.8     .07       0
  6625.8     .05       0
Bank Sta=4962.6,4981.3
XS Rating Curve= 0 ,0
Exp/Cntr=0.3,0.1

Type RM Length L Ch R = 1 ,9574    ,466,466,466
BEGIN DESCRIPTION:
Stream0834 13.0
END DESCRIPTION:
XS GIS Cut Line= 3
      2483675.03     13581174.98        2484875.       13580575.
      2486075.03     13579374.97
#Sta/Elev= 30
  3658.4  235.19  3733.3  233.05    4181  218.18    4209  218.71  4292.8   215.9
  4485.7  212.75  4642.2  208.05  4874.2  205.99  4910.6  205.45  4955.3   201.3
  4977.6   198.4  4987.9   193.6  4988.4   193.1  5006.6   193.6  5014.1  197.37
  5048.8  203.94  5070.7  207.38  5113.1  206.95  5184.3  209.19  5367.7  205.86
  5608.1  207.58  6046.5  206.47  6244.5  209.19  6386.1  213.22    6399  213.56
  6566.2   219.3  6626.3  222.17  6637.9  225.03  6668.8  224.17  6697.1  225.28
#Mann= 11 ,-1 , 0
  3658.4    .035       0  3733.3     .05       0  4874.2      .1       0
  4987.9     .05       0  5006.6      .1       0  5048.8    .035       0
  5184.3     .05       0  6386.1    .035       0    6399     .05       0
  6566.2    .035       0  6637.9     .05       0
Bank Sta=4987.9,5006.6
XS Rating Curve= 0 ,0
Exp/Cntr=0.3,0.1

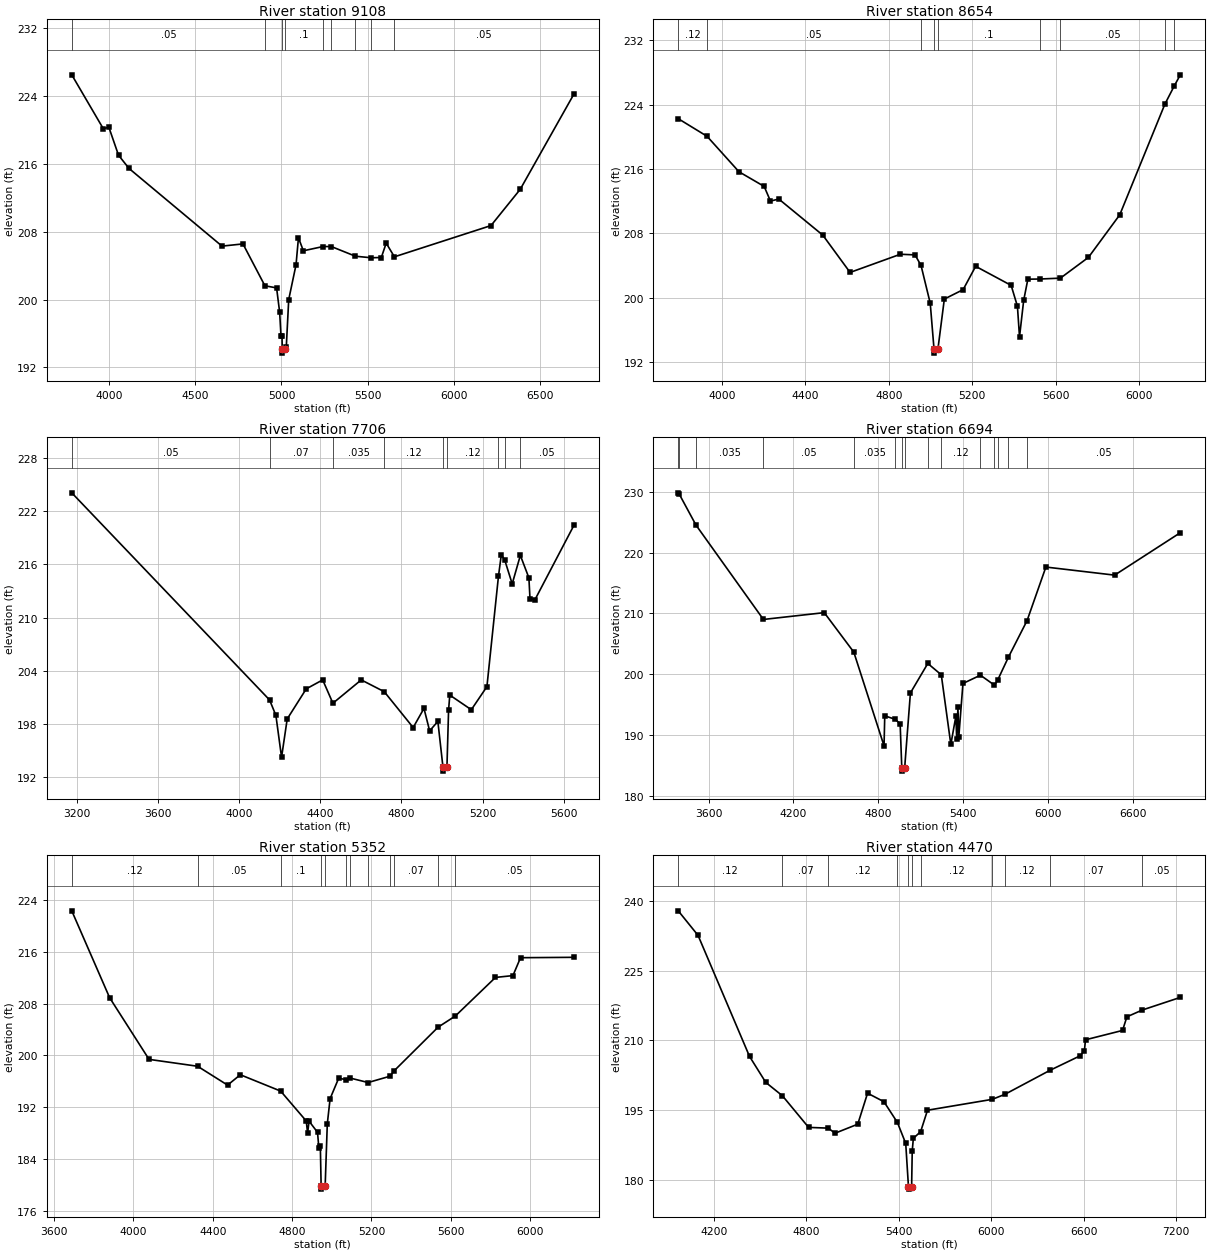
Type RM Length L Ch R = 1 ,9108    ,454,454,454
BEGIN DESCRIPTION:
Stream0834 12.0
END DESCRIPTION:
XS GIS Cut Line= 3
      2483925.02       13581125.        2485125.       13580925.
      2486325.01     13579724.99
#Sta/Elev= 30
    3783  226.46  3965.5  220.13  3998.4  220.28  4054.2     217    4115  215.44
  4654.8  206.29  4776.5  206.55  4903.8  201.62  4971.6  201.37  4989.4   198.5
    4997  195.76  5003.1  195.76  5004.3  194.19  5004.8  193.69    5023  194.19
  5027.8  194.38    5042     200  5084.4  204.09  5098.5  207.28  5126.8  205.74
    5241  206.24  5289.3  206.24  5429.3   205.1  5519.8  204.92  5579.4  204.95
  5607.6  206.64  5655.3  205.03  6215.8  208.71  6385.5  212.98  6696.6  224.18
#Mann= 9 ,-1 , 0
    3783     .05       0  4903.8      .1       0  5004.3     .05       0
    5023      .1       0    5241     .07       0  5289.3      .1       0
  5429.3     .07       0  5519.8    .035       0  5655.3     .05       0
Bank Sta=5004.3,5023
XS Rating Curve= 0 ,0
Exp/Cntr=0.3,0.1

Type RM Length L Ch R = 1 ,8654    ,948,948,948
BEGIN DESCRIPTION:
Stream0834 11.0
END DESCRIPTION:
XS GIS Cut Line= 3
      2484074.97       13581425.        2485275.       13581325.
      2486475.01       13581325.
#Sta/Elev= 30
  3791.7  222.25  3929.7  220.06  4082.7  215.65  4203.2  213.83  4233.3  212.01
  4273.4  212.26  4484.1  207.77  4614.6  203.14  4855.4   205.4  4925.6  205.32
  4954.3  204.01  4998.4  199.31  5016.5  193.61    5017  193.11  5035.2  193.61
  5065.9  199.83  5155.9     201  5215.9   203.9  5385.9  201.53  5415.9  198.94
  5425.9  195.13  5445.9  199.67  5465.9   202.3  5523.3  202.32  5621.7  202.43
  5755.9  205.01  5905.9   210.3  6122.1  224.06  6166.5   226.3  6195.9   227.7
#Mann= 9 ,-1 , 0
  3791.7     .12       0  3929.7     .05       0  4954.3      .1       0
  5016.5     .05       0  5035.2      .1       0  5523.3     .12       0
  5621.7     .05       0  6122.1    .035       0  6166.5     .05       0
Bank Sta=5016.5,5035.2
XS Rating Curve= 0 ,0
Exp/Cntr=0.3,0.1

Type RM Length L Ch R = 1 ,7706    ,1012,1012,1012
BEGIN DESCRIPTION:
Stream0834 9.0
END DESCRIPTION:
XS GIS Cut Line= 3
      2484024.97       13581675.        2485825.       13581975.
      2486425.04     13581724.98
#Sta/Elev= 30
  3174.7  224.06  4149.8  200.72  4180.9  198.98  4208.8  194.26  4236.7  198.58
  4330.5  201.97  4411.6  202.98  4461.9  200.35  4601.6  202.98  4715.1  201.65
  4857.6  197.61  4910.8  199.77  4938.7  197.24  4979.3   198.3  5004.2   193.2
  5004.7   192.7  5024.1   193.2  5032.1  199.55    5038  201.27  5144.2  199.62
  5221.1  202.22  5278.1  214.68  5292.1  217.08  5309.6  216.44  5345.7   213.8
  5385.9  217.01    5428  214.48  5433.4  212.15  5457.3  211.99  5649.6  220.38
#Mann= 9 ,-1 , 0
  3174.7     .05       0  4149.8     .07       0  4461.9    .035       0
  4715.1     .12       0  5004.2     .05       0  5024.1     .12       0
  5278.1     .07       0  5309.6     .12       0  5385.9     .05       0
Bank Sta=5004.2,5024.1
XS Rating Curve= 0 ,0
Exp/Cntr=0.3,0.1

Type RM Length L Ch R = 1 ,6694    ,1342,1342,1342
BEGIN DESCRIPTION:
Stream0834 8.0
END DESCRIPTION:
XS GIS Cut Line= 3
      2483874.97       13582475.        2485475.       13582725.
      2487025.02     13581574.98
#Sta/Elev= 30
  3385.2  229.83  3390.2  229.71  3510.5  224.53  3987.3     209  4417.6  210.12
  4626.5  203.62  4840.2   188.2  4845.2  193.15  4919.5  192.57    4954  191.84
  4965.7  184.55  4966.2  184.05  4985.8  184.55  5026.6  196.91  5149.5  201.76
  5244.8   199.9  5312.4  188.44  5347.9  193.08  5354.1  189.26  5362.5  194.59
  5368.7  189.69    5398  198.47  5521.5  199.83  5620.8  198.19  5642.5  198.98
  5719.4  202.79  5851.5  208.82  5984.3  217.62  6470.4  216.29  6934.7  223.27
#Mann= 15 ,-1 , 0
  3385.2     .07       0  3390.2     .12       0  3510.5    .035       0
  3987.3     .05       0  4626.5    .035       0  4919.5     .12       0
  4965.7     .05       0  4985.8     .12       0  5149.5      .1       0
  5244.8     .12       0  5521.5      .1       0  5620.8     .07       0
  5642.5     .12       0  5719.4     .07       0  5851.5     .05       0
Bank Sta=4965.7,4985.8
XS Rating Curve= 0 ,0
Exp/Cntr=0.3,0.1

Type RM Length L Ch R = 1 ,5352    ,882,882,882
BEGIN DESCRIPTION:
Stream0834 6.0
END DESCRIPTION:
XS GIS Cut Line= 3
        2485025.       13584075.      2486015.41      13583175.5
      2486575.84      13582121.9
#Sta/Elev= 30
  3689.4   222.3  3880.3   208.9    4079  199.39  4323.8  198.33    4475  195.42
  4539.2  197.02  4742.5   194.5  4871.6  189.89  4878.4  188.01  4885.8  189.86
  4928.4  188.14  4935.2  185.71  4942.6  185.98  4946.6  179.88  4947.1  179.38
  4966.9  179.88  4977.7  189.45  4991.9  193.34  5035.3   196.5  5073.5  196.24
  5093.9   196.5  5183.5  195.82  5293.4  196.79  5315.1  197.64  5536.4  204.36
  5623.3  206.08  5825.7  212.03  5913.6  212.31  5951.9  215.07  6220.7  215.13
#Mann= 12 ,-1 , 0
  3689.4     .12       0  4323.8     .05       0  4742.5      .1       0
  4946.6     .05       0  4966.9      .1       0  5073.5     .07       0
  5093.9    .035       0  5183.5     .07       0  5293.4     .12       0
  5315.1     .07       0  5536.4     .12       0  5623.3     .05       0
Bank Sta=4946.6,4966.9
XS Rating Curve= 0 ,0
Exp/Cntr=0.3,0.1

Type RM Length L Ch R = 1 ,4470    ,1648,1648,1648
BEGIN DESCRIPTION:
Stream0834 4.0
END DESCRIPTION:
XS GIS Cut Line= 3
      2485175.04     13584624.97        2485975.       13583975.
        2487525.       13582375.
#Sta/Elev= 30
  3969.4  237.86    4098  232.58    4432  206.57  4537.5  200.98  4645.7   198.1
  4815.5  191.31  4943.8  191.15  4986.5  190.05  5134.5     192  5198.1  198.66
  5304.3  196.83  5391.8  192.37  5445.7  187.87  5463.6  178.54  5464.1  178.04
    5484  178.54    5488  186.24  5495.2  188.95  5542.7  190.41    5587     195
  6007.6  197.34  6089.6  198.42  6380.9  203.56  6577.1  206.69  6605.4  207.83
  6612.6  210.14  6852.9  212.15  6881.2  215.08  6981.9  216.55  7227.8  219.25
#Mann= 11 ,-1 , 0
  3969.4     .12       0  4645.7     .07       0  4943.8     .12       0
  5391.8      .1       0  5463.6     .05       0    5484      .1       0
  5542.7     .12       0  6007.6    .035       0  6089.6     .12       0
  6380.9     .07       0  6981.9     .05       0
Bank Sta=5463.6,5484
XS Rating Curve= 0 ,0
Exp/Cntr=0.3,0.1