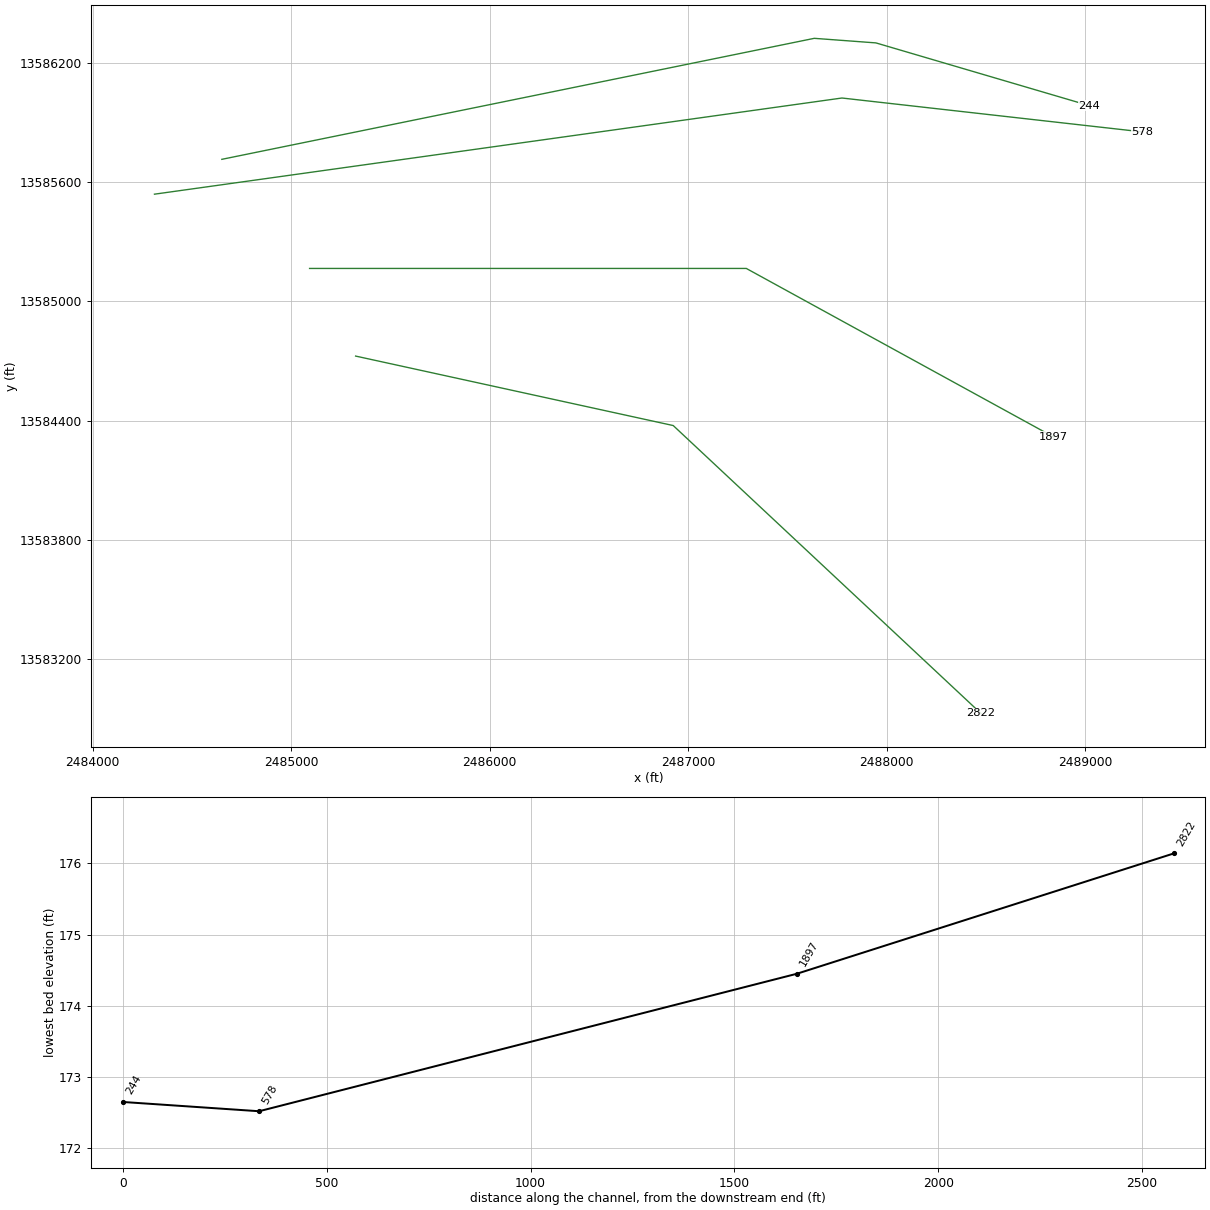
HEC-RAS study Stream0834.prj: Stream0834 Base Level Engineering

--- Stream0834.g01 (geometry) --- (continued)

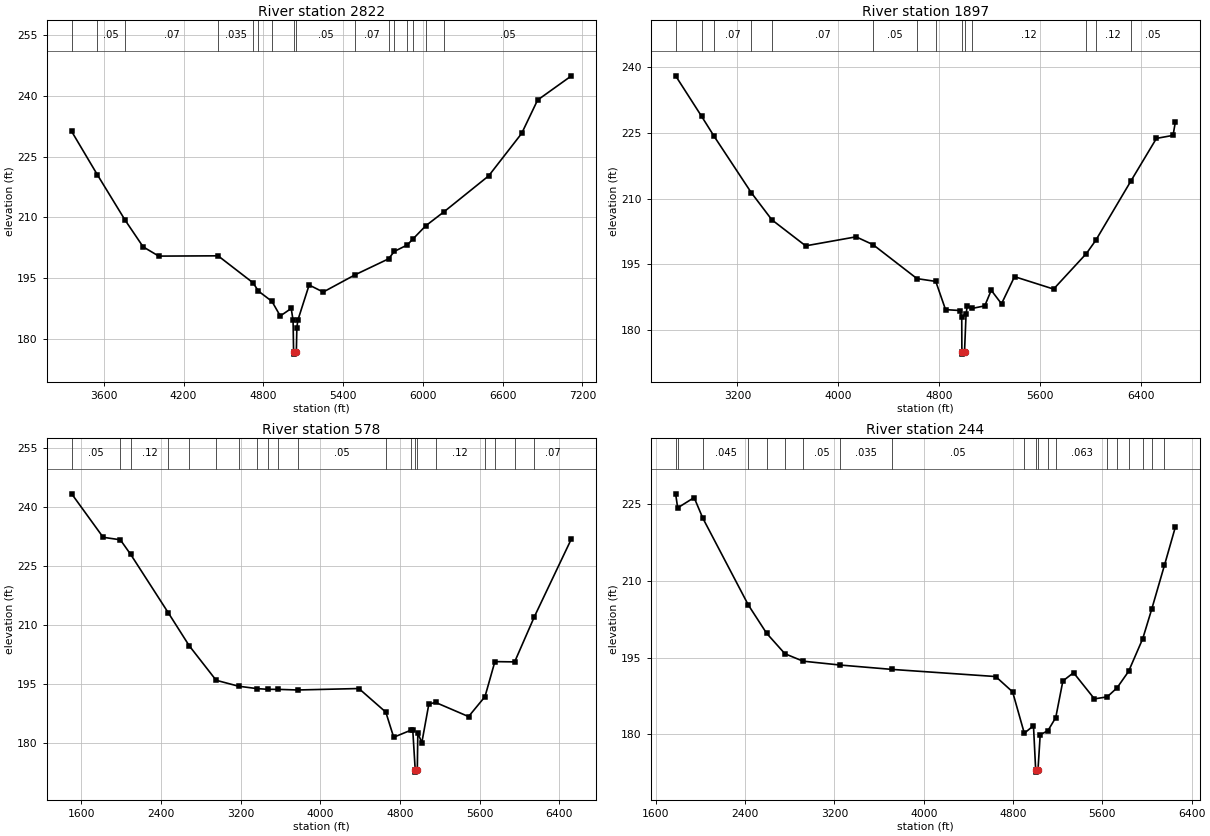
Type RM Length L Ch R = 1 ,2822    ,925,925,925
BEGIN DESCRIPTION:
Stream0834 3.0
END DESCRIPTION:
XS GIS Cut Line= 3
        2485325.       13584725.        2486925.       13584375.
      2488474.98     13582925.02
#Sta/Elev= 30
  3357.6  231.23  3550.4  220.55  3759.3  209.31  3895.4  202.68  4012.7  200.39
  4459.3  200.46  4722.1  193.79  4763.2  191.72  4864.5  189.19  4927.1  185.58
  5009.4  187.43  5023.5   184.5  5027.3  176.64  5027.8  176.14    5048  176.64
  5051.9  182.65  5059.2  184.51  5144.2  193.24  5250.2   191.5  5491.6  195.79
  5741.7  199.71  5785.2  201.55  5881.7  203.13  5923.5  204.56  6021.6  207.89
  6161.6  211.42  6495.3  220.25    6743  230.73  6863.2     239  7117.9  244.99
#Mann= 16 ,-1 , 0
  3357.6     .12       0  3550.4     .05       0  3759.3     .07       0
  4459.3    .035       0  4722.1     .07       0  4763.2    .035       0
  4864.5     .05       0  5027.3     .05       0    5048     .05       0
  5491.6     .07       0  5741.7     .05       0  5785.2     .07       0
  5881.7     .05       0  5923.5     .07       0  6021.6    .035       0
  6161.6     .05       0
Bank Sta=5027.3,5048
XS Rating Curve= 0 ,0
Exp/Cntr=0.3,0.1

Type RM Length L Ch R = 1 ,1897    ,1319,1319,1319
BEGIN DESCRIPTION:
Stream0834 2.0
END DESCRIPTION:
XS GIS Cut Line= 3
      2485093.17     13585166.43      2487293.13     13585166.43
      2488841.52     13584317.31
#Sta/Elev= 30
  2709.2  238.06  2916.1  228.77  3014.4  224.25  3309.5  211.36  3472.9  205.15
    3741   199.2    4141  201.26  4275.7  199.47  4624.3  191.71  4773.5  191.07
    4851  184.62  4963.4  184.42  4979.5  183.03  4980.7  174.95  4981.2  174.45
  5001.5  174.95  5013.9   183.6  5023.1  185.45  5060.5  184.89  5162.2  185.48
  5213.6  189.05  5295.1  185.95  5398.4  192.16  5708.4  189.32  5968.6  197.44
  6042.3  200.43  6322.9  214.07  6524.5  223.76  6656.3  224.45  6675.1   227.6
#Mann= 14 ,-1 , 0
  2709.2     .12       0  2916.1     .05       0  3014.4     .07       0
  3309.5     .05       0  3472.9     .07       0  4275.7     .05       0
  4624.3     .12       0  4773.5      .1       0  4980.7     .05       0
  5001.5      .1       0  5060.5     .12       0  5968.6     .07       0
  6042.3     .12       0  6322.9     .05       0
Bank Sta=4980.7,5001.5
XS Rating Curve= 0 ,0
Exp/Cntr=0.3,0.1

Type RM Length L Ch R = 1 ,578     ,334,334,334
BEGIN DESCRIPTION:
Stream0834 1.0
END DESCRIPTION:
XS GIS Cut Line= 3
       2484311.7     13585540.53        2487775.       13586025.
       2489288.4     13585854.37
#Sta/Elev= 30
    1503  243.26  1819.3  232.21  1991.7  231.58  2095.9  227.86  2474.6  212.98
  2684.2  204.63  2954.1  195.87  3178.8  194.36  3367.2  193.74  3475.6  193.57
  3574.5  193.56  3772.4   193.4  4387.8  193.77  4658.4  187.77  4737.5  181.39
  4916.2  183.24  4929.3  183.15  4953.8  173.02  4954.3  172.52  4974.7  173.02
  4979.8  182.47  5020.1  180.01  5090.6  189.82    5158  190.24  5489.5  186.64
  5654.5  191.71  5753.8  200.61  5952.4  200.54    6151  212.05    6523  231.84
#Mann= 20 ,-1 , 0
    1503     .05       0  1991.7     .07       0  2095.9     .12       0
  2474.6     .07       0  2684.2     .05       0  2954.1    .035       0
  3178.8     .07       0  3367.2     .05       0  3475.6     .07       0
  3574.5    .035       0  3772.4     .05       0  4658.4     .12       0
  4916.2      .1       0  4953.8     .05       0  4974.7      .1       0
    5158     .12       0  5654.5     .05       0  5753.8    .063       0
  5952.4     .05       0    6151     .07       0
Bank Sta=4953.8,4974.7
XS Rating Curve= 0 ,0
Exp/Cntr=0.3,0.1

Type RM Length L Ch R = 1 ,244     ,0,0,0
BEGIN DESCRIPTION:
H21125
END DESCRIPTION:
XS GIS Cut Line= 4
      2484651.13      13585716.1      2487635.56     13586325.63
      2487946.08     13586302.63      2489020.66     13585986.58
#Sta/Elev= 30
  1777.3  226.98  1795.7  224.24  1943.1  226.25  2020.7  222.24  2429.2  205.26
  2592.1  199.77  2756.4  195.76    2919  194.31    3254  193.55  3717.6   192.7
  4644.7  191.31  4796.2  188.32  4900.9  180.25  4983.2   181.7  5002.7  173.15
  5003.2  172.65  5023.8  173.15  5043.4  179.95  5112.1  180.73  5182.5  183.29
  5246.7  190.45  5342.1  192.06  5529.2  186.95  5643.5  187.34  5731.4  189.09
  5834.8   192.3    5962   198.7  6041.6   204.4  6156.2  213.01  6254.8  220.54
#Mann= 20 ,-1 , 0
  1777.3     .05       0  1795.7     .12       0  2020.7    .045       0
  2429.2     .05       0  2592.1     .05       0  2756.4    .035       0
    2919     .05       0    3254    .035       0  3717.6     .05       0
  4900.9     .12       0  5002.7     .05       0  5023.8     .12       0
  5112.1     .12       0  5182.5    .063       0  5643.5    .063       0
  5731.4      .1       0  5834.8     .12       0    5962    .063       0
  6041.6     .07       0  6156.2     .05       0
Bank Sta=5002.7,5023.8
XS Rating Curve= 0 ,0
Exp/Cntr=0.3,0.1

Chan Stop Cuts=-1
Use User Specified Reach Order=0
Composite Channel Slope=5