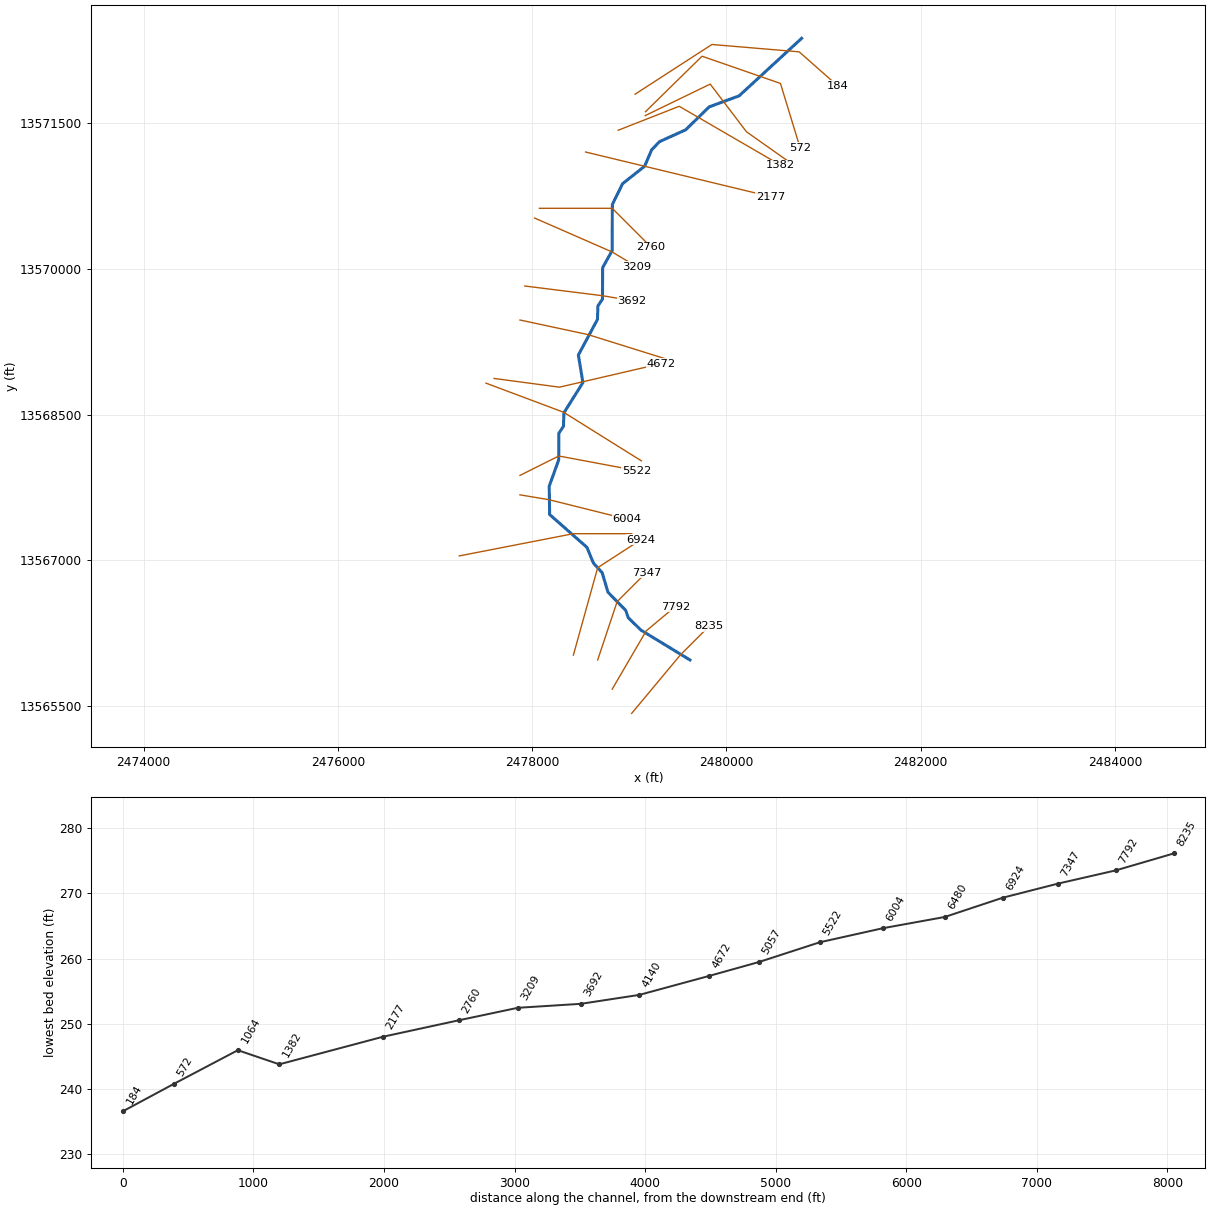
--- Stream0835.prj (project) ---

Proj Title=Stream0835 Base Level Engineering
Current Plan=p01
Default Exp/Contr=0.3,0.1
English Units
Geom File=g01
Flow File=f01
Plan File=p01
BEGIN DESCRIPTION:
Stream0835
END DESCRIPTION:

--- Stream0835.p01 (plan) ---

Plan Title=Multiple Run
Short Identifier=Multiple
Geom File=g01
Flow File=f01
Subcritical Flow
K Sum by GR= 0
Std Step Tol= 0.01
Critical Tol= 0.01
Num of Std Step Trials= 20
Max Error Tol= 0.3
Flow Tol Ratio= 0.001
Split Flow NTrial= 30
Split Flow Tol= 0.02
Split Flow Ratio= 0.02
Log Output Level= 0
Friction Slope Method= 1
Unsteady Friction Slope Method= 2
Unsteady Bridges Friction Slope Method= 1
Parabolic Critical Depth
Global Vel Dist=  1 , 1 , 1
Global Log Level= 0
CheckData=True
Encroach Param= -1, 0, 0, 0
BEGIN DESCRIPTION:
Multiple Run
END DESCRIPTION:

--- Stream0835.f01 (steady flow) ---

Flow Title=Multiple
Number of Profiles=7
Profile Names=10-year,25-year,50-year,1pct_min,100-year,1pct_plu,500-year
River Rch & RM= Stream0835,Reach-1,8235
     465     739     984     636    1268    2531    2086
River Rch & RM= Stream0835,Reach-1,6004
    1005    1661    2268    1498    2989    5964    5144
Boundary for River Rch & Prof#=Stream0835,Reach-1,1
Up Type=0
Dn Type=3
Dn Slope=0.005
Boundary for River Rch & Prof#=Stream0835,Reach-1,2
Up Type=0
Dn Type=3
Dn Slope=0.005
Boundary for River Rch & Prof#=Stream0835,Reach-1,3
Up Type=0
Dn Type=3
Dn Slope=0.005
Boundary for River Rch & Prof#=Stream0835,Reach-1,4
Up Type=0
Dn Type=3
Dn Slope=0.005
Boundary for River Rch & Prof#=Stream0835,Reach-1,5
Up Type=0
Dn Type=3
Dn Slope=0.005
Boundary for River Rch & Prof#=Stream0835,Reach-1,6
Up Type=0
Dn Type=3
Dn Slope=0.005
Boundary for River Rch & Prof#=Stream0835,Reach-1,7
Up Type=0
Dn Type=3
Dn Slope=0.005

--- Stream0835.g01 (geometry) ---

Geom Title=Existing Conditions

River Reach=Stream0835,Reach-1
Reach XY= 30
      2479625.00     13565975.00      2479118.95     13566283.16
      2478988.63     13566411.79      2478964.22     13566484.68
      2478780.83     13566672.70      2478721.38     13566873.50
      2478630.85     13566972.71      2478564.24     13567134.68
      2478180.36     13567472.30      2478176.22     13567764.50
      2478273.78     13568035.50      2478275.52     13568309.78
      2478322.73     13568380.94      2478327.25     13568519.07
      2478523.03     13568830.89      2478476.19     13569114.50
      2478672.75     13569480.93      2478677.27     13569619.06
      2478724.48     13569690.22      2478726.20     13570014.50
      2478824.49     13570190.21      2478826.20     13570664.50
      2478930.73     13570877.55      2479158.36     13571058.32
      2479230.83     13571227.31      2479311.76     13571311.39
      2479581.06     13571433.14      2479822.70     13571669.17
      2480131.17     13571782.86      2480775.00     13572375.00

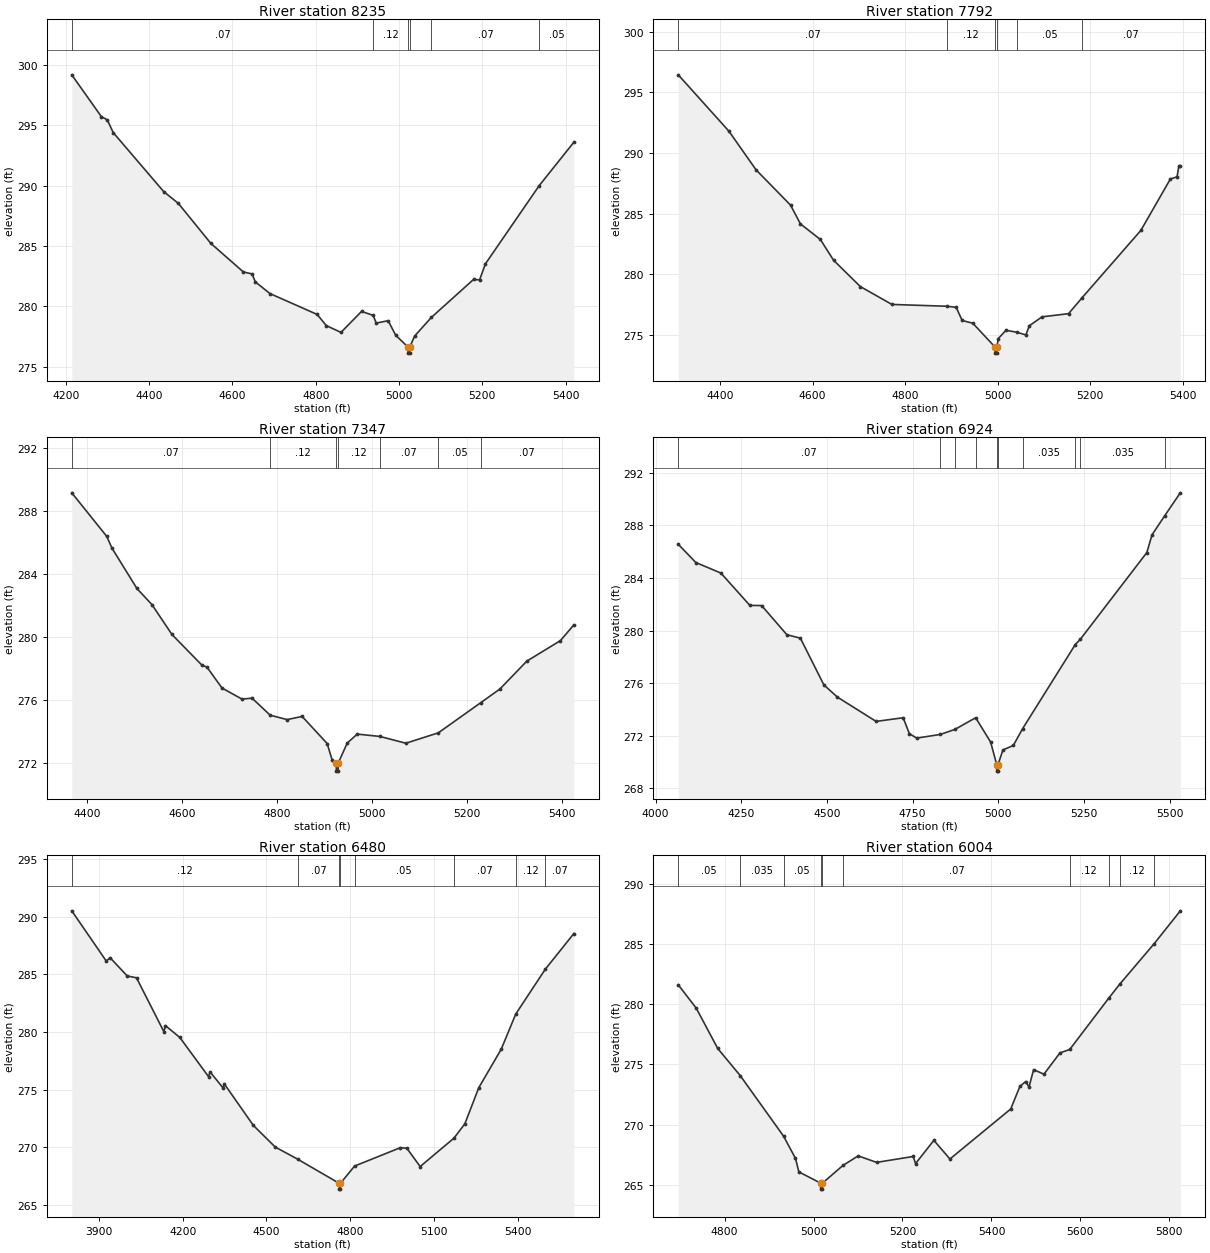
Type RM Length L Ch R = 1,8235,443,443,443
BEGIN DESCRIPTION:
Stream0835 13.0
END DESCRIPTION:
XS GIS Cut Line= 3
      2479025.02     13565425.03      2479525.00     13566025.00
      2479825.03     13566325.03
#Sta/Elev= 30
  4214.4  299.19  4285.3  295.73  4299.6  295.46  4313.9  294.40  4435.0  289.51
  4470.2  288.53  4548.3  285.21  4626.4  282.84  4647.2  282.68  4655.0  282.02
  4690.1  281.05  4803.4  279.32  4825.5  278.39  4860.7  277.83  4910.1  279.57
  4937.9  279.24  4945.3  278.60  4973.9  278.80  4992.1  277.59  5021.7  276.61
  5021.9  276.11  5025.4  276.11  5025.7  276.61  5037.8  277.54  5077.9  279.08
  5179.2  282.23  5193.4  282.18  5207.5  283.52  5336.7  290.01  5419.7  293.60
#Mann=6,-1,0
  4214.4    0.07       0  4937.9    0.12       0  5021.7    0.05       0
  5025.7    0.12       0  5077.9    0.07       0  5336.7    0.05       0
Bank Sta=5021.7,5025.7
Exp/Cntr=0.3,0.1

Type RM Length L Ch R = 1,7792,445,445,445
BEGIN DESCRIPTION:
Stream0835 12.0
END DESCRIPTION:
XS GIS Cut Line= 3
      2478825.01     13565675.02      2479175.00     13566275.00
      2479474.99     13566524.99
#Sta/Elev= 30
  4309.8  296.44  4419.3  291.80  4478.1  288.61  4552.5  285.71  4574.0  284.16
  4617.0  282.88  4645.5  281.17  4703.4  279.00  4771.6  277.53  4890.7  277.38
  4910.5  277.29  4923.4  276.21  4946.5  275.98  4994.5  274.02  4994.8  273.52
  4998.3  273.52  4998.5  274.02  5001.5  274.72  5018.1  275.40  5041.9  275.24
  5061.0  275.02  5068.8  275.78  5096.2  276.51  5153.4  276.77  5182.8  278.09
  5309.7  283.63  5373.4  287.86  5387.8  288.04  5391.7  288.92  5394.9  288.92
#Mann=6,-1,0
  4309.8    0.07       0  4890.7    0.12       0  4994.5    0.05       0
  4998.5    0.12       0  5041.9    0.05       0  5182.8    0.07       0
Bank Sta=4994.5,4998.5
Exp/Cntr=0.3,0.1

Type RM Length L Ch R = 1,7347,423,423,423
BEGIN DESCRIPTION:
Stream0835 11.0
END DESCRIPTION:
XS GIS Cut Line= 3
      2478674.99     13565974.96      2478875.00     13566575.00
      2479175.03     13566875.03
#Sta/Elev= 30
  4367.5  289.14  4441.3  286.37  4451.9  285.64  4504.6  283.07  4536.2  282.05
  4578.4  280.15  4641.6  278.20  4652.1  278.08  4683.8  276.75  4725.9  276.05
  4747.0  276.11  4785.1  275.03  4820.8  274.75  4852.4  274.95  4905.1  273.23
  4915.7  272.17  4924.2  271.98  4924.5  271.48  4928.0  271.48  4928.2  271.98
  4947.3  273.26  4968.4  273.83  5016.3  273.68  5070.7  273.25  5139.1  273.91
  5228.2  275.82  5268.7  276.69  5325.3  278.46  5396.0  279.76  5424.3  280.76
#Mann=7,-1,0
  4367.5    0.07       0  4785.1    0.12       0  4924.2    0.05       0
  4928.2    0.12       0  5016.3    0.07       0  5139.1    0.05       0
  5228.2    0.07       0
Bank Sta=4924.2,4928.2
Exp/Cntr=0.3,0.1

Type RM Length L Ch R = 1,6924,444,444,444
BEGIN DESCRIPTION:
Stream0835 10.0
END DESCRIPTION:
XS GIS Cut Line= 3
      2478425.00     13566025.00      2478675.00     13566925.00
      2479121.07     13567213.67
#Sta/Elev= 30
  4065.9  286.57  4117.3  285.18  4190.4  284.38  4275.0  281.92  4309.3  281.91
  4383.0  279.69  4422.4  279.43  4490.9  275.88  4530.3  274.95  4643.5  273.10
  4722.3  273.38  4740.5  272.17  4761.8  271.83  4830.9  272.11  4873.3  272.49
  4934.0  273.38  4977.7  271.53  4995.4  269.82  4995.6  269.32  4999.1  269.32
  4999.4  269.82  5013.5  270.93  5043.8  271.27  5071.3  272.56  5224.4  278.93
  5239.9  279.36  5433.6  285.94  5448.8  287.29  5486.1  288.75  5531.3  290.48
#Mann=10,-1,0
  4065.9    0.07       0  4830.9    0.12       0  4873.3    0.07       0
  4934.0    0.05       0  4995.4    0.05       0  4999.4    0.05       0
  5071.3   0.035       0  5224.4    0.07       0  5239.9   0.035       0
  5486.1    0.07       0
Bank Sta=4995.4,4999.4
Exp/Cntr=0.3,0.1

Type RM Length L Ch R = 1,6480,476,476,476
BEGIN DESCRIPTION:
Stream0835 9.0
END DESCRIPTION:
XS GIS Cut Line= 3
      2477250.19     13567046.18      2478425.00     13567275.00
      2479025.01     13567275.00
#Sta/Elev= 30
  3803.1  290.51  3926.4  286.16  3940.4  286.44  4001.6  284.86  4034.8  284.70
  4132.9  280.02  4138.0  280.56  4189.6  279.53  4292.9  276.12  4298.0  276.54
  4344.5  275.15  4349.6  275.48  4452.9  271.90  4531.3  270.02  4611.4  268.97
  4760.6  266.87  4760.8  266.37  4764.3  266.37  4764.6  266.87  4815.2  268.37
  4979.6  269.97  5002.5  269.91  5050.0  268.33  5170.9  270.79  5210.0  272.04
  5260.0  275.18  5340.0  278.50  5392.1  281.56  5497.7  285.44  5600.0  288.54
#Mann=8,-1,0
  3803.1    0.12       0  4611.4    0.07       0  4760.6    0.05       0
  4764.6    0.07       0  4815.2    0.05       0  5170.9    0.07       0
  5392.1    0.12       0  5497.7    0.07       0
Bank Sta=4760.6,4764.6
Exp/Cntr=0.3,0.1

Type RM Length L Ch R = 1,6004,482,482,482
BEGIN DESCRIPTION:
Stream0835 8.0
END DESCRIPTION:
XS GIS Cut Line= 3
      2477875.02     13567675.00      2478175.00     13567625.00
      2478974.96     13567425.01
#Sta/Elev= 30
  4695.9  281.60  4736.4  279.66  4784.6  276.32  4835.1  274.07  4932.8  269.03
  4959.5  267.19  4967.1  266.07  5015.9  265.14  5016.2  264.64  5019.9  264.64
  5020.2  265.14  5066.3  266.61  5100.5  267.40  5141.8  266.86  5224.2  267.35
  5229.4  266.76  5270.6  268.69  5306.7  267.14  5443.3  271.29  5463.9  273.16
  5476.8  273.57  5484.5  273.12  5494.8  274.56  5518.0  274.18  5554.1  275.95
  5576.0  276.23  5663.9  280.50  5688.4  281.65  5766.0  285.02  5824.6  287.74
#Mann=10,-1,0
  4695.9    0.05       0  4835.1   0.035       0  4932.8    0.05       0
  5015.9    0.05       0  5020.2    0.05       0  5066.3    0.07       0
  5576.0    0.12       0  5663.9    0.07       0  5688.4    0.12       0
  5766.0    0.07       0
Bank Sta=5015.9,5020.2
Exp/Cntr=0.3,0.1

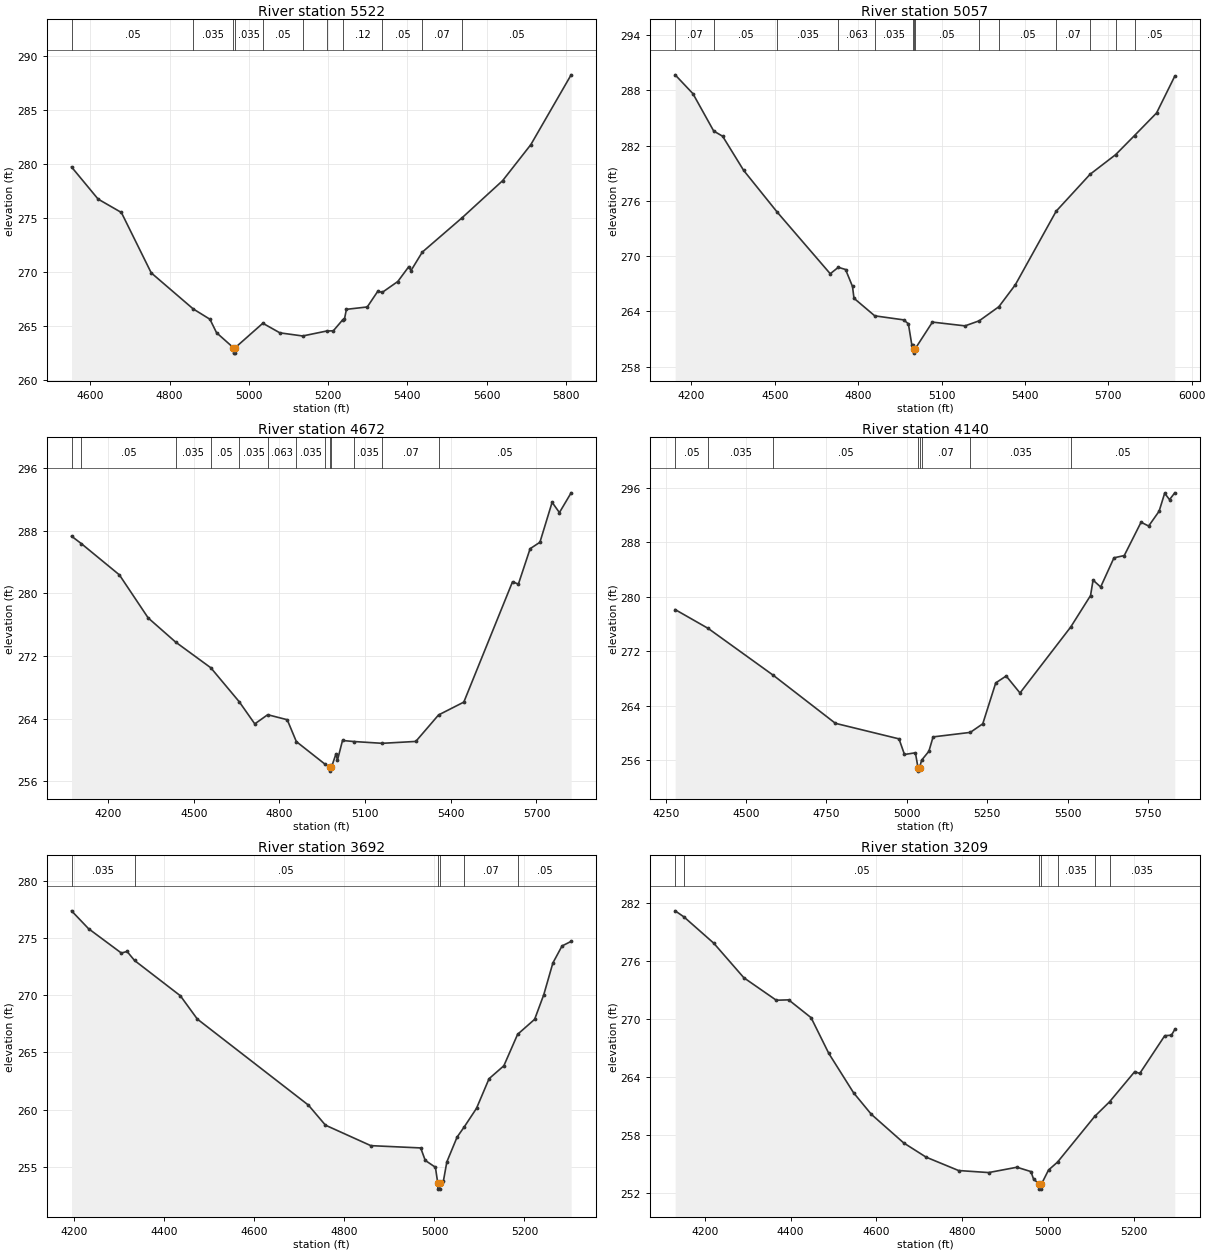
Type RM Length L Ch R = 1,5522,465,465,465
BEGIN DESCRIPTION:
Stream0835 7.0
END DESCRIPTION:
XS GIS Cut Line= 3
      2477875.02     13567875.01      2478275.00     13568075.00
      2479074.97     13567925.01
#Sta/Elev= 30
  4552.4  279.75  4619.5  276.77  4678.2  275.53  4753.6  269.93  4859.5  266.59
  4901.8  265.63  4918.5  264.38  4961.1  262.99  4961.4  262.49  4965.1  262.49
  4965.4  262.99  5035.3  265.26  5078.4  264.37  5135.9  264.08  5196.5  264.54
  5213.2  264.56  5236.5  265.56  5241.2  265.62  5246.3  266.55  5298.9  266.77
  5325.2  268.21  5337.1  268.13  5376.0  269.13  5404.0  270.52  5409.1  270.13
  5437.7  271.85  5538.3  275.04  5640.6  278.48  5711.8  281.82  5813.5  288.29
#Mann=11,-1,0
  4552.4    0.05       0  4859.5   0.035       0  4961.1   0.035       0
  4965.4   0.035       0  5035.3    0.05       0  5135.9    0.07       0
  5196.5    0.05       0  5236.5    0.12       0  5337.1    0.05       0
  5437.7    0.07       0  5538.3    0.05       0
Bank Sta=4961.1,4965.4
Exp/Cntr=0.3,0.1

Type RM Length L Ch R = 1,5057,385,385,385
BEGIN DESCRIPTION:
Stream0835 6.0
END DESCRIPTION:
XS GIS Cut Line= 3
      2477524.97     13568825.01      2478325.00     13568525.00
      2479124.97     13568025.02
#Sta/Elev= 30
  4141.4  289.69  4205.5  287.64  4280.1  283.59  4312.3  283.02  4388.0  279.31
  4508.4  274.79  4699.5  268.09  4728.6  268.79  4754.6  268.55  4779.6  266.71
  4784.9  265.43  4859.6  263.52  4963.8  263.08  4980.7  262.65  4993.2  260.34
  4996.6  260.34  5001.3  259.97  5001.6  259.47  5005.7  259.97  5067.2  262.84
  5184.5  262.43  5235.6  262.98  5306.3  264.51  5365.5  266.89  5512.4  274.88
  5634.5  278.89  5726.4  281.02  5794.5  283.10  5873.8  285.55  5939.2  289.54
#Mann=14,-1,0
  4141.4    0.07       0  4280.1    0.05       0  4508.4   0.035       0
  4728.6   0.063       0  4859.6   0.035       0  4996.6    0.05       0
  5001.3    0.05       0  5005.7    0.05       0  5235.6   0.035       0
  5306.3    0.05       0  5512.4    0.07       0  5634.5    0.05       0
  5726.4    0.07       0  5794.5    0.05       0
Bank Sta=5001.3,5005.7
Exp/Cntr=0.3,0.1

Type RM Length L Ch R = 1,4672,532,532,532
BEGIN DESCRIPTION:
Stream0835 5.0
END DESCRIPTION:
XS GIS Cut Line= 3
      2477608.87     13568873.20      2478281.41     13568783.53
      2479324.95     13569024.99
#Sta/Elev= 30
  4071.8  287.31  4106.4  286.35  4239.4  282.37  4340.3  276.87  4436.4  273.79
  4559.6  270.51  4659.2  266.17  4713.6  263.35  4758.8  264.52  4827.2  263.88
  4859.1  261.09  4959.4  258.21  4977.5  257.82  4977.8  257.32  4982.0  257.82
  4998.0  259.52  5003.1  258.72  5020.8  261.23  5059.7  261.10  5160.0  260.87
  5277.4  261.11  5357.1  264.49  5445.6  266.13  5616.2  281.49  5636.7  281.19
  5677.8  285.71  5712.1  286.53  5754.8  291.63  5780.4  290.32  5821.4  292.84
#Mann=13,-1,0
  4071.8    0.07       0  4106.4    0.05       0  4436.4   0.035       0
  4559.6    0.05       0  4659.2   0.035       0  4758.8   0.063       0
  4859.1   0.035       0  4959.4   0.063       0  4977.5    0.05       0
  4982.0   0.063       0  5059.7   0.035       0  5160.0    0.07       0
  5357.1    0.05       0
Bank Sta=4977.5,4982
Exp/Cntr=0.3,0.1

Type RM Length L Ch R = 1,4140,448,448,448
BEGIN DESCRIPTION:
Stream0835 4.0
END DESCRIPTION:
XS GIS Cut Line= 3
      2477875.04     13569474.99      2478575.00     13569325.00
      2479375.00     13569075.00
#Sta/Elev= 30
  4279.6  278.12  4382.6  275.35  4585.0  268.48  4778.1  261.44  4975.9  259.16
  4992.9  256.87  5026.9  257.12  5035.0  254.93  5035.4  254.43  5039.7  254.93
  5046.3  256.04  5068.8  257.34  5081.9  259.45  5197.6  260.11  5236.4  261.37
  5276.8  267.37  5309.2  268.38  5352.2  265.89  5510.1  275.57  5571.7  280.18
  5579.5  282.44  5603.1  281.43  5644.5  285.71  5676.5  286.04  5728.8  290.93
  5752.4  290.37  5784.9  292.54  5802.2  295.18  5817.4  294.24  5833.6  295.24
#Mann=8,-1,0
  4279.6    0.05       0  4382.6   0.035       0  4585.0    0.05       0
  5035.0    0.05       0  5039.7    0.05       0  5046.3    0.07       0
  5197.6   0.035       0  5510.1    0.05       0
Bank Sta=5035,5039.7
Exp/Cntr=0.3,0.1

Type RM Length L Ch R = 1,3692,483,483,483
BEGIN DESCRIPTION:
Stream0835 3.0
END DESCRIPTION:
XS GIS Cut Line= 3
      2477925.02     13569825.00      2478725.00     13569725.00
      2479024.96     13569675.01
#Sta/Elev= 30
  4193.4  277.38  4231.2  275.82  4304.2  273.69  4316.8  273.83  4333.5  273.04
  4435.2  269.96  4473.0  267.92  4719.9  260.40  4757.7  258.65  4858.5  256.86
  4969.4  256.66  4979.5  255.57  5002.1  254.97  5007.4  253.56  5007.7  253.06
  5011.7  253.06  5012.1  253.56  5019.9  253.78  5027.5  255.44  5050.3  257.61
  5066.7  258.53  5093.4  260.12  5121.3  262.71  5154.2  263.84  5184.8  266.59
  5222.6  267.90  5242.9  270.05  5263.2  272.83  5283.5  274.31  5303.7  274.71
#Mann=6,-1,0
  4193.4   0.035       0  4333.5    0.05       0  5007.4    0.05       0
  5012.1    0.05       0  5066.7    0.07       0  5184.8    0.05       0
Bank Sta=5007.4,5012.1
Exp/Cntr=0.3,0.1

Type RM Length L Ch R = 1,3209,449,449,449
BEGIN DESCRIPTION:
Stream0835 2.0
END DESCRIPTION:
XS GIS Cut Line= 3
      2478025.04     13570524.98      2478825.00     13570175.00
      2479074.99     13570025.01
#Sta/Elev= 30
  4130.9  281.18  4151.5  280.55  4220.9  277.84  4291.1  274.27  4366.7  271.95
  4395.5  271.99  4447.8  270.15  4489.1  266.46  4546.8  262.40  4588.1  260.18
  4663.7  257.22  4716.0  255.75  4791.6  254.37  4861.8  254.16  4927.7  254.71
  4960.4  254.26  4966.3  253.50  4979.9  252.95  4980.2  252.45  4984.3  252.45
  4984.6  252.95  5001.3  254.42  5022.3  255.24  5109.0  259.96  5143.5  261.46
  5202.3  264.58  5214.0  264.39  5272.3  268.29  5287.8  268.34  5295.6  268.93
#Mann=7,-1,0
  4130.9   0.035       0  4151.5    0.05       0  4979.9    0.05       0
  4984.6    0.05       0  5022.3   0.035       0  5109.0    0.05       0
  5143.5   0.035       0
Bank Sta=4979.9,4984.6
Exp/Cntr=0.3,0.1

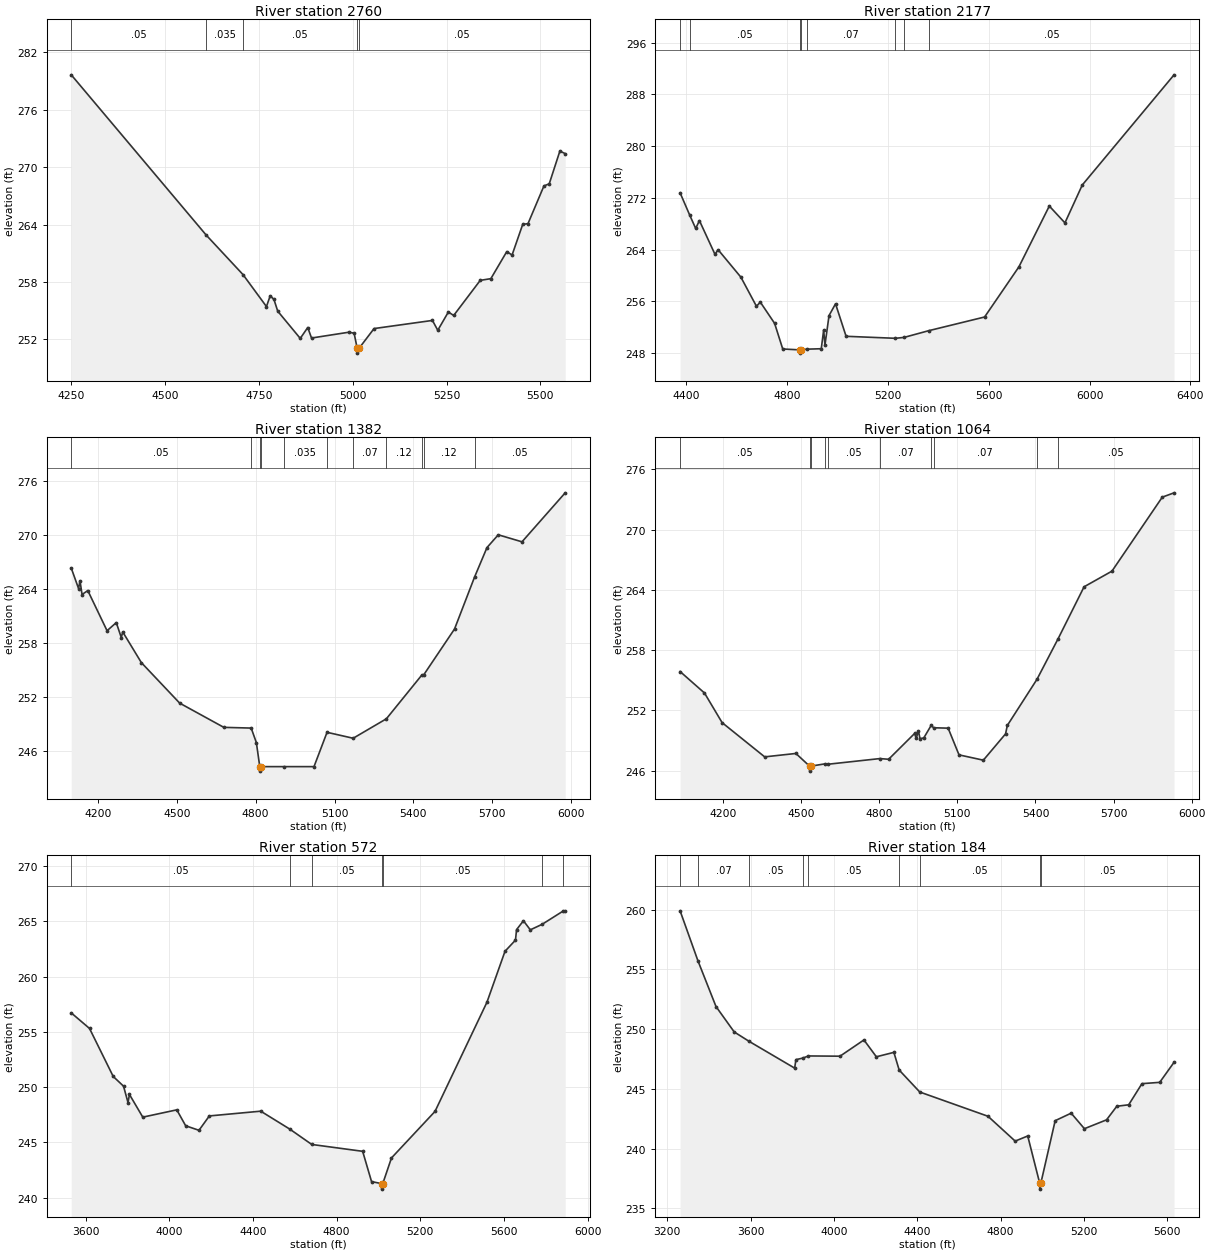
Type RM Length L Ch R = 1,2760,583,583,583
BEGIN DESCRIPTION:
Stream0835 1.0
END DESCRIPTION:
XS GIS Cut Line= 3
      2478075.02     13570625.00      2478825.00     13570625.00
      2479225.02     13570224.98
#Sta/Elev= 30
  4250.4  279.66  4609.6  262.91  4708.0  258.76  4770.4  255.42  4780.4  256.55
  4790.4  256.16  4800.4  254.94  4860.4  252.09  4880.4  253.23  4890.4  252.13
  4990.4  252.74  5003.9  252.63  5012.1  251.05  5012.5  250.55  5016.9  251.05
  5057.0  253.12  5212.5  253.97  5226.7  252.94  5254.9  254.85  5269.1  254.49
  5339.8  258.16  5368.1  258.34  5410.5  261.17  5424.6  260.81  5452.9  264.01
  5467.1  264.10  5509.5  268.04  5523.6  268.26  5551.9  271.68  5566.1  271.42
#Mann=5,-1,0
  4250.4    0.05       0  4609.6   0.035       0  4708.0    0.05       0
  5012.1    0.05       0  5016.9    0.05       0
Bank Sta=5012.1,5016.9
Exp/Cntr=0.3,0.1

Type RM Length L Ch R = 1,2177,795,795,795
BEGIN DESCRIPTION:
XS7809
END DESCRIPTION:
XS GIS Cut Line= 2
      2478550.43     13571204.61      2480455.89     13570745.05
#Sta/Elev= 30
  4374.9  272.78  4412.6  269.38  4436.7  267.28  4451.6  268.49  4513.3  263.28
  4525.6  264.00  4616.2  259.75  4677.9  255.26  4693.2  255.90  4749.9  252.62
  4782.2  248.66  4850.3  248.52  4850.7  248.02  4855.2  248.52  4877.0  248.63
  4935.1  248.70  4944.6  251.59  4949.8  249.29  4965.9  253.82  4991.7  255.64
  5033.6  250.62  5229.6  250.31  5263.7  250.45  5361.8  251.49  5583.2  253.60
  5719.4  261.35  5840.0  270.74  5902.0  268.14  5970.8  273.99  6335.0  291.01
#Mann=8,-1,0
  4374.9   0.035       0  4412.6    0.05       0  4850.3    0.05       0
  4855.2    0.05       0  4877.0    0.07       0  5229.6    0.05       0
  5263.7    0.07       0  5361.8    0.05       0
Bank Sta=4850.3,4855.2
Exp/Cntr=0.3,0.1

Type RM Length L Ch R = 1,1382,318,318,318
BEGIN DESCRIPTION:
XS7808
END DESCRIPTION:
XS GIS Cut Line= 3
      2478886.68     13571428.78      2479514.37     13571675.37
      2480556.80     13571070.09
#Sta/Elev= 30
  4098.1  266.34  4126.0  264.06  4131.3  264.93  4139.3  263.40  4161.1  263.84
  4234.4  259.38  4269.5  260.28  4288.6  258.62  4294.0  259.25  4364.9  255.84
  4510.8  251.34  4678.8  248.65  4782.9  248.57  4802.6  246.96  4815.6  244.29
  4816.0  243.79  4821.0  244.29  4906.2  244.29  5022.0  244.29  5071.6  248.10
  5171.0  247.44  5297.4  249.60  5431.8  254.44  5440.2  254.51  5556.8  259.57
  5632.9  265.33  5680.2  268.61  5723.2  270.03  5813.5  269.25  5977.9  274.69
#Mann=11,-1,0
  4098.1    0.05       0  4782.9    0.07       0  4815.6   0.035       0
  4821.0    0.07       0  4906.2   0.035       0  5071.6    0.05       0
  5171.0    0.07       0  5297.4    0.12       0  5431.8    0.07       0
  5440.2    0.12       0  5632.9    0.05       0
Bank Sta=4815.6,4821
Exp/Cntr=0.3,0.1

Type RM Length L Ch R = 1,1064,492,492,492
BEGIN DESCRIPTION:
XS7807a
END DESCRIPTION:
XS GIS Cut Line= 4
      2479164.82     13571579.57      2479833.56     13571903.90
      2480206.68     13571413.10      2480645.83     13571103.11
#Sta/Elev= 30
  4035.1  255.87  4128.8  253.73  4196.5  250.78  4360.0  247.37  4479.9  247.71
  4532.3  246.45  4532.8  245.95  4537.8  246.45  4592.9  246.68  4604.3  246.64
  4802.5  247.20  4836.0  247.13  4935.8  249.70  4942.1  249.21  4950.4  249.96
  4956.7  249.18  4971.2  249.26  4999.6  250.51  5008.8  250.27  5064.7  250.23
  5106.4  247.57  5199.9  247.04  5285.2  249.66  5292.0  250.50  5406.0  255.10
  5487.1  259.14  5586.8  264.31  5693.9  265.87  5887.2  273.24  5932.4  273.67
#Mann=10,-1,0
  4035.1    0.05       0  4532.3   0.035       0  4537.8    0.05       0
  4592.9    0.07       0  4604.3    0.05       0  4802.5    0.07       0
  4999.6   0.035       0  5008.8    0.07       0  5406.0    0.12       0
  5487.1    0.05       0
Bank Sta=4532.3,4537.8
Exp/Cntr=0.3,0.1

Type RM Length L Ch R = 1,572,388,388,388
BEGIN DESCRIPTION:
XS7807
END DESCRIPTION:
XS GIS Cut Line= 4
      2479166.91     13571619.34      2479749.75     13572190.97
      2480556.78     13571910.76      2480758.45     13571249.70
#Sta/Elev= 30
  3531.1  256.71  3618.6  255.30  3731.8  250.96  3781.2  250.08  3802.5  248.60
  3809.5  249.33  3873.2  247.28  4035.8  247.94  4078.2  246.50  4141.9  246.09
  4191.4  247.39  4437.2  247.82  4575.9  246.20  4681.1  244.81  4924.5  244.19
  4967.0  241.45  5015.1  241.27  5015.5  240.77  5020.7  241.27  5062.3  243.59
  5270.5  247.80  5518.7  257.67  5605.1  262.28  5655.2  263.29  5660.4  264.24
  5693.3  265.04  5726.1  264.22  5782.6  264.72  5884.8  265.94  5892.9  265.90
#Mann=7,-1,0
  3531.1    0.05       0  4575.9   0.035       0  4681.1    0.05       0
  5015.1    0.05       0  5020.7    0.05       0  5782.6   0.035       0
  5884.8    0.05       0
Bank Sta=5015.1,5020.7
Exp/Cntr=0.3,0.1

Type RM Length L Ch R = 1,184,0,0,0
BEGIN DESCRIPTION:
H21126
END DESCRIPTION:
XS GIS Cut Line= 4
      2479060.45     13571800.00      2479851.15     13572311.63
      2480749.39     13572236.05      2481144.70     13571887.25
#Sta/Elev= 30
  3261.7  259.90  3347.0  255.73  3433.9  251.89  3521.3  249.76  3592.1  248.98
  3811.5  246.73  3817.4  247.44  3850.3  247.57  3877.8  247.75  4029.1  247.73
  4143.9  249.09  4203.5  247.68  4287.6  248.05  4313.0  246.57  4411.9  244.73
  4739.2  242.70  4869.7  240.62  4929.9  241.05  4987.3  237.10  4987.8  236.60
  4992.9  237.10  5061.6  242.33  5138.3  242.96  5201.9  241.66  5308.1  242.40
  5357.5  243.54  5414.4  243.66  5478.0  245.43  5563.3  245.54  5632.1  247.22
#Mann=9,-1,0
  3261.7    0.05       0  3347.0    0.07       0  3592.1    0.05       0
  3850.3    0.07       0  3877.8    0.05       0  4313.0   0.035       0
  4411.9    0.05       0  4987.3    0.05       0  4992.9    0.05       0
Bank Sta=4987.3,4992.9
Exp/Cntr=0.3,0.1

Chan Stop Cuts=-1