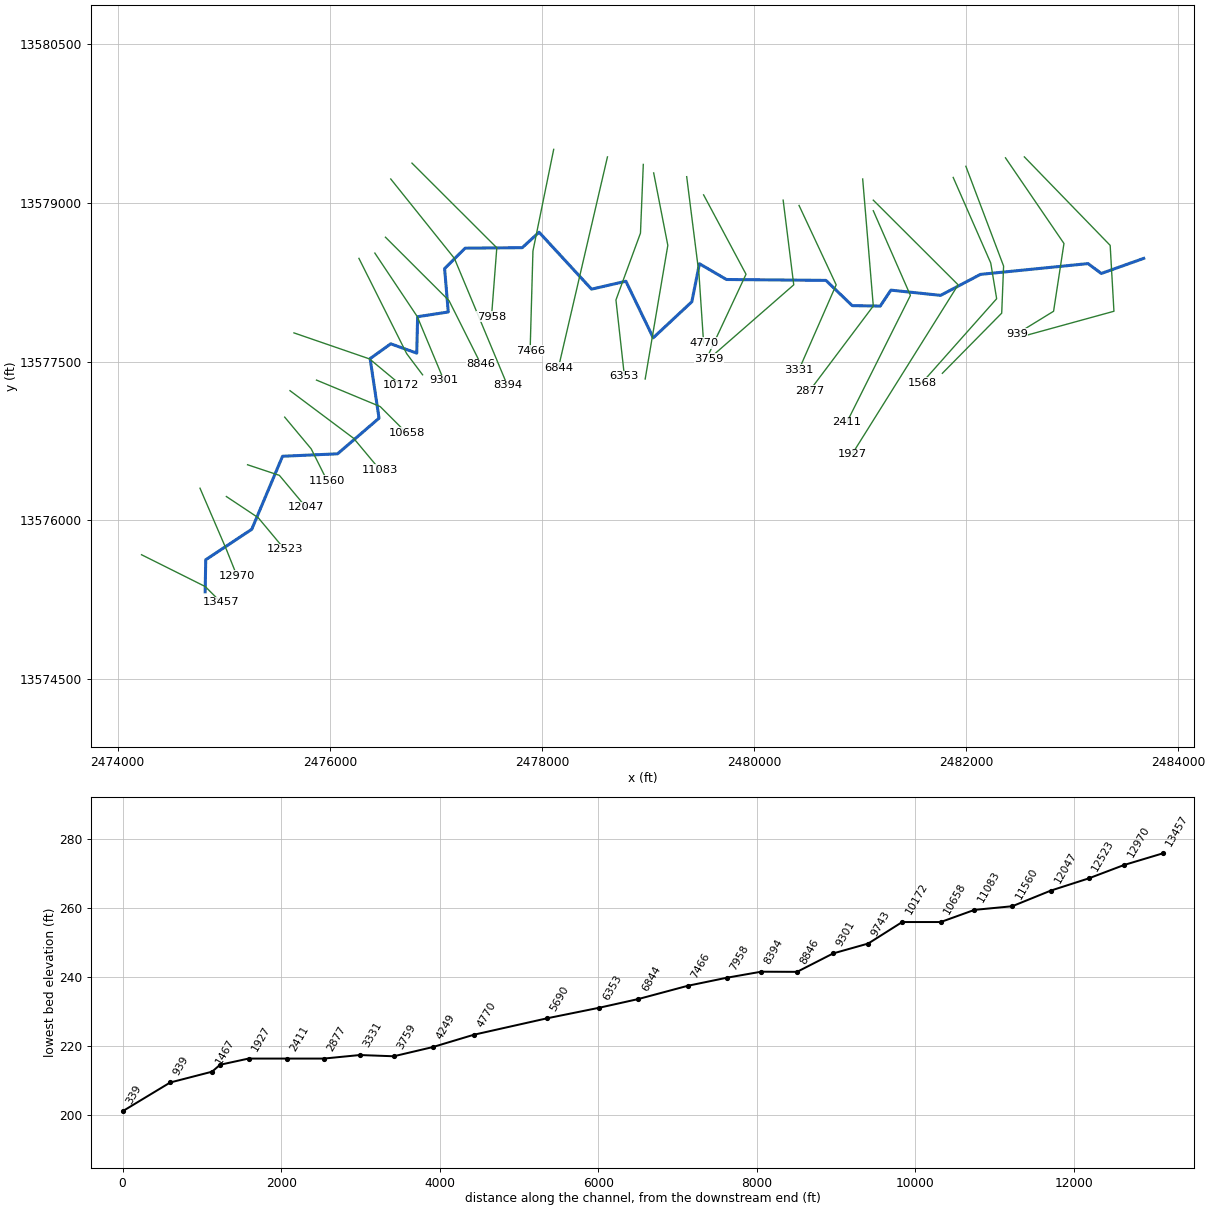
--- Stream0836.prj (project) ---

Proj Title=Stream0836 Base Level Engineering
Current Plan=p01
Default Exp/Contr=0.3,0.1
English Units
Geom File=g01
Flow File=f01
Plan File=p01
BEGIN DESCRIPTION:
Stream0836
END DESCRIPTION:

--- Stream0836.p01 (plan) ---

Plan Title=Multiple Run
Short Identifier=Multiple
Geom File=g01
Flow File=f01
Subcritical Flow
K Sum by GR= 0
Std Step Tol= 0.01
Critical Tol= 0.01
Num of Std Step Trials= 20
Max Error Tol= 0.3
Flow Tol Ratio= 0.001
Split Flow NTrial= 30
Split Flow Tol= 0.02
Split Flow Ratio= 0.02
Log Output Level= 0
Friction Slope Method= 1
Unsteady Friction Slope Method= 2
Unsteady Bridges Friction Slope Method= 1
Parabolic Critical Depth
Global Vel Dist=  1 , 1 , 1
Global Log Level= 0
CheckData=True
Encroach Param= -1, 0, 0, 0
BEGIN DESCRIPTION:
Multiple Run
END DESCRIPTION:

--- Stream0836.f01 (steady flow) ---

Flow Title=Multiple
Number of Profiles=7
Profile Names=10-year,25-year,50-year,1pct_min,100-year,1pct_plu,500-year
River Rch & RM= Stream0836,Reach-1,13457
     406     637     839     536    1070    2136    1724
River Rch & RM= Stream0836,Reach-1,12047
     664    1069    1435     932    1860    3711    3096
River Rch & RM= Stream0836,Reach-1,8394
    1017    1675    2280    1500    2993    5972    5115
River Rch & RM= Stream0836,Reach-1,2411
    1119    1851    2528    1669    3329    6643    5723
Boundary for River Rch & Prof#=Stream0836,Reach-1,1
Up Type=0
Dn Type=3
Dn Slope=0.005
Boundary for River Rch & Prof#=Stream0836,Reach-1,2
Up Type=0
Dn Type=3
Dn Slope=0.005
Boundary for River Rch & Prof#=Stream0836,Reach-1,3
Up Type=0
Dn Type=3
Dn Slope=0.005
Boundary for River Rch & Prof#=Stream0836,Reach-1,4
Up Type=0
Dn Type=3
Dn Slope=0.005
Boundary for River Rch & Prof#=Stream0836,Reach-1,5
Up Type=0
Dn Type=3
Dn Slope=0.005
Boundary for River Rch & Prof#=Stream0836,Reach-1,6
Up Type=0
Dn Type=3
Dn Slope=0.005
Boundary for River Rch & Prof#=Stream0836,Reach-1,7
Up Type=0
Dn Type=3
Dn Slope=0.005

--- Stream0836.g01 (geometry) ---

Geom Title=Existing Conditions

River Reach=Stream0836,Reach-1
Reach XY= 30
      2474825.00     13575325.00      2474830.45     13575627.47
      2475264.22     13575915.32      2475554.47     13576605.29
      2476073.50     13576628.46      2476464.53     13576965.18
      2476380.36     13577527.70      2476574.92     13577667.70
      2476819.97     13577579.92      2476828.45     13577923.81
      2477117.33     13577968.47      2477082.79     13578378.42
      2477276.46     13578571.46      2477814.71     13578575.97
      2477973.54     13578722.01      2478468.26     13578184.13
      2478792.14     13578258.97      2479049.91     13577724.37
      2479413.90     13578064.94      2479485.62     13578424.41
      2479740.17     13578275.37      2480678.32     13578266.96
      2480926.25     13578028.45      2481190.56     13578024.36
      2481291.00     13578174.77      2481759.79     13578125.51
      2482135.50     13578323.78      2483149.92     13578425.61
      2483274.90     13578332.33      2483675.00     13578475.00

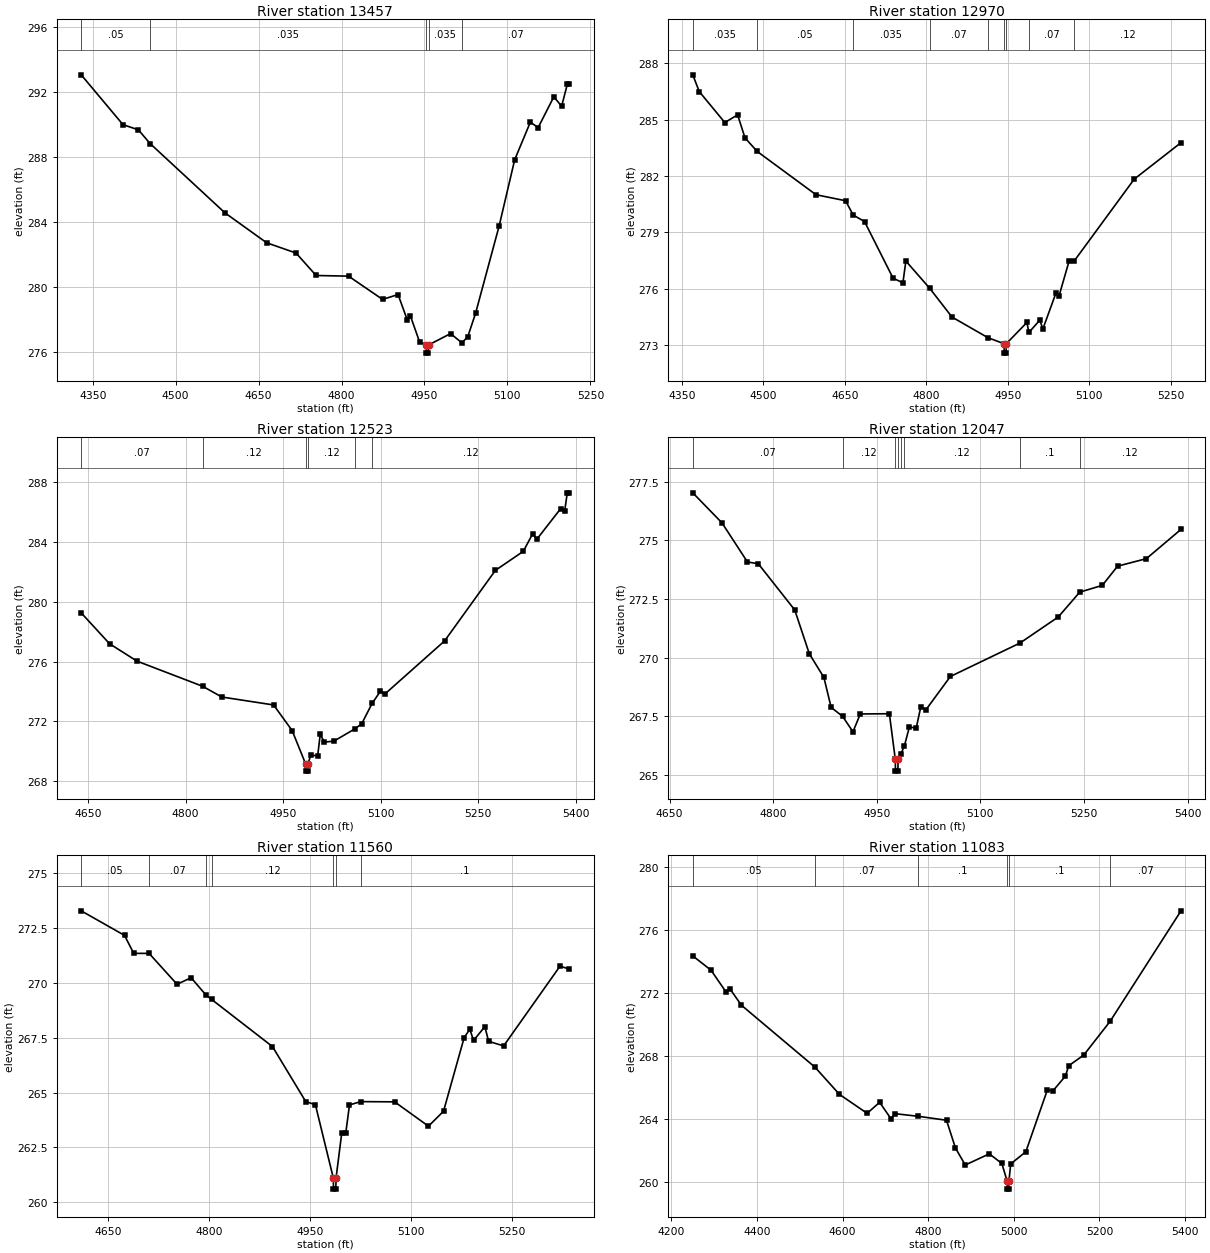
Type RM Length L Ch R = 1,13457,487,487,487
BEGIN DESCRIPTION:
Stream0836 21.0
END DESCRIPTION:
XS GIS Cut Line= 3
      2474225.01     13575675.00      2474825.00     13575375.00
      2474974.97     13575225.03
#Sta/Elev= 30
  4329.2  293.05  4404.7  289.99  4432.6  289.67  4453.7  288.83  4589.1  284.57
  4664.6  282.73  4717.7  282.10  4754.0  280.72  4812.7  280.68  4874.2  279.25
  4902.2  279.55  4919.0  277.98  4924.5  278.24  4941.3  276.62  4953.3  276.45
  4953.5  275.95  4957.0  275.95  4957.3  276.45  4997.2  277.15  5017.7  276.58
  5028.3  276.96  5042.4  278.40  5084.9  283.75  5113.1  287.83  5141.4  290.14
  5155.6  289.81  5183.9  291.70  5198.0  291.12  5208.6  292.51  5212.1  292.51
#Mann=5,-1,0
  4329.2    0.05       0  4453.7   0.035       0  4953.3   0.035       0
  4957.3   0.035       0  5017.7    0.07       0
Bank Sta=4953.3,4957.3
Exp/Cntr=0.3,0.1

Type RM Length L Ch R = 1,12970,447,447,447
BEGIN DESCRIPTION:
Stream0836 20.0
END DESCRIPTION:
XS GIS Cut Line= 3
      2474776.37     13576303.39      2475025.00     13575725.00
      2475124.99     13575475.02
#Sta/Elev= 30
  4370.1  287.39  4382.0  286.50  4429.1  284.85  4452.6  285.26  4466.3  284.03
  4488.8  283.31  4596.9  281.01  4651.3  280.69  4665.4  279.93  4686.3  279.58
  4738.8  276.57  4756.9  276.32  4762.4  277.48  4806.0  276.04  4847.3  274.50
  4913.6  273.40  4943.2  273.08  4943.5  272.58  4947.0  272.58  4947.2  273.08
  4985.2  274.21  4988.9  273.68  5009.1  274.34  5014.5  273.86  5038.7  275.78
  5044.1  275.60  5062.9  277.48  5072.2  277.48  5182.8  281.84  5268.9  283.78
#Mann=9,-1,0
  4370.1   0.035       0  4488.8    0.05       0  4665.4   0.035       0
  4806.0    0.07       0  4913.6    0.12       0  4943.2    0.05       0
  4947.2    0.12       0  4988.9    0.07       0  5072.2    0.12       0
Bank Sta=4943.2,4947.2
Exp/Cntr=0.3,0.1

Type RM Length L Ch R = 1,12523,476,476,476
BEGIN DESCRIPTION:
Stream0836 19.0
END DESCRIPTION:
XS GIS Cut Line= 3
      2475024.98     13576225.01      2475325.00     13576025.00
      2475575.01     13575724.99
#Sta/Elev= 30
  4639.4  279.25  4683.0  277.19  4725.1  276.03  4826.1  274.35  4855.8  273.63
  4935.4  273.10  4963.9  271.39  4984.5  269.18  4984.7  268.68  4988.2  268.68
  4988.5  269.18  4992.5  269.75  5003.2  269.70  5007.1  271.13  5013.6  270.62
  5028.0  270.68  5060.3  271.50  5070.9  271.84  5086.9  273.20  5099.6  274.01
  5106.1  273.81  5198.5  277.38  5276.6  282.09  5319.5  283.36  5333.9  284.53
  5340.4  284.17  5376.8  286.20  5383.3  286.08  5387.2  287.27  5390.5  287.27
#Mann=6,-1,0
  4639.4    0.07       0  4826.1    0.12       0  4984.5    0.05       0
  4988.5    0.12       0  5060.3     0.1       0  5086.9    0.12       0
Bank Sta=4984.5,4988.5
Exp/Cntr=0.3,0.1

Type RM Length L Ch R = 1,12047,487,487,487
BEGIN DESCRIPTION:
Stream0836 18.0
END DESCRIPTION:
XS GIS Cut Line= 3
      2475224.96     13576525.01      2475525.00     13576425.00
      2475775.01     13576124.99
#Sta/Elev= 30
  4683.6  277.03  4725.8  275.75  4762.7  274.08  4778.5  274.00  4831.2  272.03
  4852.3  270.16  4873.4  269.15  4883.9  267.87  4900.4  267.49  4915.5  266.83
  4926.1  267.59  4968.2  267.60  4976.8  265.65  4977.0  265.15  4980.5  265.15
  4980.8  265.65  4984.5  265.87  4989.8  266.21  4997.2  267.04  5007.0  266.98
  5013.5  267.87  5021.4  267.78  5056.5  269.19  5157.4  270.62  5212.7  271.73
  5243.8  272.79  5276.5  273.08  5298.6  273.90  5340.3  274.22  5390.4  275.47
#Mann=8,-1,0
  4683.6    0.07       0  4900.4    0.12       0  4976.8    0.05       0
  4980.8    0.12       0  4984.5     0.1       0  4989.8    0.12       0
  5157.4     0.1       0  5243.8    0.12       0
Bank Sta=4976.8,4980.8
Exp/Cntr=0.3,0.1

Type RM Length L Ch R = 1,11560,477,477,477
BEGIN DESCRIPTION:
Stream0836 17.0
END DESCRIPTION:
XS GIS Cut Line= 3
      2475574.99     13576975.01      2475825.00     13576675.00
      2475974.99     13576375.03
#Sta/Elev= 30
  4609.6  273.29  4674.0  272.17  4687.7  271.35  4710.5  271.35  4752.1  269.94
  4773.0  270.24  4795.4  269.44  4803.5  269.25  4894.0  267.10  4943.5  264.59
  4957.8  264.45  4984.5  261.10  4984.7  260.60  4988.2  260.60  4988.5  261.10
  4996.9  263.14  5002.9  263.14  5008.5  264.44  5025.3  264.59  5075.6  264.58
  5125.9  263.47  5148.3  264.15  5179.0  267.51  5187.4  267.89  5193.0  267.38
  5209.8  268.01  5215.3  267.34  5237.7  267.13  5321.6  270.77  5335.5  270.63
#Mann=7,-1,0
  4609.6    0.05       0  4710.5    0.07       0  4795.4    0.05       0
  4803.5    0.12       0  4984.5    0.05       0  4988.5    0.12       0
  5025.3     0.1       0
Bank Sta=4984.5,4988.5
Exp/Cntr=0.3,0.1

Type RM Length L Ch R = 1,11083,425,425,425
BEGIN DESCRIPTION:
Stream0836 16.0
END DESCRIPTION:
XS GIS Cut Line= 3
      2475624.98     13577225.01      2476225.00     13576775.00
      2476474.98     13576475.03
#Sta/Elev= 30
  4250.0  274.34  4292.7  273.43  4328.1  272.03  4336.5  272.26  4363.6  271.21
  4535.4  267.28  4592.7  265.55  4657.3  264.35  4686.5  265.05  4713.6  263.98
  4721.9  264.33  4777.0  264.16  4842.7  263.91  4863.6  262.15  4886.5  261.07
  4942.7  261.78  4971.9  261.17  4984.5  260.04  4984.7  259.54  4988.2  259.54
  4988.5  260.04  4992.7  261.14  5028.0  261.91  5078.1  265.82  5091.8  265.79
  5120.4  266.71  5128.2  267.37  5163.4  268.05  5224.7  270.18  5390.5  277.20
#Mann=6,-1,0
  4250.0    0.05       0  4535.4    0.07       0  4777.0     0.1       0
  4984.5    0.05       0  4988.5     0.1       0  5224.7    0.07       0
Bank Sta=4984.5,4988.5
Exp/Cntr=0.3,0.1

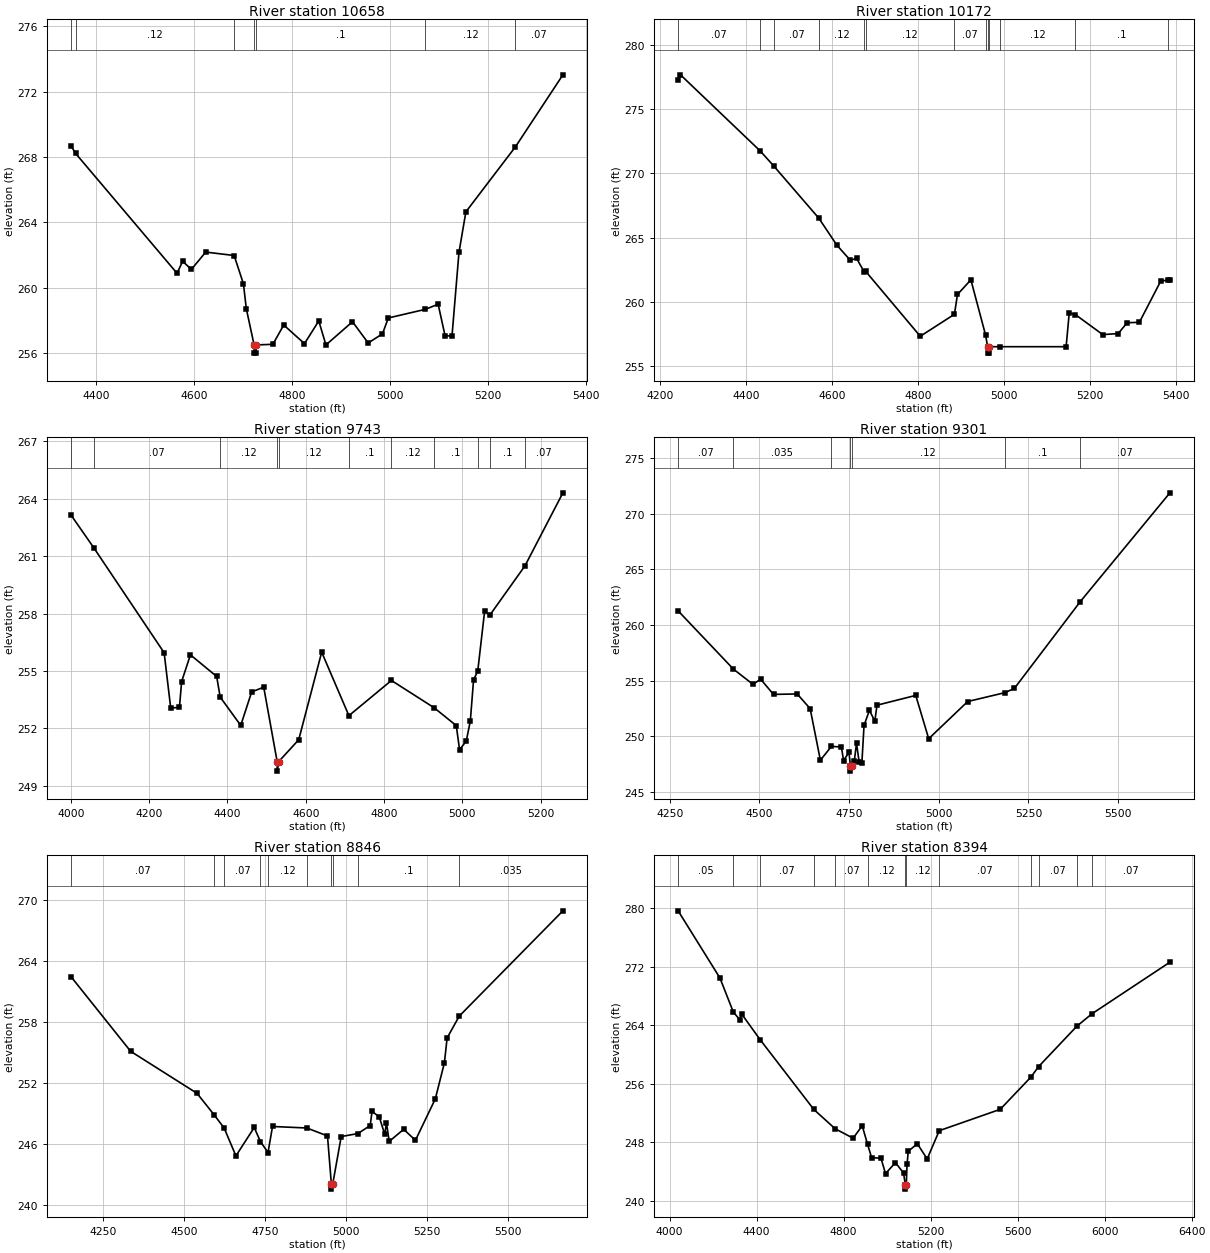
Type RM Length L Ch R = 1,10658,486,486,486
BEGIN DESCRIPTION:
Stream0836 15.0
END DESCRIPTION:
XS GIS Cut Line= 3
      2475874.96     13577325.02      2476475.00     13577075.00
      2476725.00     13576825.00
#Sta/Elev= 30
  4349.8  268.68  4359.0  268.22  4566.0  260.89  4577.3  261.63  4595.2  261.13
  4624.5  262.19  4682.5  261.98  4701.4  260.25  4707.3  258.73  4723.2  256.51
  4723.5  256.01  4727.0  256.01  4727.2  256.51  4761.5  256.55  4783.7  257.73
  4826.0  256.59  4855.2  257.98  4869.8  256.51  4924.0  257.93  4956.0  256.63
  4985.2  257.19  4997.1  258.16  5072.9  258.69  5098.8  259.00  5113.0  257.06
  5127.1  257.07  5141.3  262.17  5155.4  264.65  5256.6  268.63  5353.4  273.03
#Mann=7,-1,0
  4349.8    0.05       0  4359.0    0.12       0  4682.5     0.1       0
  4723.2    0.05       0  4727.2     0.1       0  5072.9    0.12       0
  5256.6    0.07       0
Bank Sta=4723.2,4727.2
Exp/Cntr=0.3,0.1

Type RM Length L Ch R = 1,10172,429,429,429
BEGIN DESCRIPTION:
Stream0836 14.0
END DESCRIPTION:
XS GIS Cut Line= 3
      2475662.28     13577770.96      2476375.00     13577525.00
      2476675.02     13577274.98
#Sta/Elev= 30
  4242.1  277.25  4247.6  277.65  4432.8  271.74  4464.7  270.56  4569.8  266.49
  4611.4  264.41  4642.6  263.24  4657.5  263.37  4674.9  262.34  4678.8  262.36
  4805.6  257.32  4885.1  259.03  4892.2  260.57  4923.4  261.71  4957.8  257.39
  4962.3  256.51  4962.6  256.01  4966.1  256.01  4966.3  256.51  4990.1  256.51
  5145.1  256.51  5152.3  259.14  5166.8  259.00  5230.4  257.45  5266.2  257.53
  5287.0  258.37  5315.6  258.41  5365.1  261.60  5382.1  261.70  5386.6  261.69
#Mann=13,-1,0
  4242.1    0.07       0  4432.8    0.12       0  4464.7    0.07       0
  4569.8    0.12       0  4674.9    0.07       0  4678.8    0.12       0
  4885.1    0.07       0  4957.8     0.1       0  4962.3    0.05       0
  4966.3     0.1       0  4990.1    0.12       0  5166.8     0.1       0
  5382.1    0.12       0
Bank Sta=4962.3,4966.3
Exp/Cntr=0.3,0.1

Type RM Length L Ch R = 1,9743,442,442,442
BEGIN DESCRIPTION:
Stream0836 13.0
END DESCRIPTION:
XS GIS Cut Line= 3
      2476274.98     13578475.03      2476725.00     13577575.00
      2476875.02     13577374.97
#Sta/Elev= 30
  4000.6  263.14  4058.4  261.44  4238.2  255.95  4255.0  253.06  4277.3  253.09
  4282.9  254.44  4305.3  255.84  4372.4  254.71  4381.4  253.63  4433.9  252.15
  4461.8  253.90  4492.6  254.15  4526.9  250.26  4527.2  249.76  4530.9  250.26
  4582.0  251.40  4640.7  255.98  4710.2  252.66  4818.8  254.50  4927.5  253.08
  4984.5  252.14  4992.9  250.88  5010.0  251.33  5020.4  252.38  5028.7  254.54
  5039.3  254.98  5056.9  258.12  5070.1  257.91  5159.9  260.49  5256.9  264.31
#Mann=11,-1,0
  4000.6   0.035       0  4058.4    0.07       0  4381.4    0.12       0
  4526.9    0.05       0  4530.9    0.12       0  4710.2     0.1       0
  4818.8    0.12       0  4927.5     0.1       0  5039.3    0.12       0
  5070.1     0.1       0  5159.9    0.07       0
Bank Sta=4526.9,4530.9
Exp/Cntr=0.3,0.1

Type RM Length L Ch R = 1,9301,455,455,455
BEGIN DESCRIPTION:
Stream0836 12.0
END DESCRIPTION:
XS GIS Cut Line= 3
      2476424.99     13578525.02      2476825.00     13577925.00
      2477074.99     13577325.03
#Sta/Elev= 30
  4273.3  261.28  4427.4  256.05  4482.1  254.68  4503.2  255.15  4539.2  253.78
  4605.3  253.82  4641.4  252.50  4669.9  247.87  4700.7  249.11  4728.5  249.06
  4734.5  247.84  4749.6  248.58  4753.6  247.39  4753.8  246.89  4757.6  247.39
  4764.6  247.83  4770.6  249.39  4778.1  247.68  4785.6  247.64  4791.6  250.99
  4806.6  252.35  4821.7  251.38  4827.7  252.81  4935.8  253.69  4971.9  249.80
  5080.6  253.14  5183.5  253.93  5210.6  254.31  5394.5  262.11  5644.4  271.88
#Mann=7,-1,0
  4273.3    0.07       0  4427.4   0.035       0  4700.7    0.12       0
  4753.6    0.05       0  4757.6    0.12       0  5183.5     0.1       0
  5394.5    0.07       0
Bank Sta=4753.6,4757.6
Exp/Cntr=0.3,0.1

Type RM Length L Ch R = 1,8846,452,452,452
BEGIN DESCRIPTION:
Stream0836 11.0
END DESCRIPTION:
XS GIS Cut Line= 3
      2476525.01     13578674.99      2477125.00     13578075.00
      2477424.98     13577475.04
#Sta/Elev= 30
  4151.3  262.41  4335.1  255.09  4540.2  250.96  4593.2  248.84  4624.1  247.54
  4660.4  244.81  4717.0  247.60  4736.3  246.20  4759.6  245.14  4773.5  247.70
  4879.5  247.55  4943.3  246.77  4955.3  242.04  4955.6  241.54  4959.5  242.04
  4985.7  246.71  5037.0  247.00  5075.3  247.79  5080.9  249.18  5103.2  248.65
  5120.0  246.94  5125.6  248.02  5134.0  246.23  5178.7  247.42  5215.0  246.34
  5276.5  250.42  5304.5  253.96  5312.9  256.40  5350.4  258.55  5670.6  268.90
#Mann=10,-1,0
  4151.3    0.07       0  4593.2   0.035       0  4624.1    0.07       0
  4736.3   0.035       0  4759.6    0.12       0  4879.5   0.033       0
  4955.3   0.033       0  4959.5   0.033       0  5037.0     0.1       0
  5350.4   0.035       0
Bank Sta=4955.3,4959.5
Exp/Cntr=0.3,0.1

Type RM Length L Ch R = 1,8394,436,436,436
BEGIN DESCRIPTION:
Stream0836 10.0
END DESCRIPTION:
XS GIS Cut Line= 3
      2476575.02     13579224.98      2477175.00     13578475.00
      2477674.99     13577275.03
#Sta/Elev= 30
  4039.6  279.63  4231.7  270.45  4293.3  265.79  4323.7  264.71  4331.7  265.52
  4416.6  262.01  4663.4  252.47  4761.0  249.84  4844.0  248.54  4885.6  250.25
  4910.2  247.72  4928.8  245.89  4972.0  245.80  4992.8  243.70  5038.5  245.21
  5075.9  243.77  5084.1  242.08  5084.3  241.58  5088.3  242.08  5091.6  244.95
  5097.5  246.77  5139.2  247.78  5184.2  245.71  5239.8  249.57  5520.0  252.49
  5661.8  256.92  5696.0  258.32  5872.8  263.87  5942.0  265.56  6300.0  272.61
#Mann=13,-1,0
  4039.6    0.05       0  4293.3   0.035       0  4416.6    0.07       0
  4663.4    0.12       0  4761.0    0.07       0  4910.2    0.12       0
  5084.1    0.05       0  5088.3    0.12       0  5239.8    0.07       0
  5661.8   0.035       0  5696.0    0.07       0  5872.8   0.035       0
  5942.0    0.07       0
Bank Sta=5084.1,5088.3
Exp/Cntr=0.3,0.1

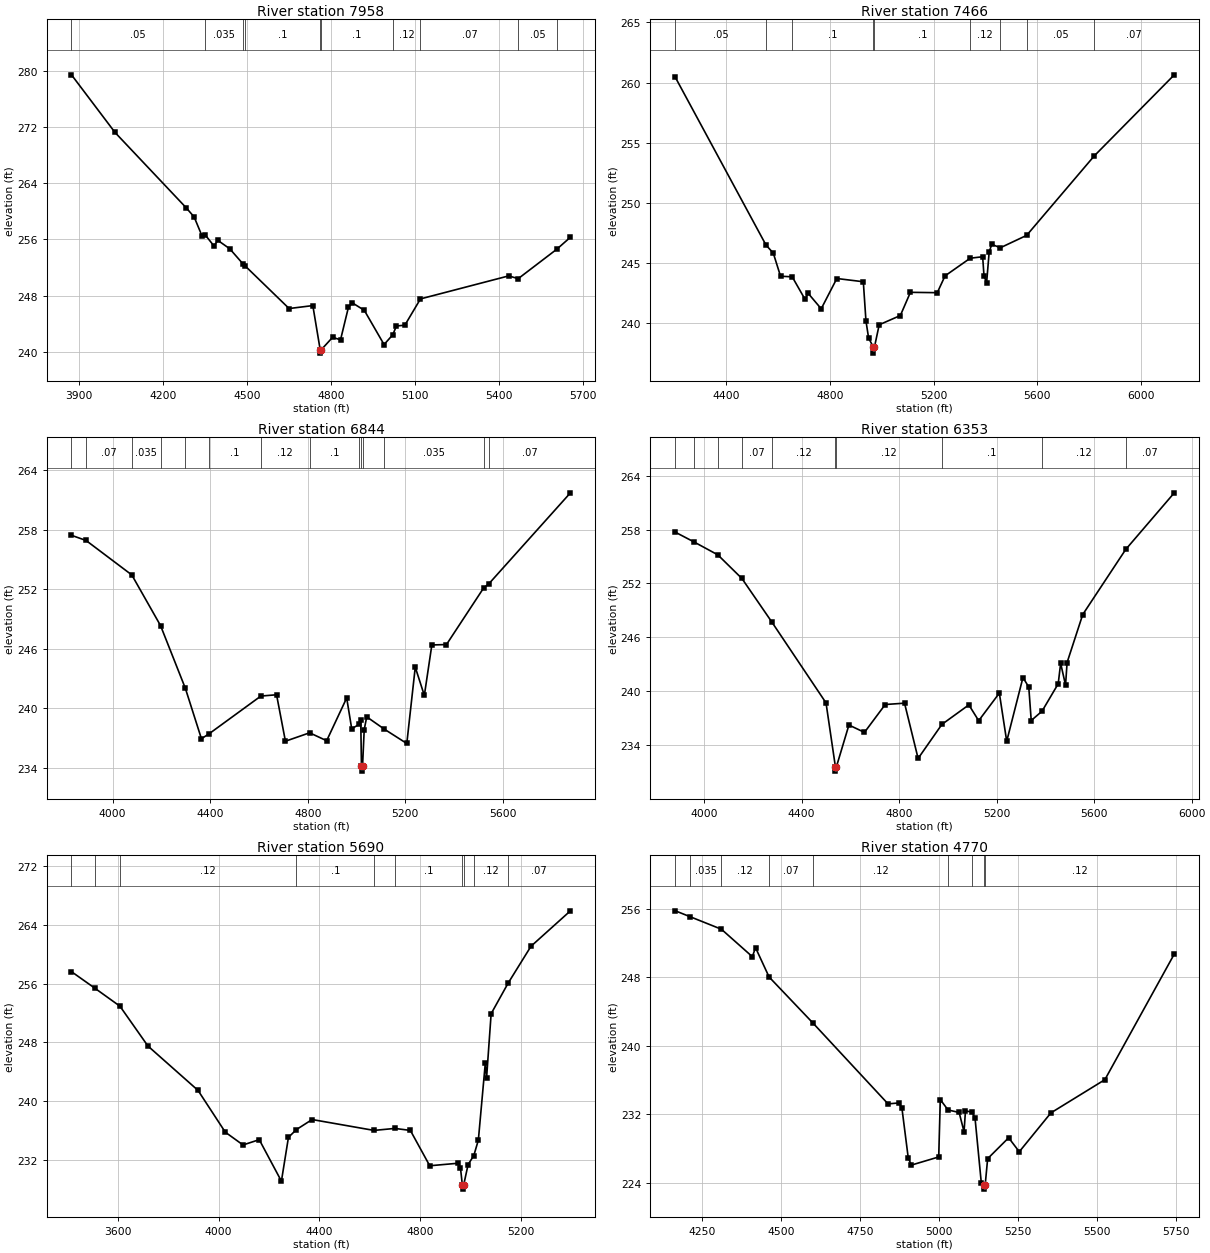
Type RM Length L Ch R = 1,7958,492,492,492
BEGIN DESCRIPTION:
Stream0836 9.0
END DESCRIPTION:
XS GIS Cut Line= 3
      2476775.03     13579374.97      2477575.00     13578575.00
      2477525.00     13577924.95
#Sta/Elev= 30
  3873.4  279.39  4028.9  271.20  4283.5  260.48  4311.8  259.18  4340.1  256.47
  4350.4  256.68  4382.5  255.06  4396.6  255.85  4439.0  254.66  4485.9  252.53
  4495.1  252.18  4651.2  246.16  4736.0  246.58  4762.2  240.32  4762.5  239.82
  4766.5  240.32  4806.7  242.07  4835.0  241.71  4863.3  246.35  4877.5  246.96
  4919.9  245.91  4990.6  241.04  5021.7  242.43  5034.8  243.68  5064.9  243.79
  5120.7  247.53  5436.0  250.80  5470.1  250.41  5608.5  254.61  5656.7  256.30
#Mann=10,-1,0
  3873.4    0.05       0  4350.4   0.035       0  4485.9    0.12       0
  4495.1     0.1       0  4762.2    0.05       0  4766.5     0.1       0
  5021.7    0.12       0  5120.7    0.07       0  5470.1    0.05       0
  5608.5    0.07       0
Bank Sta=4762.2,4766.5
Exp/Cntr=0.3,0.1

Type RM Length L Ch R = 1,7466,622,622,622
BEGIN DESCRIPTION:
Stream0836 8.0
END DESCRIPTION:
XS GIS Cut Line= 3
      2478111.44     13579504.99      2477915.78     13578544.49
      2477889.10     13577601.80
#Sta/Elev= 30
  4204.6  260.43  4553.9  246.48  4582.2  245.80  4610.1  243.88  4655.1  243.83
  4704.7  241.95  4716.4  242.46  4766.9  241.17  4827.1  243.69  4929.2  243.42
  4939.4  240.15  4949.6  238.74  4967.8  237.98  4968.1  237.48  4972.1  237.98
  4990.4  239.84  5072.0  240.61  5110.7  242.54  5214.3  242.51  5244.3  243.91
  5341.4  245.38  5389.2  245.50  5394.4  243.92  5404.4  243.32  5414.4  245.91
  5424.4  246.53  5457.5  246.25  5558.8  247.28  5819.3  253.89  6127.9  260.64
#Mann=9,-1,0
  4204.6    0.05       0  4553.9   0.035       0  4655.1     0.1       0
  4967.8    0.05       0  4972.1     0.1       0  5341.4    0.12       0
  5457.5    0.07       0  5558.8    0.05       0  5819.3    0.07       0
Bank Sta=4967.8,4972.1
Exp/Cntr=0.3,0.1

Type RM Length L Ch R = 1,6844,491,491,491
BEGIN DESCRIPTION:
XS7812
END DESCRIPTION:
XS GIS Cut Line= 2
      2478618.36     13579433.82      2478155.90     13577441.69
#Sta/Elev= 30
  3831.8  257.45  3891.4  256.93  4079.0  253.45  4196.9  248.33  4298.7  241.99
  4364.4  236.91  4396.9  237.43  4608.1  241.22  4672.4  241.35  4708.7  236.66
  4807.9  237.51  4877.7  236.71  4959.8  241.03  4980.4  237.92  5011.6  238.37
  5017.4  238.79  5020.4  234.14  5020.7  233.64  5024.8  234.14  5031.7  237.84
  5042.0  239.12  5113.4  237.89  5206.2  236.43  5240.9  244.14  5278.1  241.28
  5308.9  246.38  5368.8  246.42  5520.8  252.12  5543.1  252.57  5876.9  261.74
#Mann=14,-1,0
  3831.8    0.12       0  3891.4    0.07       0  4079.0   0.035       0
  4196.9    0.07       0  4298.7    0.12       0  4396.9     0.1       0
  4608.1    0.12       0  4807.9     0.1       0  5011.6    0.12       0
  5020.4    0.05       0  5024.8    0.12       0  5113.4   0.035       0
  5520.8    0.12       0  5543.1    0.07       0
Bank Sta=5020.4,5024.8
Exp/Cntr=0.3,0.1

Type RM Length L Ch R = 1,6353,663,663,663
BEGIN DESCRIPTION:
XS7811
END DESCRIPTION:
XS GIS Cut Line= 4
      2478956.31     13579362.69      2478929.63     13578713.46
      2478698.40     13578082.03      2478778.44     13577361.68
#Sta/Elev= 30
  3881.8  257.70  3957.4  256.63  4056.1  255.18  4154.9  252.55  4277.6  247.71
  4500.0  238.71  4538.4  231.62  4538.7  231.12  4542.8  231.62  4593.9  236.25
  4657.7  235.43  4742.9  238.53  4822.1  238.68  4877.8  232.53  4975.4  236.32
  5086.0  238.49  5126.3  236.73  5211.1  239.80  5241.3  234.44  5307.9  241.53
  5331.8  240.48  5341.9  236.75  5386.3  237.79  5452.6  240.84  5462.6  243.12
  5482.7  240.68  5489.0  243.20  5553.2  248.54  5729.5  255.78  5928.8  262.08
#Mann=10,-1,0
  3881.8    0.07       0  3957.4    0.05       0  4056.1   0.035       0
  4154.9    0.07       0  4277.6    0.12       0  4538.4    0.05       0
  4542.8    0.12       0  4975.4     0.1       0  5386.3    0.12       0
  5729.5    0.07       0
Bank Sta=4538.4,4542.8
Exp/Cntr=0.3,0.1

Type RM Length L Ch R = 1,5690,920,920,920
BEGIN DESCRIPTION:
XS7810
END DESCRIPTION:
XS GIS Cut Line= 3
      2479054.15     13579282.61      2479187.54     13578597.85
      2478974.10     13577334.99
#Sta/Elev= 30
  3417.0  257.62  3509.3  255.38  3609.2  252.92  3720.2  247.50  3918.6  241.47
  4026.9  235.78  4097.2  234.04  4161.5  234.76  4249.4  229.11  4277.3  235.08
  4309.2  236.14  4371.1  237.50  4616.6  236.02  4699.3  236.29  4760.7  236.02
  4837.6  231.21  4949.2  231.55  4959.3  230.95  4967.1  228.53  4967.5  228.03
  4971.7  228.53  4989.7  231.38  5012.2  232.59  5030.3  234.70  5057.8  245.15
  5062.9  243.15  5081.0  251.90  5148.2  256.05  5239.1  261.08  5395.4  265.90
#Mann=10,-1,0
  3417.0    0.05       0  3509.3   0.035       0  3609.2    0.12       0
  4309.2     0.1       0  4616.6    0.12       0  4699.3     0.1       0
  4967.1    0.05       0  4971.7     0.1       0  5012.2    0.12       0
  5148.2    0.07       0
Bank Sta=4967.1,4971.7
Exp/Cntr=0.3,0.1

Type RM Length L Ch R = 1,4770,521,521,521
BEGIN DESCRIPTION:
Stream0836 7.0
END DESCRIPTION:
XS GIS Cut Line= 3
      2479365.41     13579247.05      2479481.02     13578331.05
      2479525.00     13577674.99
#Sta/Elev= 30
  4164.6  255.79  4211.5  255.10  4310.5  253.64  4408.6  250.43  4418.6  251.49
  4461.6  248.06  4601.3  242.65  4838.5  233.23  4872.2  233.34  4882.3  232.79
  4902.5  226.92  4912.5  226.08  4999.0  227.03  5004.1  233.73  5028.6  232.52
  5063.7  232.23  5079.3  229.98  5083.8  232.42  5104.3  232.27  5114.0  231.61
  5134.0  223.99  5141.7  223.77  5142.0  223.27  5146.3  223.77  5154.1  226.83
  5220.6  229.27  5254.3  227.64  5354.5  232.18  5525.5  236.06  5745.4  250.74
#Mann=9,-1,0
  4164.6    0.05       0  4211.5   0.035       0  4310.5    0.12       0
  4461.6    0.07       0  4601.3    0.12       0  5028.6     0.1       0
  5104.3    0.12       0  5141.7    0.05       0  5146.3    0.12       0
Bank Sta=5141.7,5146.3
Exp/Cntr=0.3,0.1

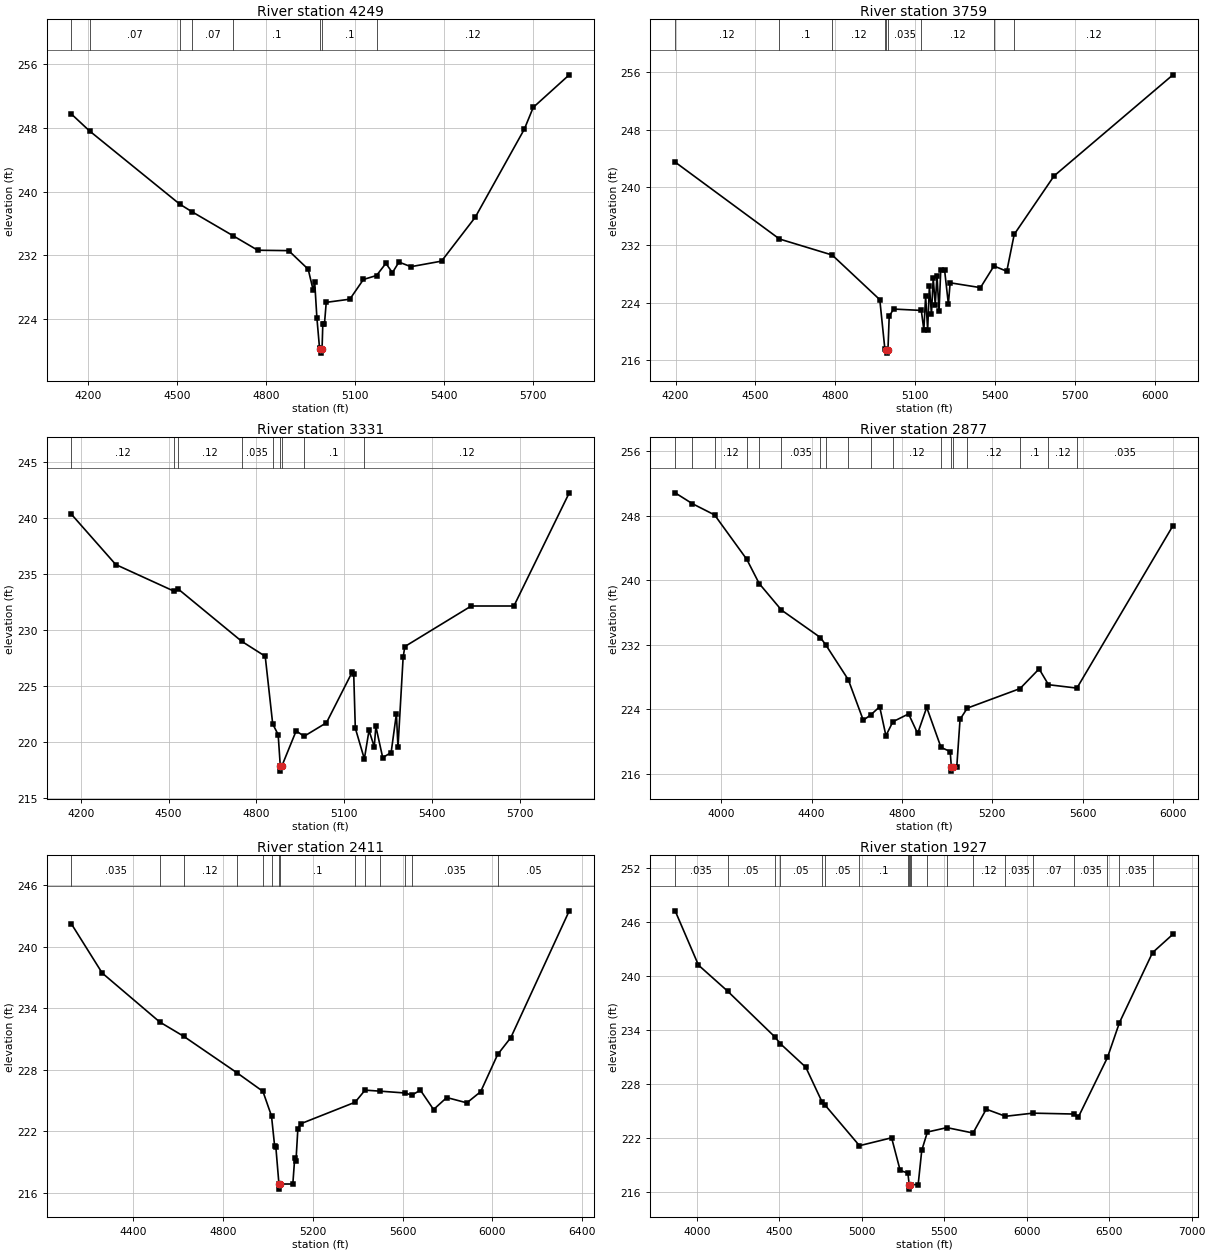
Type RM Length L Ch R = 1,4249,490,490,490
BEGIN DESCRIPTION:
Stream0836 6.0
END DESCRIPTION:
XS GIS Cut Line= 3
      2479525.00     13579075.00      2479925.00     13578325.00
      2479574.98     13577574.96
#Sta/Elev= 30
  4143.3  249.76  4204.2  247.64  4508.1  238.43  4548.4  237.49  4688.7  234.43
  4771.2  232.62  4875.4  232.57  4941.2  230.23  4957.5  227.67  4963.2  228.57
  4970.6  224.07  4979.5  220.26  4982.5  220.17  4982.9  219.67  4987.9  220.17
  4990.5  223.38  4996.1  223.38  5002.0  226.06  5081.6  226.46  5127.3  228.94
  5171.5  229.44  5203.0  230.97  5225.0  229.80  5247.1  231.13  5287.3  230.55
  5390.6  231.25  5504.1  236.77  5669.6  247.86  5699.6  250.60  5821.0  254.70
#Mann=8,-1,0
  4143.3    0.12       0  4204.2    0.07       0  4508.1    0.12       0
  4548.4    0.07       0  4688.7     0.1       0  4982.5    0.05       0
  4987.9     0.1       0  5171.5    0.12       0
Bank Sta=4982.5,4987.9
Exp/Cntr=0.3,0.1

Type RM Length L Ch R = 1,3759,428,428,428
BEGIN DESCRIPTION:
Stream0836 5.0
END DESCRIPTION:
XS GIS Cut Line= 3
      2480275.00     13579024.96      2480375.00     13578225.00
      2479575.00     13577525.00
#Sta/Elev= 30
  4198.4  243.49  4590.1  232.83  4788.0  230.61  4966.8  224.42  4985.9  217.55
  4991.5  217.51  4992.0  217.01  4997.5  217.51  5002.1  222.10  5018.3  223.12
  5122.7  222.93  5132.2  220.22  5138.9  224.90  5146.5  220.25  5153.1  226.35
  5160.7  222.40  5167.4  227.40  5175.0  223.71  5181.6  227.76  5189.2  222.85
  5195.8  228.60  5210.1  228.53  5224.3  223.82  5231.0  226.76  5344.8  226.09
  5395.4  229.09  5443.6  228.36  5471.5  233.47  5621.0  241.57  6067.6  255.59
#Mann=9,-1,0
  4198.4    0.12       0  4590.1     0.1       0  4788.0    0.12       0
  4985.9   0.035       0  4991.5   0.035       0  4997.5   0.035       0
  5122.7    0.12       0  5395.4     0.1       0  5471.5    0.12       0
Bank Sta=4991.5,4997.5
Exp/Cntr=0.3,0.1

Type RM Length L Ch R = 1,3331,454,454,454
BEGIN DESCRIPTION:
Stream0836 4.0
END DESCRIPTION:
XS GIS Cut Line= 3
      2480425.00     13578975.01      2480775.00     13578225.00
      2480424.99     13577424.97
#Sta/Elev= 30
  4168.1  240.36  4319.5  235.86  4519.1  233.47  4533.8  233.65  4749.8  228.99
  4830.2  227.65  4855.8  221.59  4874.4  220.64  4881.6  217.87  4882.1  217.37
  4887.7  217.87  4935.9  220.97  4963.1  220.49  5039.4  221.70  5126.7  226.20
  5132.6  226.06  5138.0  221.22  5168.9  218.46  5184.8  221.01  5202.8  219.55
  5208.2  221.37  5231.6  218.58  5260.4  219.03  5278.4  222.50  5283.8  219.49
  5301.4  227.55  5307.2  228.52  5534.1  232.15  5679.9  232.15  5869.0  242.28
#Mann=9,-1,0
  4168.1    0.12       0  4519.1     0.1       0  4533.8    0.12       0
  4749.8   0.035       0  4855.8    0.12       0  4881.6    0.05       0
  4887.7    0.12       0  4963.1     0.1       0  5168.9    0.12       0
Bank Sta=4881.6,4887.7
Exp/Cntr=0.3,0.1

Type RM Length L Ch R = 1,2877,466,466,466
BEGIN DESCRIPTION:
Stream0836 3.0
END DESCRIPTION:
XS GIS Cut Line= 3
      2481025.00     13579224.98      2481125.00     13578025.00
      2480525.02     13577225.03
#Sta/Elev= 30
  3795.7  250.83  3871.7  249.49  3970.4  248.09  4113.0  242.58  4167.7  239.59
  4266.4  236.30  4438.7  232.90  4463.7  231.94  4562.3  227.67  4628.6  222.65
  4661.0  223.29  4701.3  224.32  4728.9  220.73  4759.6  222.46  4829.2  223.43
  4869.4  221.01  4909.5  224.24  4972.8  219.28  5013.4  218.77  5018.7  216.84
  5019.2  216.34  5024.8  216.84  5042.5  216.84  5057.1  222.76  5089.3  224.15
  5322.7  226.57  5407.1  229.01  5448.6  227.05  5574.5  226.63  5999.8  246.76
#Mann=18,-1,0
  3795.7    0.12       0  3871.7   0.035       0  3970.4    0.12       0
  4113.0   0.035       0  4167.7    0.12       0  4266.4   0.035       0
  4438.7    0.12       0  4463.7     0.1       0  4562.3    0.12       0
  4661.0    0.05       0  4759.6    0.12       0  4972.8     0.1       0
  5018.7    0.05       0  5024.8     0.1       0  5089.3    0.12       0
  5322.7     0.1       0  5448.6    0.12       0  5574.5   0.035       0
Bank Sta=5018.7,5024.8
Exp/Cntr=0.3,0.1

Type RM Length L Ch R = 1,2411,484,484,484
BEGIN DESCRIPTION:
Stream0836 2.0
END DESCRIPTION:
XS GIS Cut Line= 3
      2481125.01     13578924.99      2481475.00     13578125.00
      2480875.02     13576925.04
#Sta/Elev= 30
  4126.7  242.22  4263.5  237.43  4519.6  232.65  4625.8  231.26  4862.2  227.71
  4978.6  225.88  5016.8  223.48  5030.6  220.57  5036.2  220.43  5049.9  216.84
  5050.4  216.34  5056.2  216.84  5111.7  216.84  5120.1  219.38  5125.7  219.11
  5134.1  222.24  5148.0  222.73  5388.7  224.82  5433.0  226.00  5500.5  225.90
  5612.3  225.72  5641.1  225.51  5679.1  226.00  5737.8  224.11  5796.5  225.28
  5885.9  224.76  5947.4  225.85  6022.9  229.48  6081.6  231.13  6341.5  243.50
#Mann=14,-1,0
  4126.7   0.035       0  4519.6    0.05       0  4625.8    0.12       0
  4862.2     0.1       0  4978.6    0.12       0  5016.8     0.1       0
  5049.9    0.05       0  5056.2     0.1       0  5388.7   0.035       0
  5433.0    0.12       0  5500.5   0.035       0  5612.3    0.12       0
  5641.1   0.035       0  6022.9    0.05       0
Bank Sta=5049.9,5056.2
Exp/Cntr=0.3,0.1

Type RM Length L Ch R = 1,1927,359,359,359
BEGIN DESCRIPTION:
Stream0836 1.0
END DESCRIPTION:
XS GIS Cut Line= 3
      2481125.03     13579024.97      2481925.00     13578225.00
      2480925.01     13576625.02
#Sta/Elev= 30
  3868.7  247.29  4010.1  241.25  4186.1  238.37  4472.5  233.28  4507.3  232.50
  4660.6  229.90  4758.8  226.06  4778.3  225.67  4986.2  221.17  5181.0  222.05
  5232.9  218.42  5279.7  218.12  5287.6  216.84  5288.1  216.34  5293.9  216.84
  5299.1  216.84  5342.0  216.84  5363.8  220.65  5398.0  222.69  5516.3  223.18
  5674.7  222.58  5754.7  225.23  5871.3  224.44  6037.7  224.79  6288.5  224.69
  6313.1  224.35  6489.7  230.98  6562.6  234.87  6762.9  242.64  6886.8  244.69
#Mann=20,-1,0
  3868.7   0.035       0  4186.1    0.05       0  4472.5   0.035       0
  4507.3    0.05       0  4758.8   0.035       0  4778.3    0.05       0
  4986.2     0.1       0  5279.7   0.033       0  5287.6    0.05       0
  5293.9   0.033       0  5299.1     0.1       0  5398.0   0.035       0
  5516.3    0.05       0  5674.7    0.12       0  5871.3   0.035       0
  6037.7    0.07       0  6288.5   0.035       0  6489.7    0.05       0
  6562.6   0.035       0  6762.9    0.05       0
Bank Sta=5287.6,5293.9
Exp/Cntr=0.3,0.1

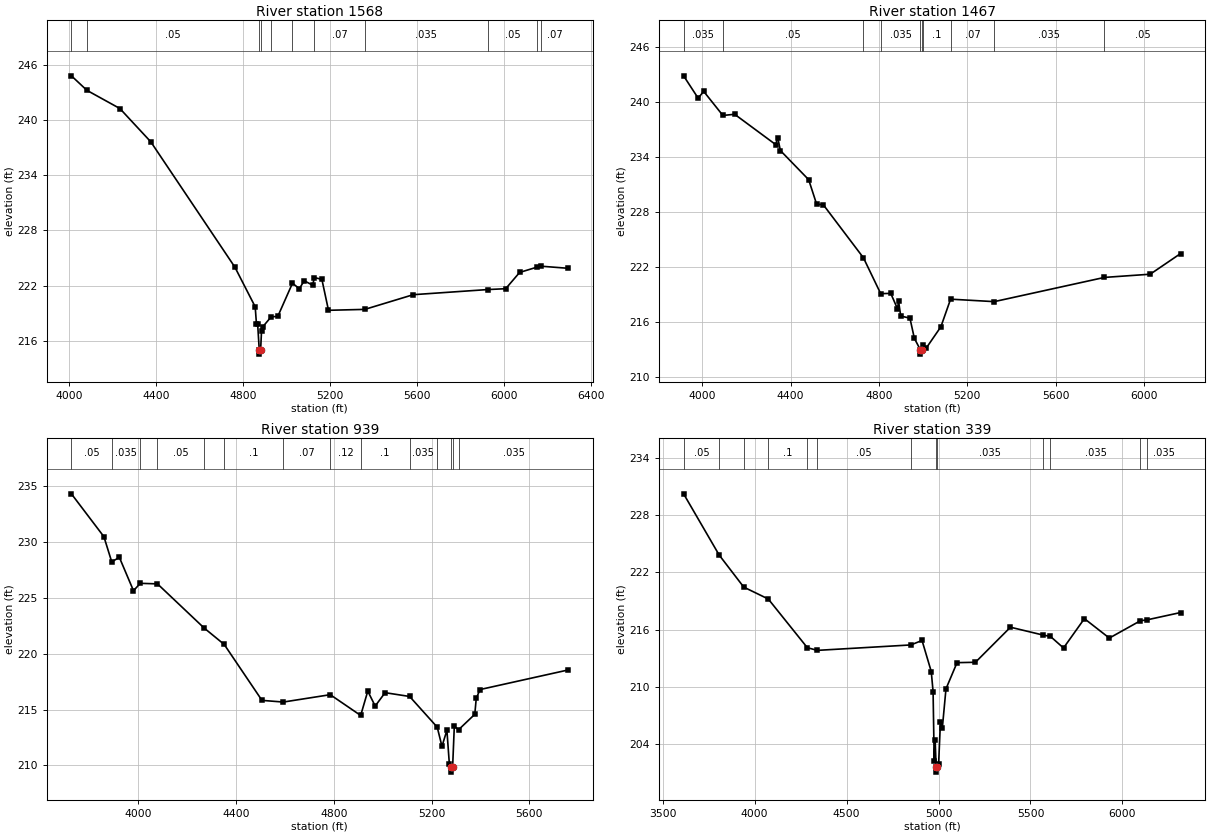
Type RM Length L Ch R = 1,1568,101,101,101
BEGIN DESCRIPTION:
XS7815a
END DESCRIPTION:
XS GIS Cut Line= 4
      2481878.47     13579239.59      2482232.64     13578430.58
      2482288.19     13578093.77      2481583.91     13577299.29
#Sta/Elev= 30
  4009.9  244.83  4081.4  243.25  4233.0  241.27  4375.1  237.65  4762.2  224.00
  4855.5  219.69  4861.2  217.84  4866.7  217.85  4874.0  215.04  4874.5  214.54
  4880.5  215.04  4884.6  217.05  4889.8  217.50  4928.9  218.60  4959.5  218.65
  5027.0  222.26  5058.5  221.66  5081.1  222.53  5119.6  222.04  5127.8  222.87
  5162.2  222.68  5192.6  219.31  5359.7  219.41  5582.6  221.01  5926.6  221.57
  6007.8  221.66  6071.9  223.43  6150.6  224.00  6170.3  224.11  6296.1  223.88
#Mann=11,-1,0
  4009.9   0.035       0  4081.4    0.05       0  4874.0   0.035       0
  4880.5    0.05       0  4928.9   0.035       0  5027.0     0.1       0
  5127.8    0.07       0  5359.7   0.035       0  5926.6    0.05       0
  6150.6    0.12       0  6170.3    0.07       0
Bank Sta=4874,4880.5
Exp/Cntr=0.3,0.1

Type RM Length L Ch R = 1,1467,528,528,528
BEGIN DESCRIPTION:
XS7815
END DESCRIPTION:
XS GIS Cut Line= 4
      2481997.88     13579344.86      2482353.61     13578402.19
      2482335.82     13577957.52      2481776.35     13577389.17
#Sta/Elev= 30
  3915.2  242.86  3981.2  240.42  4006.0  241.17  4093.1  238.54  4146.3  238.67
  4331.9  235.37  4341.6  236.12  4353.3  234.72  4481.5  231.54  4517.5  228.87
  4547.7  228.81  4729.4  223.03  4807.6  219.12  4853.1  219.15  4883.3  217.49
  4888.6  218.27  4898.4  216.68  4940.0  216.45  4960.0  214.25  4986.7  213.03
  4987.2  212.53  4993.2  213.03  4999.6  213.57  5014.0  213.20  5080.1  215.51
  5124.0  218.52  5321.5  218.25  5820.5  220.89  6027.8  221.24  6165.3  223.49
#Mann=10,-1,0
  3915.2   0.035       0  4093.1    0.05       0  4729.4    0.07       0
  4807.6   0.035       0  4986.7    0.05       0  4993.2   0.035       0
  4999.6     0.1       0  5124.0    0.07       0  5321.5   0.035       0
  5820.5    0.05       0
Bank Sta=4986.7,4993.2
Exp/Cntr=0.3,0.1

Type RM Length L Ch R = 1,939,600,600,600
BEGIN DESCRIPTION:
XS7814
END DESCRIPTION:
XS GIS Cut Line= 4
      2482371.41     13579424.92      2482922.79     13578615.64
      2482824.96     13577975.31      2482479.04     13577762.43
#Sta/Elev= 30
  3726.7  234.33  3859.7  230.49  3891.8  228.23  3922.9  228.64  3980.7  225.65
  4008.8  226.31  4078.9  226.26  4269.5  222.31  4352.0  220.83  4506.4  215.82
  4593.7  215.67  4785.8  216.33  4910.2  214.47  4939.3  216.65  4969.6  215.31
  5010.1  216.51  5110.5  216.17  5223.4  213.42  5242.8  211.70  5263.0  213.14
  5273.1  210.10  5280.0  209.89  5280.5  209.39  5286.5  209.89  5293.3  213.49
  5310.7  213.19  5377.1  214.57  5383.0  215.99  5398.4  216.79  5759.9  218.55
#Mann=14,-1,0
  3726.7    0.05       0  3891.8   0.035       0  4008.8    0.07       0
  4078.9    0.05       0  4269.5    0.07       0  4352.0     0.1       0
  4593.7    0.07       0  4785.8    0.12       0  4910.2     0.1       0
  5110.5   0.035       0  5223.4    0.07       0  5280.0    0.05       0
  5286.5    0.07       0  5310.7   0.035       0
Bank Sta=5280,5286.5
Exp/Cntr=0.3,0.1

Type RM Length L Ch R = 1,339,0,0,0
BEGIN DESCRIPTION:
XS7813
END DESCRIPTION:
XS GIS Cut Line= 4
      2482549.29     13579433.80      2483358.57     13578597.85
      2483394.14     13577975.31      2482511.51     13577732.42
#Sta/Elev= 30
  3613.6  230.25  3807.2  223.82  3940.7  220.46  4074.1  219.21  4286.5  214.10
  4341.1  213.82  4849.4  214.39  4910.2  214.86  4960.3  211.60  4970.3  209.50
  4976.4  202.16  4981.4  204.43  4987.0  201.54  4987.5  201.04  4993.6  201.54
  5000.3  201.88  5010.3  206.34  5020.4  205.64  5040.4  209.78  5100.5  212.53
  5200.6  212.57  5391.0  216.25  5567.5  215.43  5608.6  215.28  5679.6  214.07
  5793.1  217.15  5928.7  215.11  6097.8  216.93  6133.2  217.02  6316.1  217.79
#Mann=13,-1,0
  3613.6    0.05       0  3807.2   0.035       0  3940.7    0.12       0
  4074.1     0.1       0  4286.5    0.12       0  4341.1    0.05       0
  4849.4   0.035       0  4987.0   0.035       0  4993.6   0.035       0
  5567.5    0.12       0  5608.6   0.035       0  6097.8    0.07       0
  6133.2   0.035       0
Bank Sta=4987,4993.6
Exp/Cntr=0.3,0.1

Chan Stop Cuts=-1