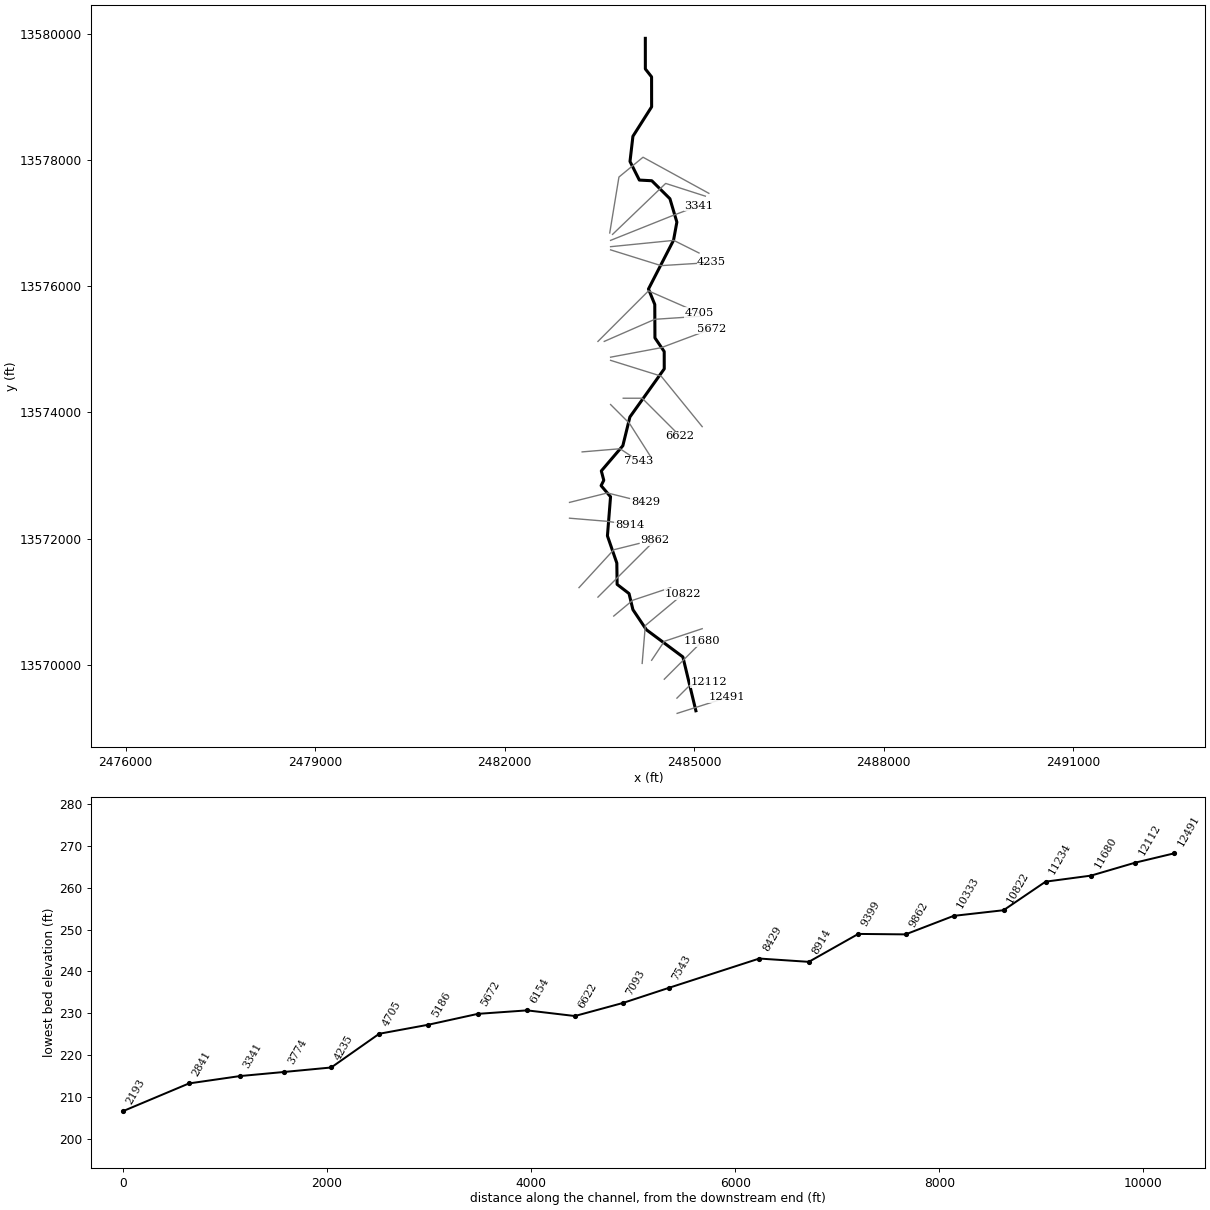
--- Stream0837.prj (project) ---

Proj Title=Stream0837 Base Level Engineering
Current Plan=p01
Default Exp/Contr=0.3,0.1
English Units
Geom File=g01
Flow File=f01
Plan File=p01
BEGIN DESCRIPTION:
Stream0837
END DESCRIPTION:

--- Stream0837.p01 (plan) ---

Plan Title=Multiple Run
Short Identifier=Multiple
Geom File=g01
Flow File=f01
Subcritical Flow
K Sum by GR= 0
Std Step Tol= 0.01
Critical Tol= 0.01
Num of Std Step Trials= 20
Max Error Tol= 0.3
Flow Tol Ratio= 0.001
Split Flow NTrial= 30
Split Flow Tol= 0.02
Split Flow Ratio= 0.02
Log Output Level= 0
Friction Slope Method= 1
Unsteady Friction Slope Method= 2
Unsteady Bridges Friction Slope Method= 1
Parabolic Critical Depth
Global Vel Dist=  1 , 1 , 1
Global Log Level= 0
CheckData=True
Encroach Param= -1, 0, 0, 0
BEGIN DESCRIPTION:
Multiple Run
END DESCRIPTION:

--- Stream0837.f01 (steady flow) ---

Flow Title=Multiple
Number of Profiles=7
Profile Names=10-year,25-year,50-year,1pct_min,100-year,1pct_plu,500-year
River Rch & RM= Stream0837,Reach-1,12491
     324     502     657     418     834    1663    1327
River Rch & RM= Stream0837,Reach-1,10822
     690    1119    1510     987    1968    3927    3314
River Rch & RM= Stream0837,Reach-1,6154
     984    1620    2205    1451    2896    5778    4948
Boundary for River Rch & Prof#=Stream0837,Reach-1,1
Up Type=0
Dn Type=3
Dn Slope=0.005
Boundary for River Rch & Prof#=Stream0837,Reach-1,2
Up Type=0
Dn Type=3
Dn Slope=0.005
Boundary for River Rch & Prof#=Stream0837,Reach-1,3
Up Type=0
Dn Type=3
Dn Slope=0.005
Boundary for River Rch & Prof#=Stream0837,Reach-1,4
Up Type=0
Dn Type=3
Dn Slope=0.005
Boundary for River Rch & Prof#=Stream0837,Reach-1,5
Up Type=0
Dn Type=3
Dn Slope=0.005
Boundary for River Rch & Prof#=Stream0837,Reach-1,6
Up Type=0
Dn Type=3
Dn Slope=0.005
Boundary for River Rch & Prof#=Stream0837,Reach-1,7
Up Type=0
Dn Type=3
Dn Slope=0.005

--- Stream0837.g01 (geometry) ---

Geom Title=Existing Conditions

River Reach=Stream0837,Reach-1
Reach XY= 30
      2485025.00     13569275.00      2484819.48     13570127.43
      2484241.61     13570558.31      2484028.54     13570876.47
      2483966.98     13571131.34      2483778.53     13571276.45
      2483773.78     13571614.50      2483625.07     13572045.03
      2483674.40     13572664.38      2483525.01     13572840.36
      2483567.40     13572924.99      2483528.46     13573073.50
      2483869.16     13573472.71      2483980.48     13573927.44
      2484524.49     13574690.21      2484523.80     13574964.50
      2484377.06     13575180.86      2484374.49     13575709.79
      2484274.90     13575954.90      2484671.25     13576726.55
      2484724.23     13577014.31      2484614.24     13577384.68
      2484327.45     13577669.54      2484130.41     13577680.17
      2483982.33     13577974.90      2484028.55     13578373.53
      2484324.61     13578840.16      2484323.94     13579314.56
      2484225.39     13579440.16      2484225.00     13579925.00

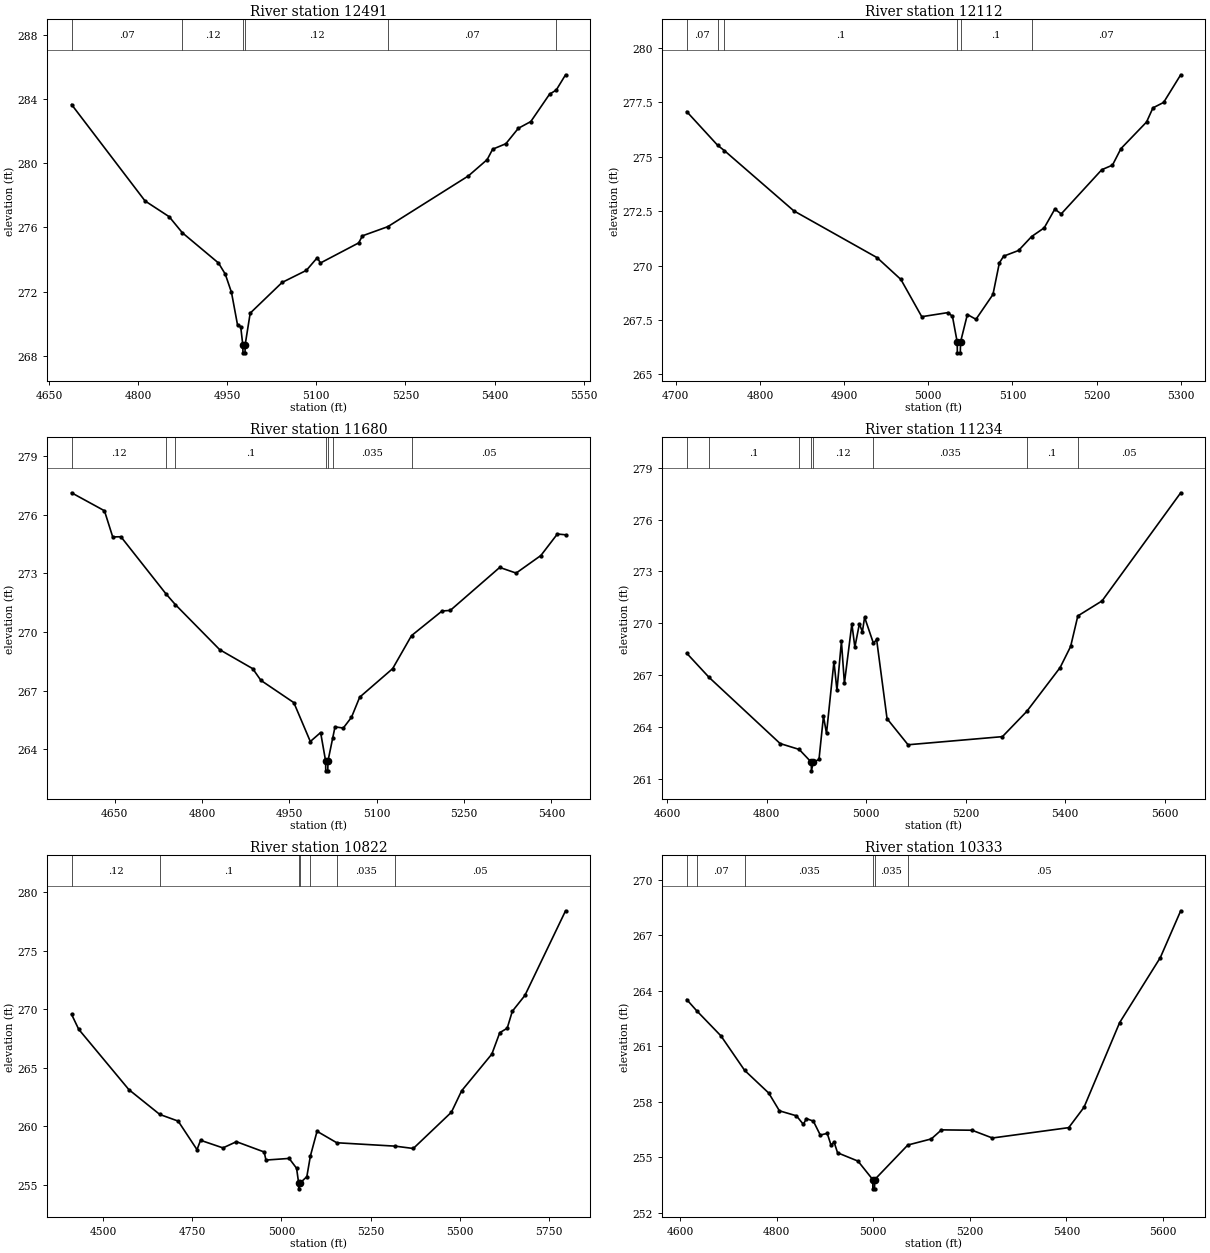
Type RM Length L Ch R = 1,12491,379,379,379
BEGIN DESCRIPTION:
XS7816
END DESCRIPTION:
XS GIS Cut Line= 2
      2484728.48     13569233.65      2485520.76     13569486.00
#Sta/Elev= 30
  4688.1  283.65  4811.8  277.65  4852.4  276.67  4874.6  275.67  4935.4  273.79
  4946.8  273.10  4957.3  271.96  4967.6  269.91  4972.8  269.83  4976.3  268.70
  4976.6  268.20  4980.1  268.20  4980.3  268.70  4988.8  270.67  5042.5  272.58
  5083.3  273.33  5101.7  274.12  5107.0  273.79  5171.4  275.04  5177.7  275.48
  5220.4  276.05  5356.1  279.21  5387.6  280.22  5396.9  280.87  5419.1  281.21
  5440.1  282.17  5461.1  282.59  5492.6  284.29  5503.9  284.55  5519.6  285.50
#Mann=6,-1,0
  4688.1    0.07       0  4874.6    0.12       0  4976.3    0.05       0
  4980.3    0.12       0  5220.4    0.07       0  5503.9    0.12       0
Bank Sta=4976.3,4980.3
Exp/Cntr=0.3,0.1

Type RM Length L Ch R = 1,12112,432,432,432
BEGIN DESCRIPTION:
Stream0837 20.0
END DESCRIPTION:
XS GIS Cut Line= 3
      2484725.01     13569475.01      2484925.00     13569675.00
      2485225.04     13569725.01
#Sta/Elev= 30
  4712.9  277.07  4749.7  275.52  4757.6  275.28  4840.2  272.51  4939.2  270.36
  4967.4  269.36  4992.2  267.65  5023.6  267.84  5028.7  267.66  5034.3  266.49
  5034.5  265.99  5038.0  265.99  5038.3  266.49  5046.4  267.75  5056.6  267.53
  5076.8  268.67  5084.4  270.12  5089.5  270.43  5107.2  270.69  5122.7  271.33
  5137.7  271.73  5150.3  272.59  5157.9  272.37  5206.1  274.40  5218.8  274.61
  5228.9  275.37  5259.3  276.59  5266.9  277.24  5279.6  277.49  5299.9  278.76
#Mann=6,-1,0
  4712.9    0.07       0  4749.7    0.12       0  4757.6     0.1       0
  5034.3    0.05       0  5038.3     0.1       0  5122.7    0.07       0
Bank Sta=5034.3,5038.3
Exp/Cntr=0.3,0.1

Type RM Length L Ch R = 1,11680,446,446,446
BEGIN DESCRIPTION:
Stream0837 19.0
END DESCRIPTION:
XS GIS Cut Line= 3
      2484525.02     13569775.02      2484825.00     13570075.00
      2485125.00     13570375.00
#Sta/Elev= 30
  4575.7  277.13  4632.2  276.21  4646.4  274.87  4660.5  274.88  4737.8  271.96
  4753.9  271.41  4830.2  269.10  4886.8  268.13  4900.9  267.53  4957.5  266.39
  4985.8  264.40  5003.5  264.86  5012.1  263.40  5012.3  262.90  5015.8  262.90
  5016.1  263.40  5024.4  264.60  5028.2  265.15  5042.4  265.09  5056.5  265.64
  5070.6  266.67  5127.2  268.13  5159.6  269.82  5212.1  271.08  5226.2  271.11
  5311.1  273.31  5339.3  273.02  5381.8  273.92  5410.1  275.02  5424.2  274.98
#Mann=7,-1,0
  4575.7    0.12       0  4737.8   0.035       0  4753.9     0.1       0
  5012.1    0.05       0  5016.1     0.1       0  5024.4   0.035       0
  5159.6    0.05       0
Bank Sta=5012.1,5016.1
Exp/Cntr=0.3,0.1

Type RM Length L Ch R = 1,11234,412,412,412
BEGIN DESCRIPTION:
Stream0837 18.0
END DESCRIPTION:
XS GIS Cut Line= 3
      2484324.99     13570074.99      2484525.00     13570375.00
      2485124.97     13570574.99
#Sta/Elev= 30
  4639.4  268.26  4684.4  266.86  4827.2  263.03  4865.5  262.69  4889.8  261.95
  4890.1  261.45  4893.8  261.95  4905.3  262.11  4914.3  264.61  4920.4  263.62
  4935.4  267.78  4941.4  266.11  4950.4  268.94  4956.4  266.52  4971.4  269.96
  4977.4  268.61  4986.5  269.96  4992.5  269.50  4997.0  270.34  5014.8  268.83
  5021.1  269.06  5042.1  264.47  5084.3  262.96  5274.0  263.43  5322.9  264.89
  5390.0  267.43  5411.1  268.65  5425.6  270.42  5474.3  271.29  5632.4  277.55
#Mann=8,-1,0
  4639.4    0.12       0  4684.4     0.1       0  4865.5    0.12       0
  4889.8    0.05       0  4893.8    0.12       0  5014.8   0.035       0
  5322.9     0.1       0  5425.6    0.05       0
Bank Sta=4889.8,4893.8
Exp/Cntr=0.3,0.1

Type RM Length L Ch R = 1,10822,489,489,489
BEGIN DESCRIPTION:
Stream0837 17.0
END DESCRIPTION:
XS GIS Cut Line= 3
      2484175.00     13570025.04      2484225.00     13570625.00
      2484825.03     13571125.02
#Sta/Elev= 30
  4412.3  269.55  4432.3  268.27  4572.8  263.11  4659.3  260.99  4710.8  260.42
  4763.5  257.98  4773.5  258.78  4836.2  258.13  4873.9  258.66  4951.6  257.78
  4956.6  257.09  5021.5  257.23  5042.3  256.39  5048.1  255.13  5048.4  254.63
  5052.1  255.13  5071.0  255.67  5081.0  257.44  5099.6  259.55  5154.8  258.57
  5318.2  258.28  5369.1  258.08  5475.8  261.18  5504.4  263.01  5589.0  266.15
  5611.2  267.98  5632.0  268.36  5646.3  269.81  5681.5  271.16  5795.4  278.40
#Mann=7,-1,0
  4412.3    0.12       0  4659.3     0.1       0  5048.1    0.05       0
  5052.1     0.1       0  5081.0    0.07       0  5154.8   0.035       0
  5318.2    0.05       0
Bank Sta=5048.1,5052.1
Exp/Cntr=0.3,0.1

Type RM Length L Ch R = 1,10333,471,471,471
BEGIN DESCRIPTION:
Stream0837 16.0
END DESCRIPTION:
XS GIS Cut Line= 3
      2483724.98     13570774.98      2484025.00     13571025.00
      2484625.00     13571225.00
#Sta/Elev= 30
  4613.8  263.52  4634.2  262.92  4684.8  261.55  4733.7  259.69  4783.7  258.46
  4805.8  257.50  4841.0  257.23  4855.3  256.77  4861.8  257.08  4876.1  256.94
  4890.4  256.19  4904.8  256.28  4912.6  255.65  4919.1  255.80  4926.2  255.23
  4968.5  254.78  4999.1  253.78  4999.3  253.28  5002.8  253.28  5003.1  253.78
  5071.7  255.65  5120.3  255.98  5141.4  256.47  5204.6  256.45  5246.8  256.03
  5404.9  256.59  5436.5  257.69  5510.3  262.27  5594.6  265.79  5636.8  268.32
#Mann=6,-1,0
  4613.8   0.035       0  4634.2    0.07       0  4733.7   0.035       0
  4999.1   0.035       0  5003.1   0.035       0  5071.7    0.05       0
Bank Sta=4999.1,5003.1
Exp/Cntr=0.3,0.1

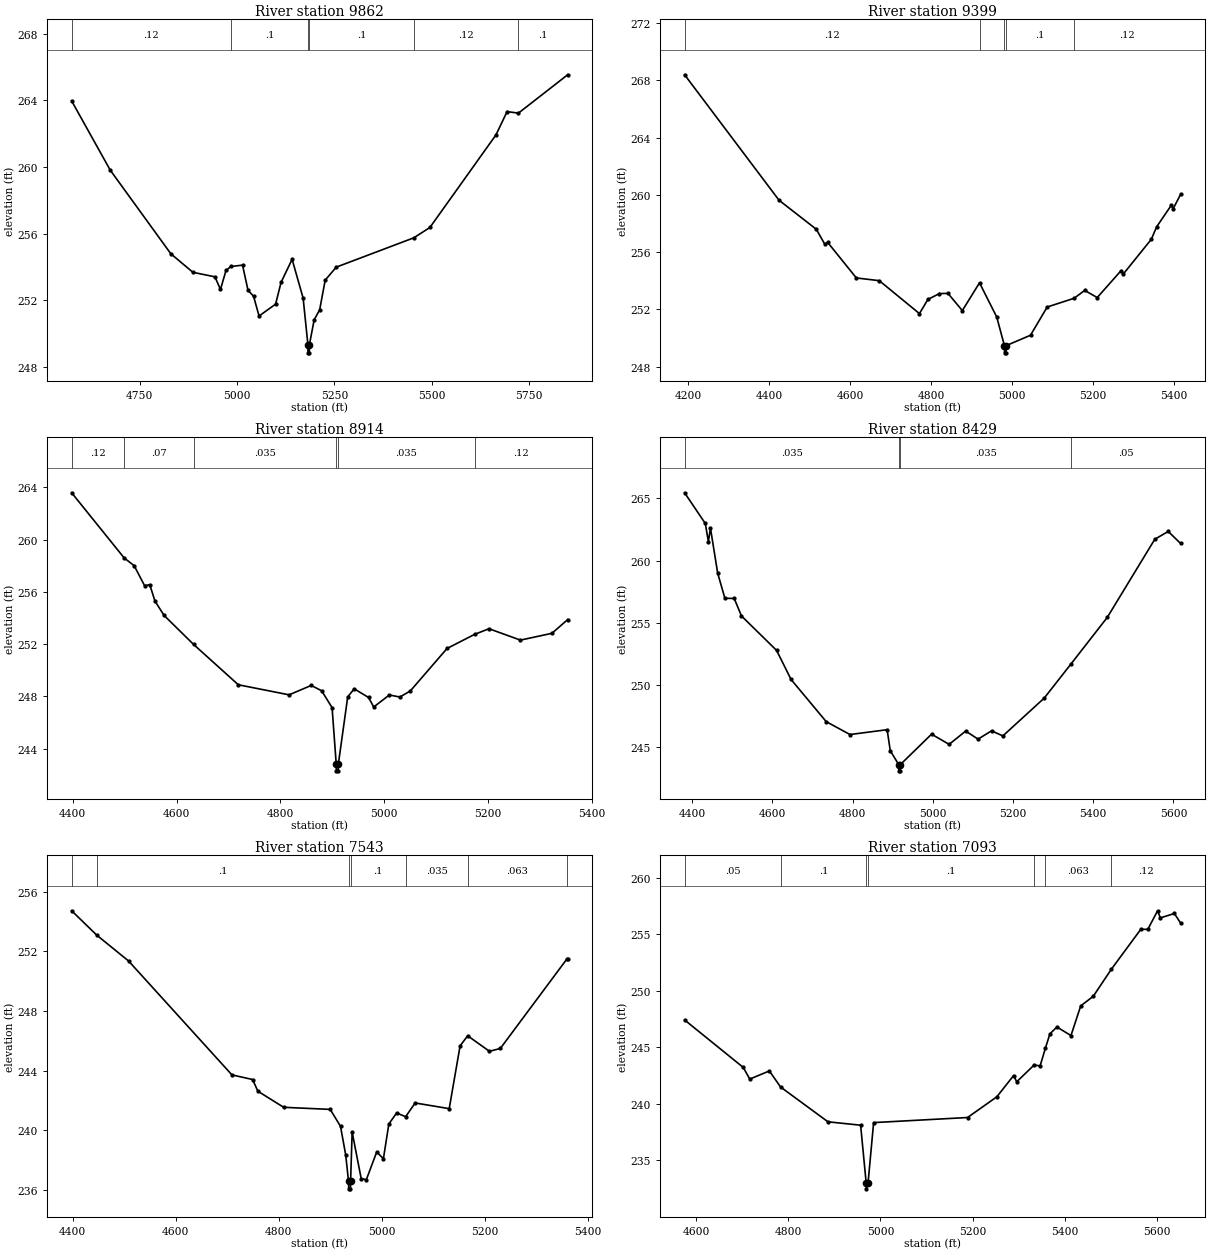
Type RM Length L Ch R = 1,9862,463,463,463
BEGIN DESCRIPTION:
Stream0837 15.0
END DESCRIPTION:
XS GIS Cut Line= 3
      2483474.97     13571074.97      2483775.00     13571375.00
      2484374.97     13571974.97
#Sta/Elev= 30
  4575.8  263.97  4674.8  259.82  4830.4  254.80  4887.0  253.69  4943.5  253.42
  4957.7  252.66  4971.8  253.80  4984.3  254.04  5014.3  254.12  5028.4  252.61
  5042.5  252.26  5056.7  251.07  5099.1  251.78  5113.2  253.09  5141.5  254.47
  5169.8  252.14  5182.0  249.36  5182.2  248.86  5185.7  248.86  5186.0  249.36
  5198.1  250.84  5212.2  251.44  5226.4  253.22  5254.7  254.00  5453.8  255.76
  5495.1  256.38  5664.8  261.94  5693.1  263.33  5722.3  263.24  5848.6  265.54
#Mann=6,-1,0
  4575.8    0.12       0  4984.3     0.1       0  5182.0    0.05       0
  5186.0     0.1       0  5453.8    0.12       0  5722.3     0.1       0
Bank Sta=5182,5186
Exp/Cntr=0.3,0.1

Type RM Length L Ch R = 1,9399,485,485,485
BEGIN DESCRIPTION:
Stream0837 14.0
END DESCRIPTION:
XS GIS Cut Line= 3
      2483174.99     13571224.99      2483725.00     13571825.00
      2484125.04     13571925.01
#Sta/Elev= 30
  4190.7  268.39  4424.1  259.63  4516.3  257.60  4537.6  256.54  4544.3  256.69
  4615.3  254.20  4672.0  254.01  4771.3  251.71  4792.2  252.70  4820.6  253.11
  4841.9  253.12  4877.3  251.92  4919.8  253.86  4962.4  251.47  4981.4  249.47
  4981.6  248.97  4985.1  248.97  4985.4  249.47  5045.9  250.20  5087.1  252.17
  5153.6  252.78  5179.9  253.33  5210.8  252.83  5270.1  254.72  5275.2  254.47
  5344.8  256.91  5357.7  257.77  5393.8  259.27  5398.9  259.05  5417.0  260.04
#Mann=5,-1,0
  4190.7    0.12       0  4919.8     0.1       0  4981.4    0.05       0
  4985.4     0.1       0  5153.6    0.12       0
Bank Sta=4981.4,4985.4
Exp/Cntr=0.3,0.1

Type RM Length L Ch R = 1,8914,485,485,485
BEGIN DESCRIPTION:
Stream0837 13.0
END DESCRIPTION:
XS GIS Cut Line= 3
      2483024.98     13572325.00      2483625.00     13572275.00
      2483975.04     13572224.99
#Sta/Elev= 30
  4397.9  263.59  4499.1  258.60  4518.3  258.01  4538.4  256.48  4548.4  256.55
  4558.5  255.29  4576.0  254.20  4632.8  251.98  4719.0  248.89  4816.9  248.12
  4859.5  248.84  4879.6  248.43  4899.7  247.14  4907.7  242.80  4907.9  242.30
  4911.4  242.30  4911.7  242.80  4929.8  247.96  4942.3  248.58  4969.9  247.92
  4979.9  247.19  5010.1  248.11  5030.3  247.95  5050.5  248.42  5121.2  251.67
  5174.3  252.75  5202.0  253.18  5262.6  252.31  5323.3  252.83  5353.6  253.88
#Mann=6,-1,0
  4397.9    0.12       0  4499.1    0.07       0  4632.8   0.035       0
  4907.7   0.035       0  4911.7   0.035       0  5174.3    0.12       0
Bank Sta=4907.7,4911.7
Exp/Cntr=0.3,0.1

Type RM Length L Ch R = 1,8429,886,886,886
BEGIN DESCRIPTION:
Stream0837 12.0
END DESCRIPTION:
XS GIS Cut Line= 3
      2483024.96     13572574.99      2483625.00     13572725.00
      2484225.02     13572574.99
#Sta/Elev= 30
  4381.0  265.46  4432.6  262.99  4440.3  261.54  4445.5  262.61  4463.5  258.99
  4481.5  256.97  4504.7  256.96  4522.8  255.55  4610.4  252.78  4646.5  250.44
  4734.1  247.05  4793.4  246.01  4886.1  246.40  4893.9  244.71  4915.0  243.59
  4915.3  243.09  4918.8  243.09  4919.0  243.59  4996.9  246.04  5040.7  245.22
  5082.0  246.29  5112.9  245.64  5146.4  246.31  5174.7  245.90  5277.8  248.94
  5344.9  251.70  5435.0  255.43  5553.6  261.72  5587.1  262.35  5618.0  261.38
#Mann=4,-1,0
  4381.0   0.035       0  4915.0   0.035       0  4919.0   0.035       0
  5344.9    0.05       0
Bank Sta=4915,4919
Exp/Cntr=0.3,0.1

Type RM Length L Ch R = 1,7543,450,450,450
BEGIN DESCRIPTION:
Stream0837 10.0
END DESCRIPTION:
XS GIS Cut Line= 3
      2483224.96     13573375.00      2483825.00     13573425.00
      2484125.02     13573224.99
#Sta/Elev= 30
  4397.9  254.71  4446.9  253.07  4508.3  251.35  4709.0  243.72  4749.2  243.41
  4759.2  242.63  4809.4  241.55  4899.7  241.41  4919.7  240.28  4929.8  238.36
  4935.3  236.59  4935.6  236.09  4939.1  236.09  4939.3  236.59  4942.3  239.89
  4959.9  236.77  4969.9  236.71  4990.0  238.56  5003.0  238.11  5013.5  240.43
  5028.6  241.17  5046.1  240.92  5064.6  241.84  5130.7  241.46  5151.8  245.66
  5166.5  246.34  5208.8  245.30  5229.9  245.49  5359.3  251.49  5360.6  251.49
#Mann=7,-1,0
  4397.9    0.05       0  4446.9     0.1       0  4935.3    0.05       0
  4939.3     0.1       0  5046.1   0.035       0  5166.5   0.063       0
  5359.3    0.12       0
Bank Sta=4935.3,4939.3
Exp/Cntr=0.3,0.1

Type RM Length L Ch R = 1,7093,471,471,471
BEGIN DESCRIPTION:
Stream0837 9.0
END DESCRIPTION:
XS GIS Cut Line= 3
      2483674.99     13574125.01      2483975.00     13573825.00
      2484325.00     13573275.00
#Sta/Elev= 30
  4575.1  247.42  4702.4  243.22  4716.5  242.19  4759.0  242.91  4783.3  241.49
  4886.2  238.41  4957.0  238.11  4969.1  232.98  4969.3  232.48  4973.1  232.98
  4985.2  238.34  5189.0  238.79  5252.5  240.62  5288.9  242.50  5295.7  241.95
  5333.3  243.43  5346.5  243.36  5357.8  244.91  5367.7  246.19  5382.9  246.80
  5413.4  246.04  5434.6  248.67  5461.7  249.51  5501.2  251.92  5564.9  255.44
  5580.2  255.44  5601.3  257.08  5607.3  256.45  5637.8  256.84  5651.3  255.99
#Mann=7,-1,0
  4575.1    0.05       0  4783.3     0.1       0  4969.1    0.05       0
  4973.1     0.1       0  5333.3   0.035       0  5357.8   0.063       0
  5501.2    0.12       0
Bank Sta=4969.1,4973.1
Exp/Cntr=0.3,0.1

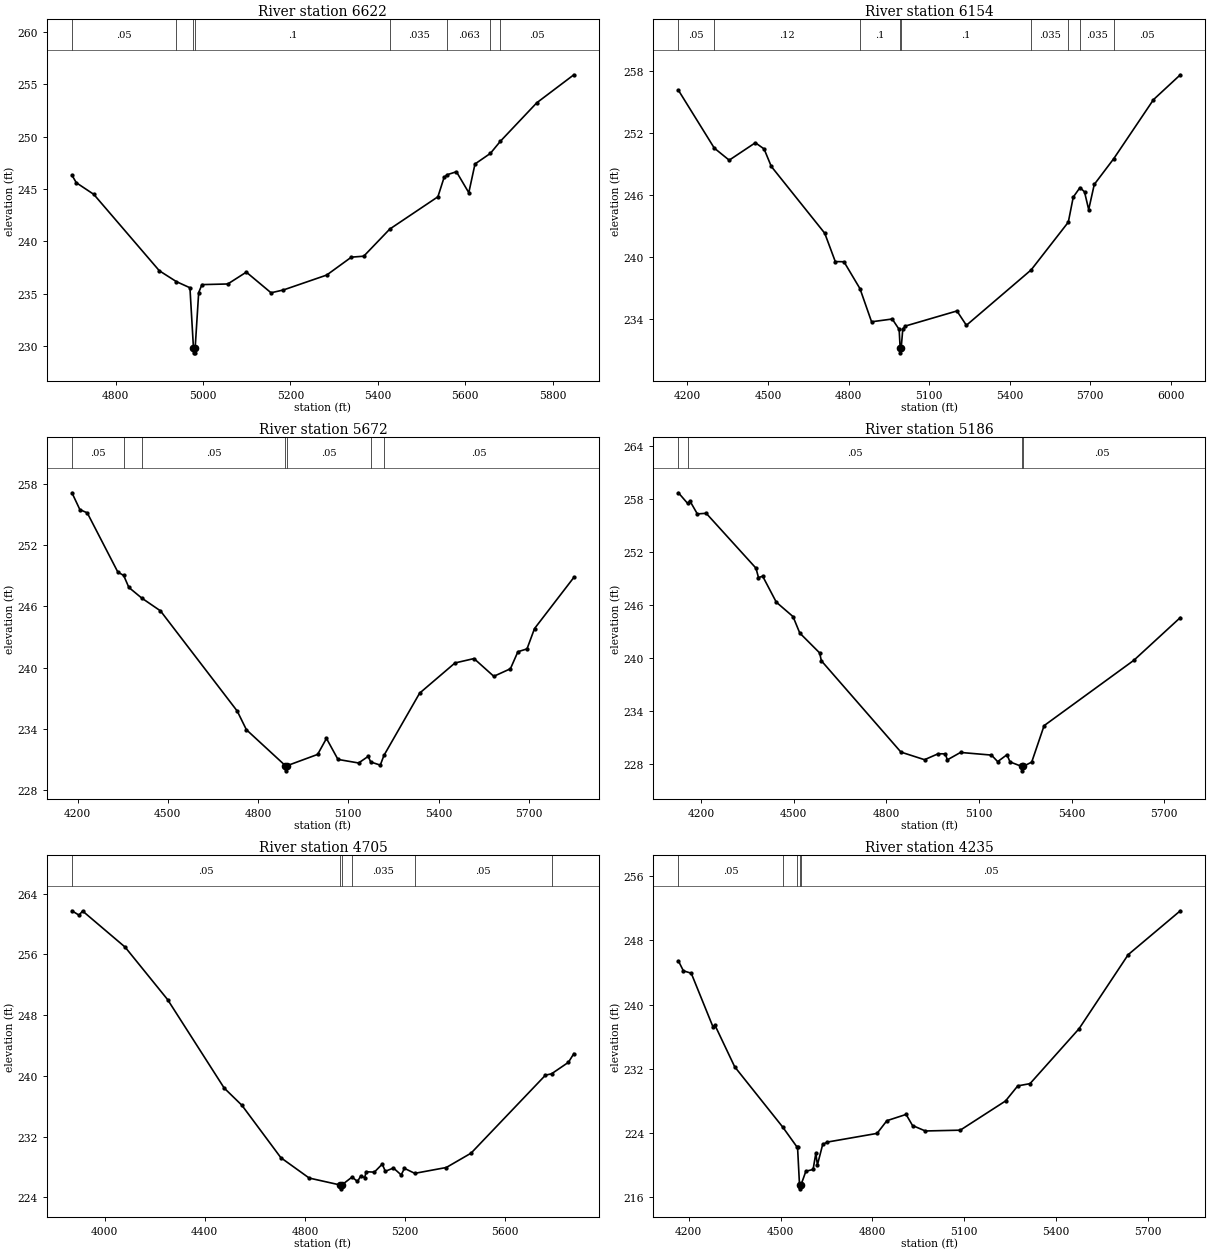
Type RM Length L Ch R = 1,6622,468,468,468
BEGIN DESCRIPTION:
Stream0837 8.0
END DESCRIPTION:
XS GIS Cut Line= 3
      2483874.98     13574225.00      2484175.00     13574225.00
      2484774.97     13573625.03
#Sta/Elev= 30
  4700.3  246.31  4710.3  245.59  4750.3  244.48  4900.3  237.19  4939.5  236.15
  4970.3  235.57  4978.3  229.86  4978.6  229.36  4982.1  229.36  4982.3  229.86
  4990.3  235.11  4997.8  235.87  5056.9  235.93  5099.3  237.06  5155.9  235.09
  5184.2  235.36  5283.2  236.78  5339.7  238.49  5368.0  238.58  5427.6  241.17
  5537.7  244.25  5551.9  246.10  5559.4  246.36  5580.1  246.64  5608.4  244.64
  5622.6  247.38  5657.8  248.39  5680.5  249.54  5764.0  253.22  5848.8  255.89
#Mann=8,-1,0
  4700.3    0.05       0  4939.5     0.1       0  4978.3    0.05       0
  4982.3     0.1       0  5427.6   0.035       0  5559.4   0.063       0
  5657.8   0.035       0  5680.5    0.05       0
Bank Sta=4978.3,4982.3
Exp/Cntr=0.3,0.1

Type RM Length L Ch R = 1,6154,482,482,482
BEGIN DESCRIPTION:
Stream0837 7.0
END DESCRIPTION:
XS GIS Cut Line= 3
      2483675.03     13574824.99      2484475.00     13574575.00
      2485125.00     13573775.00
#Sta/Elev= 30
  4166.2  256.17  4299.8  250.56  4355.3  249.39  4452.7  251.08  4485.2  250.48
  4511.9  248.79  4711.0  242.31  4750.3  239.56  4782.7  239.54  4842.3  236.93
  4885.4  233.72  4962.4  233.99  4988.1  232.98  4991.8  231.21  4992.1  230.71
  4995.8  231.21  5001.7  233.02  5011.5  233.31  5203.3  234.77  5238.5  233.38
  5479.6  238.75  5618.0  243.38  5636.4  245.81  5661.4  246.73  5678.3  246.32
  5693.9  244.60  5714.7  247.04  5787.3  249.54  5935.2  255.26  6035.1  257.67
#Mann=9,-1,0
  4166.2    0.05       0  4299.8    0.12       0  4842.3     0.1       0
  4991.8    0.05       0  4995.8     0.1       0  5479.6   0.035       0
  5618.0   0.063       0  5661.4   0.035       0  5787.3    0.05       0
Bank Sta=4991.8,4995.8
Exp/Cntr=0.3,0.1

Type RM Length L Ch R = 1,5672,486,486,486
BEGIN DESCRIPTION:
Stream0837 6.0
END DESCRIPTION:
XS GIS Cut Line= 3
      2483675.02     13574875.00      2484475.00     13575025.00
      2485274.98     13575324.99
#Sta/Elev= 30
  4181.5  257.15  4207.8  255.50  4232.4  255.18  4334.1  249.37  4353.5  249.04
  4370.6  247.87  4413.2  246.83  4475.7  245.57  4730.9  235.74  4761.4  233.91
  4891.2  230.38  4891.6  229.88  4896.1  230.38  4998.1  231.49  5027.5  233.06
  5065.7  231.00  5134.3  230.65  5166.3  231.30  5174.5  230.75  5206.4  230.44
  5218.5  231.39  5337.2  237.50  5454.7  240.46  5517.9  240.89  5583.7  239.15
  5638.9  239.89  5663.8  241.56  5694.1  241.84  5719.0  243.83  5849.8  248.85
#Mann=7,-1,0
  4181.5    0.05       0  4353.5    0.12       0  4413.2    0.05       0
  4891.2    0.05       0  4896.1    0.05       0  5174.5    0.12       0
  5218.5    0.05       0
Bank Sta=4891.2,4896.1
Exp/Cntr=0.3,0.1

Type RM Length L Ch R = 1,5186,481,481,481
BEGIN DESCRIPTION:
Stream0837 5.0
END DESCRIPTION:
XS GIS Cut Line= 3
      2483575.01     13575125.00      2484375.00     13575475.00
      2485125.03     13575525.00
#Sta/Elev= 30
  4126.8  258.72  4156.6  257.52  4164.6  257.76  4188.0  256.33  4216.8  256.40
  4377.8  250.20  4386.0  249.14  4399.7  249.28  4443.7  246.35  4497.9  244.72
  4519.7  242.86  4584.1  240.61  4589.5  239.73  4847.2  229.40  4923.6  228.54
  4967.6  229.21  4991.0  229.20  4997.3  228.52  5040.1  229.36  5140.3  229.06
  5160.4  228.32  5190.4  229.10  5200.4  228.29  5238.1  227.78  5238.4  227.28
  5243.0  227.78  5270.6  228.27  5310.7  232.39  5601.3  239.78  5751.7  244.61
#Mann=4,-1,0
  4126.8    0.07       0  4156.6    0.05       0  5238.1    0.05       0
  5243.0    0.05       0
Bank Sta=5238.1,5243
Exp/Cntr=0.3,0.1

Type RM Length L Ch R = 1,4705,470,470,470
BEGIN DESCRIPTION:
Stream0837 4.0
END DESCRIPTION:
XS GIS Cut Line= 3
      2483474.97     13575124.97      2484275.00     13575925.00
      2485074.98     13575575.01
#Sta/Elev= 30
  3869.7  261.74  3898.0  261.16  3912.2  261.71  4081.9  256.96  4251.6  250.05
  4477.8  238.39  4548.6  236.12  4704.1  229.22  4817.3  226.54  4942.0  225.62
  4942.4  225.12  4947.0  225.62  4988.5  226.67  5010.1  226.09  5022.9  226.79
  5038.9  226.61  5044.8  227.37  5077.5  227.32  5109.1  228.38  5121.2  227.43
  5153.9  227.86  5184.7  226.95  5197.6  227.82  5238.9  227.16  5364.8  227.93
  5463.8  229.82  5760.9  240.09  5785.2  240.27  5852.5  241.78  5874.3  242.93
#Mann=6,-1,0
  3869.7    0.05       0  4942.0   0.035       0  4947.0    0.05       0
  4988.5   0.035       0  5238.9    0.05       0  5785.2   0.035       0
Bank Sta=4942,4947
Exp/Cntr=0.3,0.1

Type RM Length L Ch R = 1,4235,461,461,461
BEGIN DESCRIPTION:
Stream0837 3.0
END DESCRIPTION:
XS GIS Cut Line= 3
      2483675.03     13576574.99      2484475.00     13576325.00
      2485275.02     13576375.00
#Sta/Elev= 30
  4166.2  245.43  4182.4  244.20  4208.1  243.90  4279.8  237.16  4285.1  237.47
  4350.0  232.26  4506.9  224.76  4553.2  222.30  4555.4  222.26  4561.8  217.57
  4562.1  217.07  4566.8  217.57  4582.6  219.26  4606.2  219.48  4615.1  221.48
  4620.3  220.05  4637.6  222.60  4652.8  222.89  4815.2  223.97  4847.2  225.55
  4910.0  226.33  4931.0  224.95  4972.9  224.27  5087.0  224.37  5234.8  228.00
  5274.8  229.88  5314.9  230.16  5475.2  237.00  5635.6  246.21  5805.9  251.67
#Mann=5,-1,0
  4166.2    0.05       0  4506.9   0.035       0  4553.2    0.05       0
  4561.8    0.05       0  4566.8    0.05       0
Bank Sta=4561.8,4566.8
Exp/Cntr=0.3,0.1

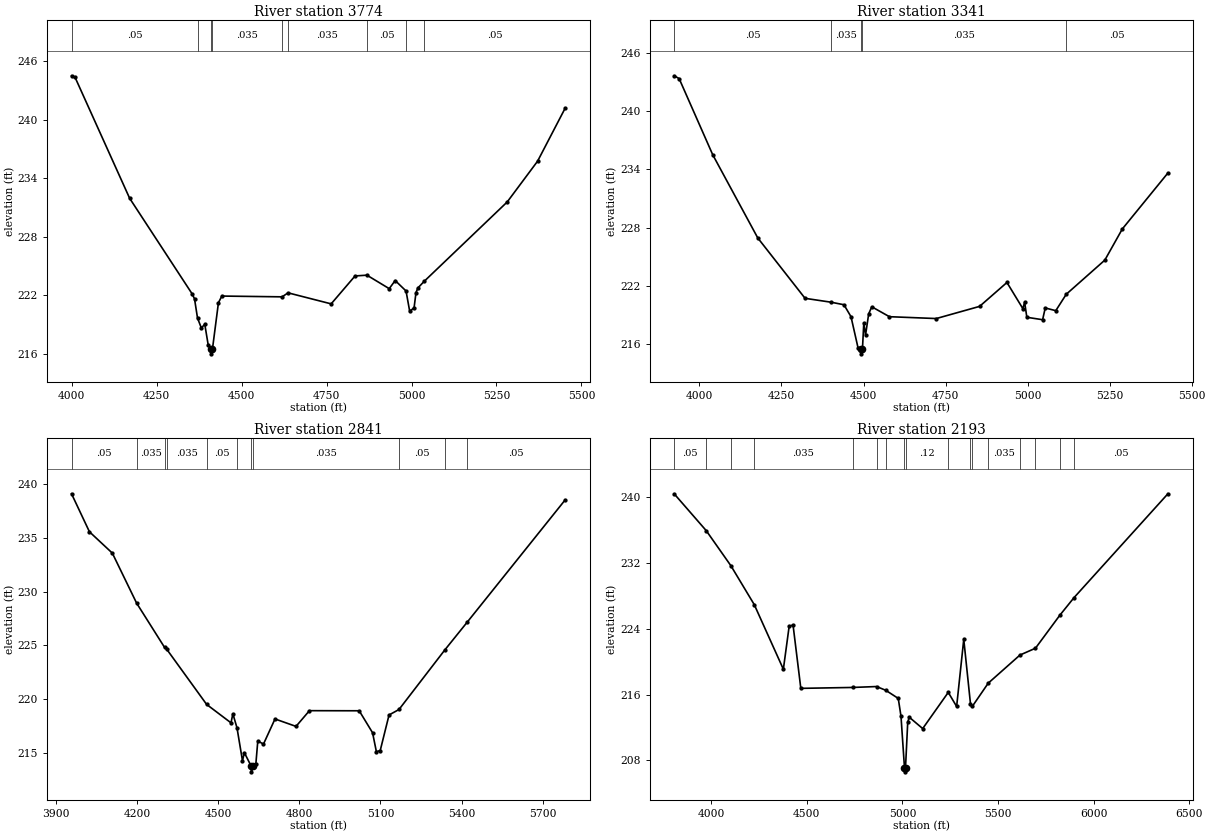
Type RM Length L Ch R = 1,3774,433,433,433
BEGIN DESCRIPTION:
Stream0837 2.0
END DESCRIPTION:
XS GIS Cut Line= 3
      2483674.99     13576625.00      2484675.00     13576725.00
      2485074.99     13576525.00
#Sta/Elev= 30
  3999.8  244.49  4009.9  244.35  4170.7  231.94  4354.1  222.17  4361.6  221.64
  4370.4  219.67  4381.7  218.65  4391.8  219.03  4401.8  216.92  4409.3  216.50
  4409.7  216.00  4414.4  216.50  4432.0  221.24  4442.0  221.92  4619.3  221.84
  4636.8  222.25  4763.6  221.12  4833.9  223.98  4868.8  224.06  4934.4  222.68
  4952.0  223.51  4983.9  222.44  4994.7  220.35  5007.6  220.73  5013.2  222.28
  5018.8  222.75  5037.0  223.42  5281.5  231.56  5370.9  235.74  5452.0  241.17
#Mann=9,-1,0
  3999.8    0.05       0  4370.4   0.035       0  4409.3   0.035       0
  4414.4   0.035       0  4619.3    0.05       0  4636.8   0.035       0
  4868.8    0.05       0  4983.9   0.035       0  5037.0    0.05       0
Bank Sta=4409.3,4414.4
Exp/Cntr=0.3,0.1

Type RM Length L Ch R = 1,3341,500,500,500
BEGIN DESCRIPTION:
Stream0837 1.0
END DESCRIPTION:
XS GIS Cut Line= 3
      2483675.01     13576725.01      2484675.00     13577125.00
      2485074.98     13577274.99
#Sta/Elev= 30
  3923.4  243.62  3938.2  243.33  4040.5  235.50  4177.8  226.94  4321.9  220.73
  4401.3  220.33  4440.4  220.07  4461.9  218.84  4483.4  215.63  4491.7  215.52
  4492.1  215.02  4496.8  215.52  4500.9  218.19  4506.3  216.97  4515.8  219.13
  4525.2  219.86  4579.0  218.84  4721.7  218.65  4853.7  219.90  4937.1  222.36
  4985.6  219.67  4991.0  220.34  4997.7  218.78  5045.8  218.53  5053.8  219.74
  5085.9  219.46  5117.9  221.15  5235.4  224.66  5288.8  227.87  5427.6  233.62
#Mann=5,-1,0
  3923.4    0.05       0  4401.3   0.035       0  4491.7   0.035       0
  4496.8   0.035       0  5117.9    0.05       0
Bank Sta=4491.7,4496.8
Exp/Cntr=0.3,0.1

Type RM Length L Ch R = 1,2841,648,648,648
BEGIN DESCRIPTION:
XS7806
END DESCRIPTION:
XS GIS Cut Line= 3
      2483706.41     13576820.16      2484547.07     13577627.19
      2485174.81     13577425.42
#Sta/Elev= 30
  3957.9  239.08  4024.1  235.55  4108.7  233.57  4198.4  228.93  4301.9  224.81
  4309.3  224.66  4457.3  219.52  4547.4  217.81  4554.3  218.65  4569.6  217.34
  4589.8  214.29  4596.8  215.04  4622.5  213.76  4622.9  213.26  4627.6  213.76
  4639.2  213.97  4646.4  216.12  4667.5  215.84  4710.0  218.17  4787.7  217.48
  4837.3  218.94  5021.3  218.93  5070.7  216.89  5084.8  215.13  5099.0  215.24
  5131.6  218.54  5168.4  219.05  5337.8  224.58  5420.9  227.17  5782.6  238.51
#Mann=11,-1,0
  3957.9    0.05       0  4198.4   0.035       0  4301.9    0.05       0
  4309.3   0.035       0  4457.3    0.05       0  4569.6   0.035       0
  4622.5   0.035       0  4627.6   0.035       0  5168.4    0.05       0
  5337.8   0.035       0  5420.9    0.05       0
Bank Sta=4622.5,4627.6
Exp/Cntr=0.3,0.1

Type RM Length L Ch R = 1,2193,0,0,0
BEGIN DESCRIPTION:
XS7805
END DESCRIPTION:
XS GIS Cut Line= 4
      2483661.59     13576842.58      2483807.30     13577728.07
      2484188.40     13578041.91      2485230.41     13577470.49
#Sta/Elev= 30
  3807.9  240.34  3974.7  235.89  4103.4  231.64  4225.8  226.91  4377.9  219.07
  4408.3  224.30  4428.6  224.42  4469.1  216.75  4740.0  216.86  4864.8  216.97
  4912.6  216.52  4978.3  215.53  4992.6  213.37  5010.8  207.12  5011.2  206.62
  5016.2  207.12  5027.8  212.64  5035.7  213.25  5106.0  211.87  5239.6  216.26
  5283.4  214.55  5320.6  222.70  5355.7  214.88  5365.2  214.56  5448.5  217.38
  5614.2  220.79  5695.3  221.62  5822.9  225.63  5896.5  227.75  6387.4  240.36
#Mann=17,-1,0
  3807.9    0.05       0  3974.7    0.07       0  4103.4    0.05       0
  4225.8   0.035       0  4740.0    0.12       0  4864.8   0.035       0
  4912.6    0.12       0  5010.8    0.05       0  5016.2    0.12       0
  5239.6    0.05       0  5355.7   0.035       0  5365.2    0.05       0
  5448.5   0.035       0  5614.2    0.07       0  5695.3    0.05       0
  5822.9    0.07       0  5896.5    0.05       0
Bank Sta=5010.8,5016.2
Exp/Cntr=0.3,0.1

Chan Stop Cuts=-1