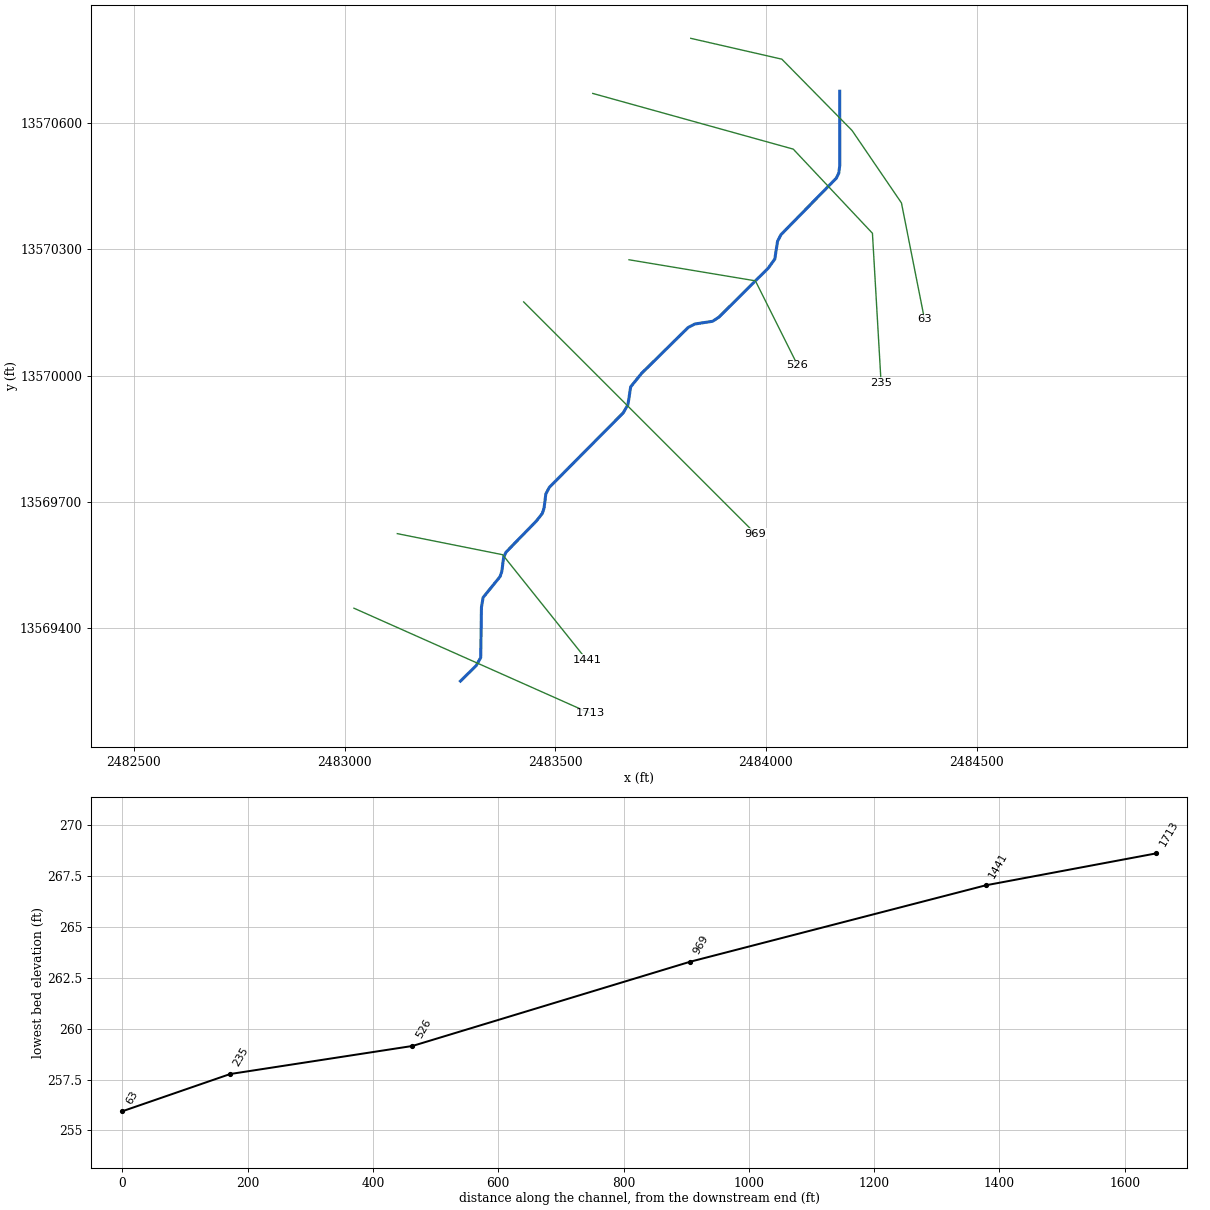
--- Stream0838.prj (project) ---

Proj Title=Stream0838 Base Level Engineering
Current Plan=p01
Default Exp/Contr=0.3,0.1
English Units
Geom File=g01
Flow File=f01
Plan File=p01
Y Axis Title=Elevation
X Axis Title(PF)=Main Channel Distance
X Axis Title(XS)=Station
BEGIN DESCRIPTION:
Stream0838
END DESCRIPTION:
DSS Export Rating Curves= 0
DSS Export Rating Curve Sorted= 0
DSS Export Volume Flow Curves= 0
DXF OffsetX= 0
DXF OffsetY= 0
DXF ScaleX= 1
DXF ScaleY= 10

--- Stream0838.p01 (plan) ---

Plan Title=Multiple Run
Short Identifier=Multiple
Geom File=g01
Flow File=f01
Subcritical Flow
K Sum by GR= 0
Std Step Tol= 0.01
Critical Tol= 0.01
Num of Std Step Trials= 20
Max Error Tol= 0.3
Flow Tol Ratio= 0.001
Split Flow NTrial= 30
Split Flow Tol= 0.02
Split Flow Ratio= 0.02
Log Output Level= 0
Friction Slope Method= 1
Unsteady Friction Slope Method= 2
Unsteady Bridges Friction Slope Method= 1
Parabolic Critical Depth
Global Vel Dist=  1 , 1 , 1
Global Log Level= 0
CheckData=True
Encroach Param= -1, 0, 0, 0
BEGIN DESCRIPTION:
Multiple Run
END DESCRIPTION:

--- Stream0838.f01 (steady flow) ---

Flow Title=Multiple
Program Version=4.10
Number of Profiles= 7
Profile Names=10-year,25-year,50-year,1pct_min,100-year,1pct_plu,500-year
River Rch & RM=Stream0838,Reach-1         ,1713
     266     407     528     334     666    1328    1043
River Rch & RM=Stream0838,Reach-1         ,63
     690    1119    1510     987    1968    3927    3314
Boundary for River Rch & Prof#=Stream0838,Reach-1         , 1
Up Type= 0
Dn Type= 3
Dn Slope=0.01
Boundary for River Rch & Prof#=Stream0838,Reach-1         , 2
Up Type= 0
Dn Type= 3
Dn Slope=0.01
Boundary for River Rch & Prof#=Stream0838,Reach-1         , 3
Up Type= 0
Dn Type= 3
Dn Slope=0.01
Boundary for River Rch & Prof#=Stream0838,Reach-1         , 4
Up Type= 0
Dn Type= 3
Dn Slope=0.01
Boundary for River Rch & Prof#=Stream0838,Reach-1         , 5
Up Type= 0
Dn Type= 3
Dn Slope=0.01
Boundary for River Rch & Prof#=Stream0838,Reach-1         , 6
Up Type= 0
Dn Type= 3
Dn Slope=0.01
Boundary for River Rch & Prof#=Stream0838,Reach-1         , 7
Up Type= 0
Dn Type= 3
Dn Slope=0.01
DSS Import GetInterval= 0
DSS Import GetPeak= 0
DSS Import FillOption= 0

--- Stream0838.g01 (geometry) ---

Geom Title=Existing Conditions

River Reach=Stream0838,Reach-1
Reach XY= 30
      2483275.00     13569275.00      2483312.08     13569311.50
      2483323.09     13569330.79      2483324.81     13569450.08
      2483328.75     13569473.45      2483368.86     13569522.83
      2483373.28     13569535.71      2483377.50     13569568.96
      2483383.16     13569581.05      2483455.17     13569654.93
      2483469.13     13569672.72      2483473.44     13569685.64
      2483477.53     13569718.95      2483485.78     13569734.68
      2483661.37     13569911.79      2483672.47     13569931.05
      2483678.98     13569973.35      2483704.61     13570005.16
      2483815.32     13570114.22      2483831.05     13570122.47
      2483873.35     13570128.98      2483888.21     13570138.63
      2484005.21     13570254.91      2484021.02     13570276.65
      2484027.54     13570318.95      2484035.78     13570334.68
      2484167.19     13570468.81      2484172.95     13570480.85
      2484175.31     13570499.87      2484175.00     13570675.00

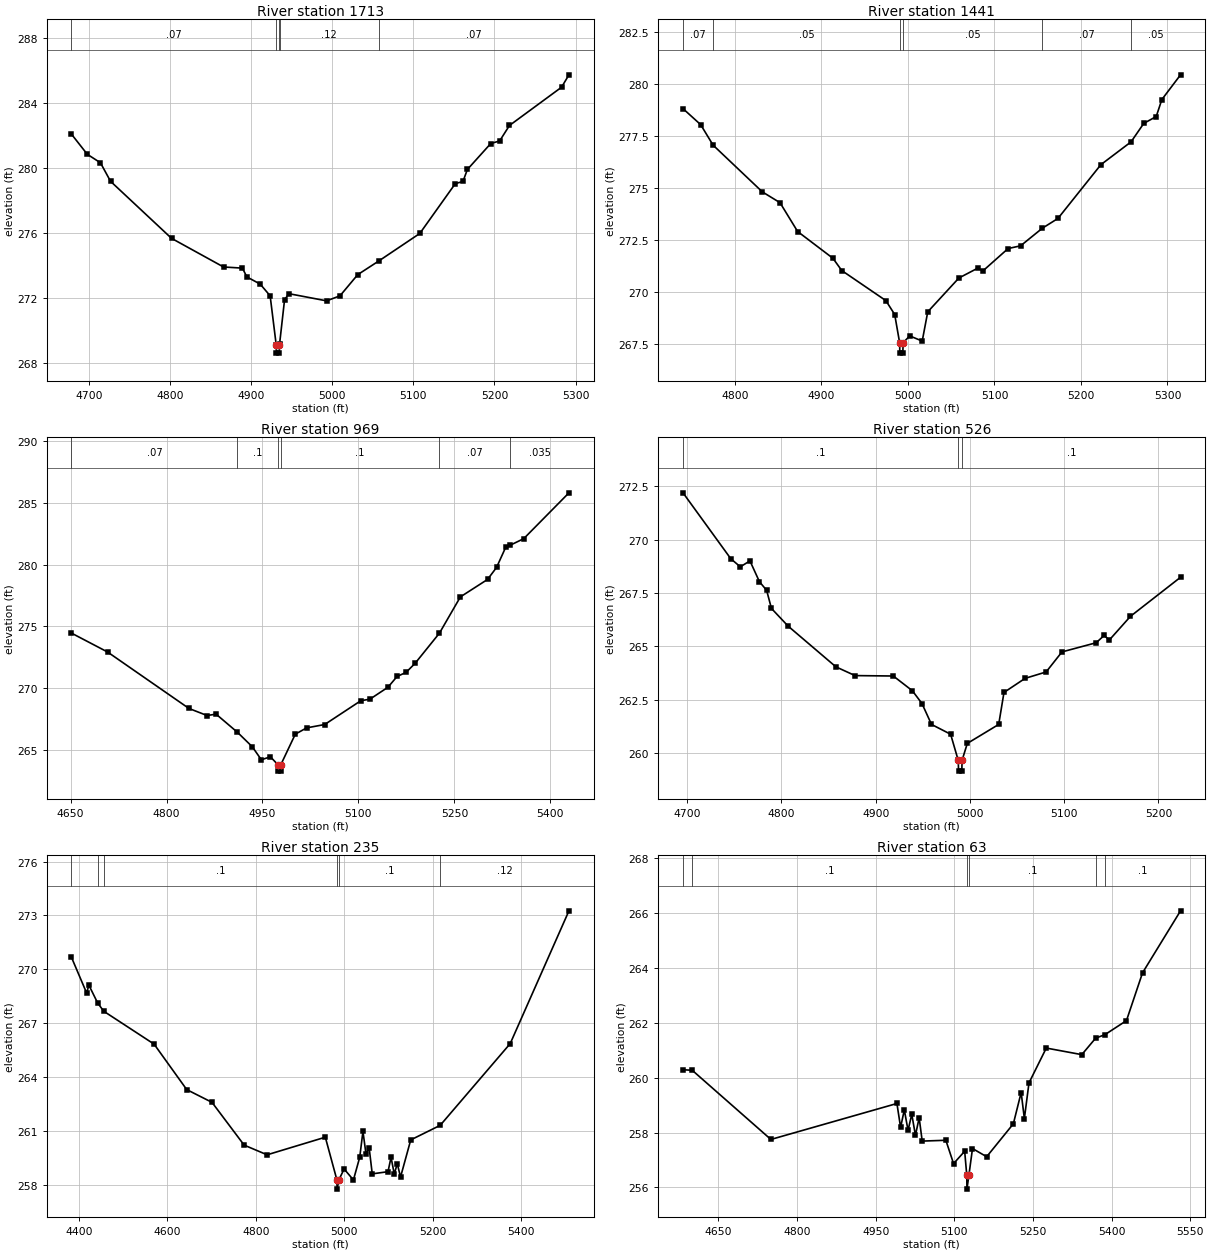
Type RM Length L Ch R = 1,1713,272,272,272
BEGIN DESCRIPTION:
XS7818
END DESCRIPTION:
XS GIS Cut Line= 2
      2483022.26     13569448.02      2483583.13     13569198.42
#Sta/Elev= 30
  4678.0  282.07  4697.6  280.83  4713.8  280.31  4726.3  279.17  4801.5  275.67
  4865.7  273.91  4889.0  273.84  4894.5  273.30  4910.9  272.86  4923.2  272.14
  4930.7  269.12  4931.0  268.62  4934.5  268.62  4934.7  269.12  4934.8  269.16
  4941.0  271.90  4946.4  272.27  4992.9  271.83  5009.4  272.14  5031.3  273.44
  5057.0  274.27  5107.9  275.97  5151.7  279.03  5161.1  279.16  5166.6  279.90
  5195.4  281.49  5206.4  281.65  5218.5  282.60  5282.8  284.95  5291.9  285.71
#Mann=5,-1,0
  4678.0    0.07       0  4930.7    0.05       0  4934.7    0.07       0
  4934.8    0.12       0  5057.0    0.07       0
Bank Sta=4930.7,4934.7
Exp/Cntr=0.3,0.1

Type RM Length L Ch R = 1,1441,472,472,472
BEGIN DESCRIPTION:
Stream0838 3.0
END DESCRIPTION:
XS GIS Cut Line= 3
      2483125.05     13569624.99      2483375.00     13569575.00
      2483575.02     13569324.97
#Sta/Elev= 30
  4740.0  278.83  4760.4  278.06  4774.8  277.07  4831.7  274.82  4852.1  274.30
  4872.5  272.91  4913.3  271.62  4923.5  271.03  4974.5  269.58  4984.7  268.91
  4990.4  267.55  4990.6  267.05  4994.1  267.05  4994.4  267.55  5002.1  267.88
  5016.5  267.63  5022.9  269.04  5058.9  270.67  5080.5  271.14  5086.9  271.02
  5115.8  272.09  5130.2  272.22  5155.4  273.07  5173.4  273.54  5223.0  276.13
  5257.9  277.23  5272.6  278.12  5287.0  278.45  5293.5  279.27  5315.1  280.46
#Mann=6,-1,0
  4740.0    0.07       0  4774.8    0.05       0  4990.4    0.05       0
  4994.4    0.05       0  5155.4    0.07       0  5257.9    0.05       0
Bank Sta=4990.4,4994.4
Exp/Cntr=0.3,0.1

Type RM Length L Ch R = 1,969,443,443,443
BEGIN DESCRIPTION:
Stream0838 2.0
END DESCRIPTION:
XS GIS Cut Line= 3
      2483425.03     13570174.97      2483675.00     13569925.00
      2483975.02     13569624.98
#Sta/Elev= 30
  4651.3  274.46  4707.8  272.93  4835.1  268.36  4863.4  267.79  4877.5  267.90
  4910.9  266.43  4934.1  265.26  4948.2  264.21  4962.4  264.45  4974.5  263.79
  4974.8  263.29  4978.3  263.29  4978.5  263.79  5001.3  266.28  5019.0  266.79
  5047.2  267.06  5103.8  268.99  5117.9  269.11  5146.2  270.08  5160.4  270.95
  5174.5  271.28  5188.7  272.02  5226.7  274.46  5259.4  277.39  5301.8  278.80
  5315.9  279.77  5330.1  281.39  5337.2  281.57  5358.4  282.10  5429.1  285.81
#Mann=6,-1,0
  4651.3    0.07       0  4910.9     0.1       0  4974.5    0.05       0
  4978.5     0.1       0  5226.7    0.07       0  5337.2   0.035       0
Bank Sta=4974.5,4978.5
Exp/Cntr=0.3,0.1

Type RM Length L Ch R = 1,526,291,291,291
BEGIN DESCRIPTION:
Stream0838 1.0
END DESCRIPTION:
XS GIS Cut Line= 3
      2483674.98     13570275.00      2483975.00     13570225.00
      2484075.02     13570024.97
#Sta/Elev= 30
  4695.6  272.20  4746.3  269.11  4756.4  268.73  4766.6  269.01  4776.7  268.03
  4784.3  267.63  4789.4  266.78  4807.1  265.95  4857.8  264.04  4878.1  263.63
  4918.7  263.61  4938.9  262.92  4949.1  262.32  4959.2  261.34  4979.5  260.88
  4987.6  259.65  4987.9  259.15  4991.4  259.15  4991.6  259.65  4997.2  260.45
  5030.5  261.34  5036.1  262.84  5058.5  263.50  5080.8  263.80  5097.6  264.74
  5133.9  265.17  5142.3  265.51  5147.9  265.30  5170.3  266.41  5223.4  268.24
#Mann=3,-1,0
  4695.6     0.1       0  4987.6    0.05       0  4991.6     0.1       0
Bank Sta=4987.6,4991.6
Exp/Cntr=0.3,0.1

Type RM Length L Ch R = 1,235,172,172,172
BEGIN DESCRIPTION:
XS7817
END DESCRIPTION:
XS GIS Cut Line= 4
      2483589.03     13570669.75      2484064.79     13570537.59
      2484252.75     13570337.89      2484273.31     13569982.50
#Sta/Elev= 30
  4383.5  270.68  4417.8  268.69  4423.0  269.12  4442.8  268.13  4456.6  267.67
  4570.3  265.84  4644.0  263.31  4701.1  262.60  4773.7  260.22  4825.6  259.68
  4957.1  260.66  4983.4  258.27  4983.7  257.77  4987.4  258.27  4999.6  258.89
  5020.6  258.28  5034.8  259.54  5042.1  260.98  5048.9  259.74  5056.2  260.05
  5063.1  258.62  5098.7  258.74  5105.6  259.54  5112.9  258.61  5119.7  259.19
  5127.0  258.44  5150.1  260.51  5216.6  261.32  5374.8  265.87  5507.5  273.26
#Mann=6,-1,0
  4383.5   0.035       0  4442.8    0.07       0  4456.6     0.1       0
  4983.4    0.05       0  4987.4     0.1       0  5216.6    0.12       0
Bank Sta=4983.4,4987.4
Exp/Cntr=0.3,0.1

Type RM Length L Ch R = 1,63,0,0,0
BEGIN DESCRIPTION:
H21127
END DESCRIPTION:
XS GIS Cut Line= 5
      2483821.64     13570800.51      2484037.76     13570751.04
      2484204.43     13570581.77      2484321.61     13570409.90
      2484376.30     13570133.84
#Sta/Elev= 30
  4582.6  260.29  4600.2  260.27  4750.2  257.75  4990.5  259.06  4997.5  258.19
  5004.6  258.83  5011.7  258.08  5018.8  258.67  5025.8  257.90  5032.9  258.54
  5038.7  257.69  5083.8  257.72  5098.5  256.87  5119.7  257.32  5123.7  256.44
  5124.0  255.94  5127.7  256.44  5134.6  257.42  5161.6  257.12  5212.5  258.32
  5227.4  259.46  5233.5  258.51  5242.3  259.81  5275.3  261.08  5343.0  260.84
  5369.4  261.44  5387.3  261.57  5428.2  262.08  5458.8  263.82  5531.3  266.08
#Mann=6,-1,0
  4582.6    0.07       0  4600.2     0.1       0  5123.7    0.05       0
  5127.7     0.1       0  5369.4    0.12       0  5387.3     0.1       0
Bank Sta=5123.7,5127.7
Exp/Cntr=0.3,0.1

Chan Stop Cuts=-1