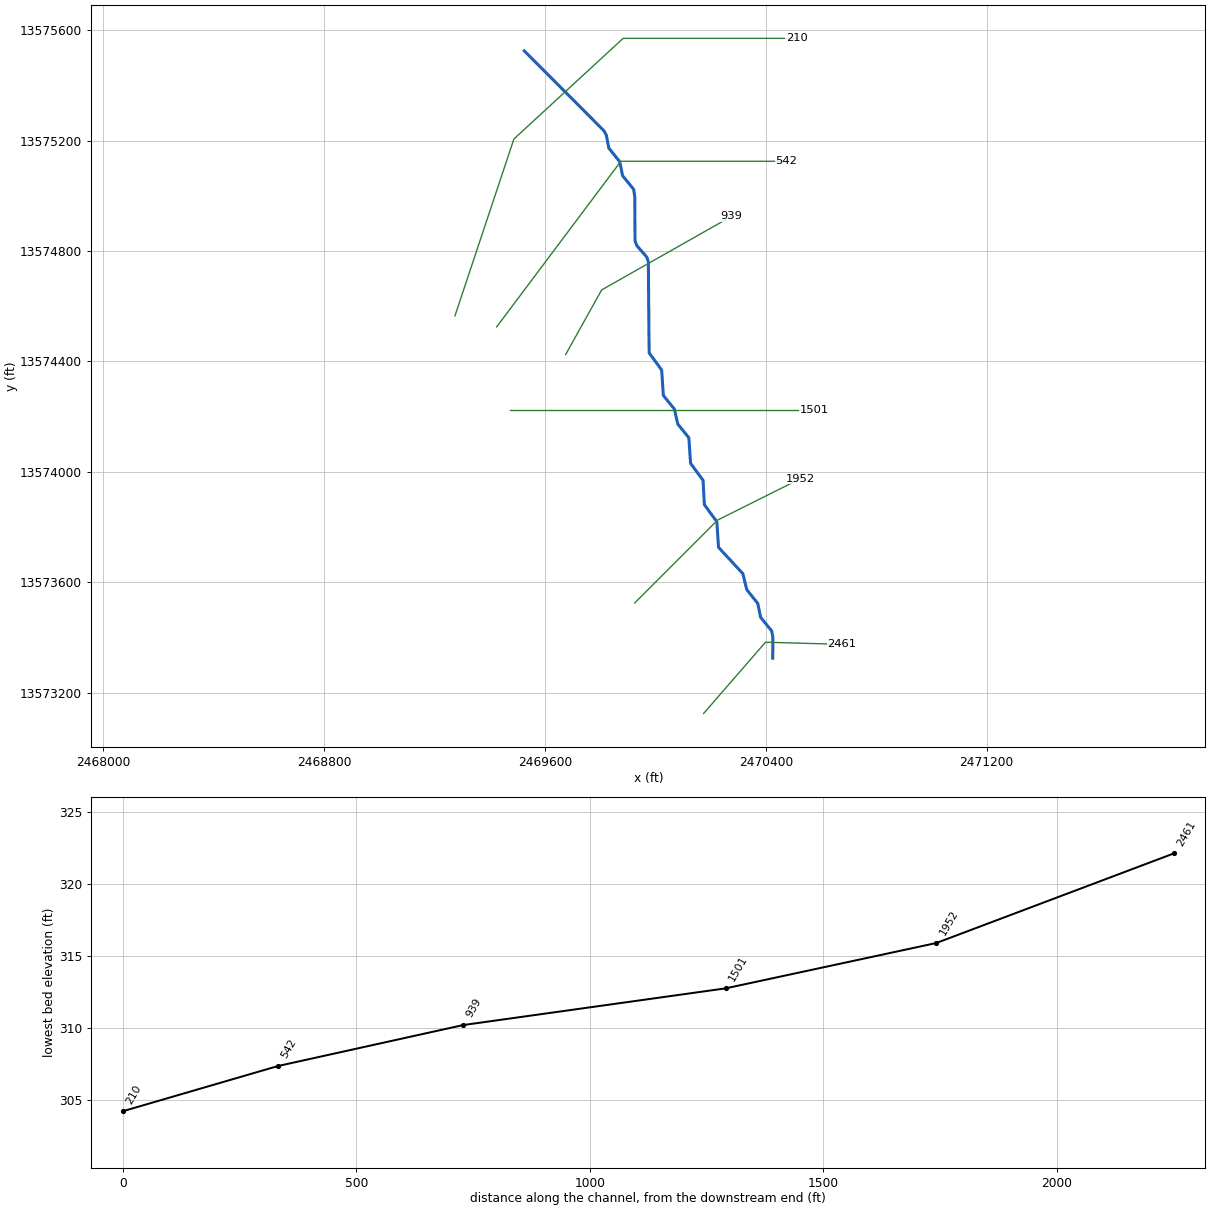
--- Stream0840.prj (project) ---

Proj Title=Stream0840 Base Level Engineering
Current Plan=p01
Default Exp/Contr=0.3,0.1
English Units
Geom File=g01
Flow File=f01
Plan File=p01
BEGIN DESCRIPTION:
Stream0840
END DESCRIPTION:

--- Stream0840.p01 (plan) ---

Plan Title=Multiple Run
Short Identifier=Multiple
Geom File=g01
Flow File=f01
Subcritical Flow
K Sum by GR= 0
Std Step Tol= 0.01
Critical Tol= 0.01
Num of Std Step Trials= 20
Max Error Tol= 0.3
Flow Tol Ratio= 0.001
Split Flow NTrial= 30
Split Flow Tol= 0.02
Split Flow Ratio= 0.02
Log Output Level= 0
Friction Slope Method= 1
Unsteady Friction Slope Method= 2
Unsteady Bridges Friction Slope Method= 1
Parabolic Critical Depth
Global Vel Dist=  1 , 1 , 1
Global Log Level= 0
CheckData=True
Encroach Param= -1, 0, 0, 0
BEGIN DESCRIPTION:
Multiple Run
END DESCRIPTION:

--- Stream0840.f01 (steady flow) ---

Flow Title=Multiple
Number of Profiles=7
Profile Names=10-year,25-year,50-year,1pct_min,100-year,1pct_plu,500-year
River Rch & RM= Stream0840,Reach-1,2461
     275     421     545     344     686    1369    1072
Boundary for River Rch & Prof#=Stream0840,Reach-1,1
Up Type=0
Dn Type=3
Dn Slope=0.005
Boundary for River Rch & Prof#=Stream0840,Reach-1,2
Up Type=0
Dn Type=3
Dn Slope=0.005
Boundary for River Rch & Prof#=Stream0840,Reach-1,3
Up Type=0
Dn Type=3
Dn Slope=0.005
Boundary for River Rch & Prof#=Stream0840,Reach-1,4
Up Type=0
Dn Type=3
Dn Slope=0.005
Boundary for River Rch & Prof#=Stream0840,Reach-1,5
Up Type=0
Dn Type=3
Dn Slope=0.005
Boundary for River Rch & Prof#=Stream0840,Reach-1,6
Up Type=0
Dn Type=3
Dn Slope=0.005
Boundary for River Rch & Prof#=Stream0840,Reach-1,7
Up Type=0
Dn Type=3
Dn Slope=0.005

--- Stream0840.g01 (geometry) ---

Geom Title=Existing Conditions

River Reach=Stream0840,Reach-1
Reach XY= 30
      2470425.00     13573325.00      2470425.48     13573400.20
      2470421.37     13573423.50      2470381.09     13573472.81
      2470370.84     13573523.28      2470331.10     13573572.81
      2470316.84     13573631.05      2470228.62     13573726.50
      2470222.64     13573819.02      2470177.35     13573880.97
      2470172.65     13573969.03      2470127.35     13574030.97
      2470121.17     13574123.42      2470081.11     13574172.82
      2470068.89     13574227.18      2470028.83     13574276.58
      2470022.64     13574369.02      2469977.26     13574430.94
      2469974.48     13574759.78      2469969.25     13574777.33
      2469933.14     13574818.94      2469926.22     13574835.51
      2469925.36     13574995.15      2469921.25     13575023.45
      2469881.12     13575072.82      2469870.84     13575123.28
      2469831.10     13575172.81      2469822.50     13575218.97
      2469814.24     13575234.68      2469525.00     13575525.00

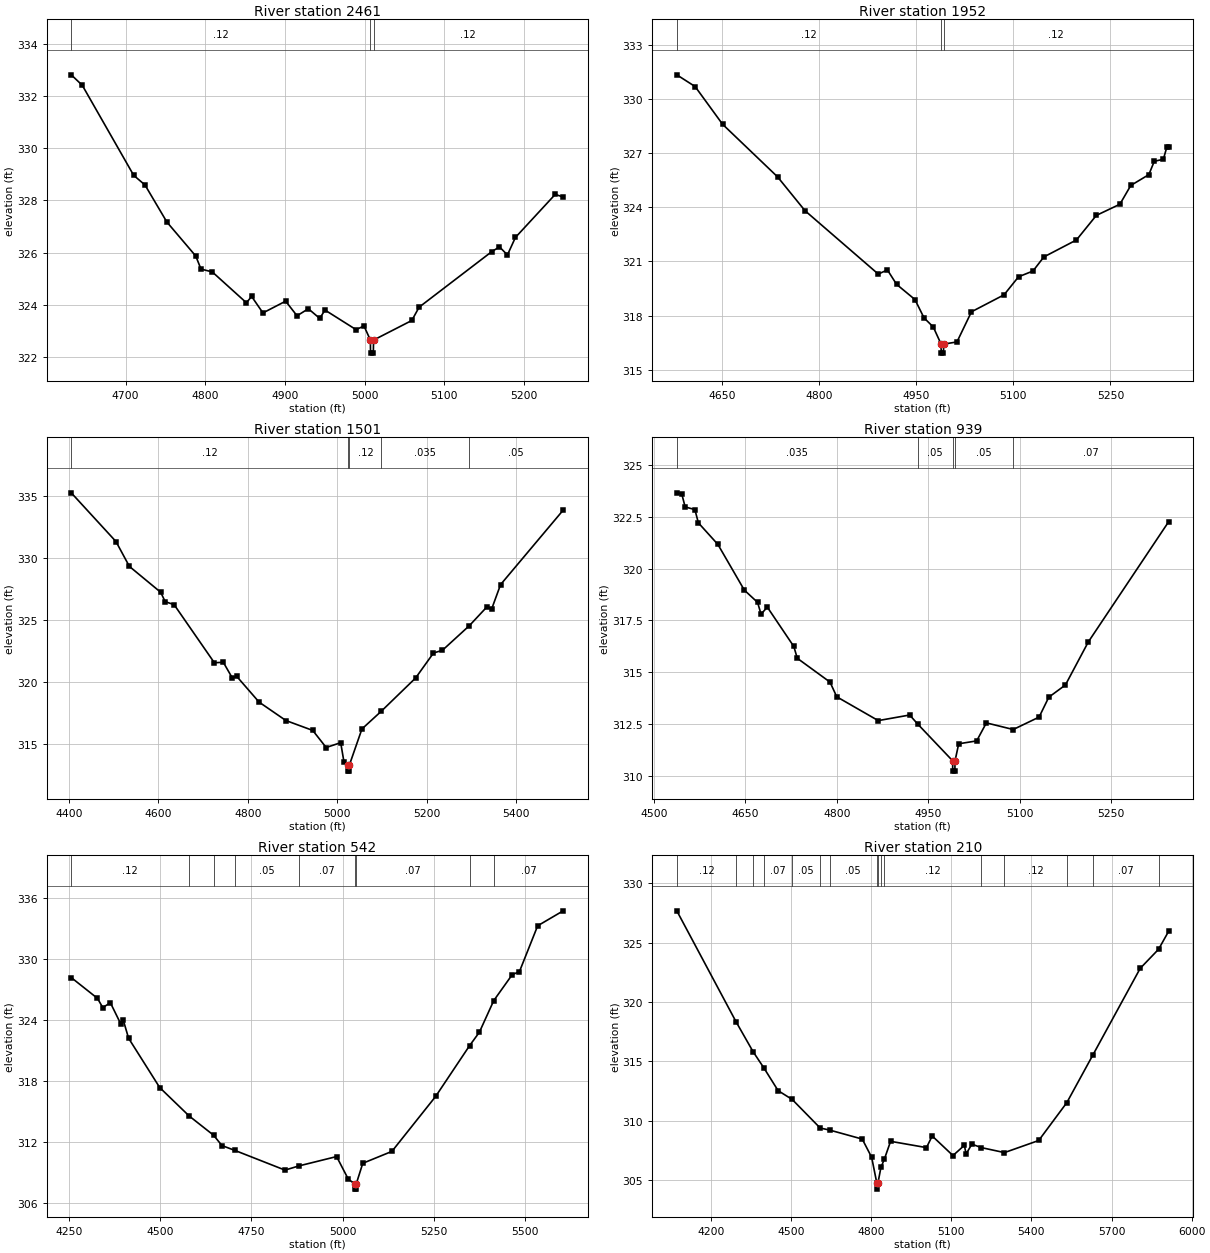
Type RM Length L Ch R = 1,2461,509,509,509
BEGIN DESCRIPTION:
Stream0840 5.0
END DESCRIPTION:
XS GIS Cut Line= 3
      2470174.98     13573124.97      2470398.96     13573382.81
      2470675.01     13573375.00
#Sta/Elev= 30
  4631.7  332.81  4645.5  332.41  4710.1  328.96  4724.3  328.59  4751.8  327.17
  4788.0  325.87  4794.6  325.37  4808.8  325.26  4851.6  324.08  4858.2  324.32
  4872.4  323.69  4900.9  324.14  4915.2  323.58  4929.4  323.85  4943.7  323.48
  4950.3  323.80  4989.3  323.05  4999.3  323.19  5007.3  322.65  5007.5  322.15
  5011.0  322.15  5011.3  322.65  5059.3  323.40  5068.5  323.91  5159.4  326.03
  5169.4  326.22  5179.4  325.91  5189.4  326.58  5239.4  328.23  5249.4  328.13
#Mann=3,-1,0
  4631.7    0.12       0  5007.3    0.05       0  5011.3    0.12       0
Bank Sta=5007.3,5011.3
Exp/Cntr=0.3,0.1

Type RM Length L Ch R = 1,1952,451,451,451
BEGIN DESCRIPTION:
Stream0840 4.0
END DESCRIPTION:
XS GIS Cut Line= 3
      2469925.02     13573525.02      2470225.00     13573825.00
      2470524.96     13573974.98
#Sta/Elev= 30
  4580.4  331.34  4608.7  330.69  4651.1  328.60  4735.9  325.69  4778.4  323.81
  4891.5  320.30  4905.6  320.53  4919.8  319.73  4948.1  318.89  4962.2  317.87
  4976.4  317.37  4988.5  316.42  4988.7  315.92  4992.2  315.92  4992.5  316.42
  5013.0  316.54  5035.4  318.21  5085.7  319.15  5108.1  320.15  5130.4  320.47
  5147.2  321.25  5197.5  322.19  5228.2  323.55  5264.6  324.17  5281.4  325.21
  5309.3  325.81  5317.7  326.55  5331.7  326.66  5337.3  327.36  5340.0  327.36
#Mann=3,-1,0
  4580.4    0.12       0  4988.5    0.05       0  4992.5    0.12       0
Bank Sta=4988.5,4992.5
Exp/Cntr=0.3,0.1

Type RM Length L Ch R = 1,1501,562,562,562
BEGIN DESCRIPTION:
Stream0840 3.0
END DESCRIPTION:
XS GIS Cut Line= 3
      2469474.96     13574225.00      2470075.00     13574225.00
      2470574.96     13574225.00
#Sta/Elev= 30
  4405.0  335.27  4505.0  331.33  4535.0  329.32  4605.0  327.23  4615.0  326.47
  4635.0  326.23  4725.0  321.53  4745.0  321.57  4765.0  320.31  4775.0  320.43
  4825.0  318.35  4885.0  316.86  4945.0  316.06  4975.0  314.68  5007.5  315.07
  5015.0  313.47  5023.0  313.27  5023.3  312.77  5026.8  312.77  5027.0  313.27
  5055.0  316.18  5098.5  317.62  5175.0  320.30  5215.0  322.32  5235.0  322.54
  5295.2  324.53  5335.0  326.07  5345.0  325.87  5365.0  327.85  5505.0  333.87
#Mann=5,-1,0
  4405.0    0.12       0  5023.0    0.05       0  5027.0    0.12       0
  5098.5   0.035       0  5295.2    0.05       0
Bank Sta=5023,5027
Exp/Cntr=0.3,0.1

Type RM Length L Ch R = 1,939,397,397,397
BEGIN DESCRIPTION:
Stream0840 2.0
END DESCRIPTION:
XS GIS Cut Line= 3
      2469675.01     13574425.02      2469805.21     13574658.85
      2470275.01     13574925.01
#Sta/Elev= 30
  4537.3  323.66  4545.3  323.62  4551.0  322.98  4567.0  322.85  4572.7  322.21
  4604.7  321.17  4648.2  318.96  4669.9  318.37  4675.6  317.80  4685.9  318.14
  4729.4  316.24  4735.1  315.67  4788.8  314.52  4799.9  313.81  4868.0  312.66
  4919.6  312.93  4932.9  312.49  4990.1  310.72  4990.3  310.22  4993.8  310.22
  4994.1  310.72  5000.1  311.54  5029.6  311.68  5045.5  312.55  5089.6  312.23
  5132.1  312.83  5148.0  313.79  5175.3  314.38  5212.9  316.46  5344.9  322.27
#Mann=5,-1,0
  4537.3   0.035       0  4932.9    0.05       0  4990.1    0.05       0
  4994.1    0.05       0  5089.6    0.07       0
Bank Sta=4990.1,4994.1
Exp/Cntr=0.3,0.1

Type RM Length L Ch R = 1,542,332,332,332
BEGIN DESCRIPTION:
Stream0840 1.0
END DESCRIPTION:
XS GIS Cut Line= 3
      2469424.97     13574524.96      2469875.00     13575125.00
      2470474.95     13575125.00
#Sta/Elev= 30
  4255.4  328.16  4327.3  326.12  4341.9  325.21  4362.7  325.69  4391.9  323.56
  4398.2  323.97  4412.7  322.20  4498.2  317.35  4578.9  314.56  4645.9  312.67
  4669.0  311.65  4704.8  311.17  4841.9  309.24  4881.1  309.66  4983.6  310.57
  5015.4  308.37  5033.4  307.87  5033.7  307.37  5037.2  307.37  5037.4  307.87
  5055.4  309.91  5135.4  311.08  5255.4  316.48  5348.5  321.47  5375.4  322.79
  5414.9  325.90  5465.4  328.44  5485.4  328.75  5535.4  333.25  5605.4  334.72
#Mann=9,-1,0
  4255.4    0.12       0  4578.9    0.05       0  4645.9   0.035       0
  4704.8    0.05       0  4881.1    0.07       0  5033.4    0.05       0
  5037.4    0.07       0  5348.5    0.12       0  5414.9    0.07       0
Bank Sta=5033.4,5037.4
Exp/Cntr=0.3,0.1

Type RM Length L Ch R = 1,210,0,0,0
BEGIN DESCRIPTION:
XS7819
END DESCRIPTION:
XS GIS Cut Line= 4
      2469273.95     13574565.09      2469487.50     13575205.73
      2469883.33     13575570.31      2470511.79     13575570.31
#Sta/Elev= 30
  4072.2  327.69  4294.5  318.32  4357.7  315.82  4399.3  314.41  4451.6  312.53
  4504.2  311.79  4609.1  309.38  4644.2  309.21  4766.5  308.45  4801.7  306.92
  4821.2  304.73  4821.5  304.23  4825.2  304.73  4836.5  306.06  4849.6  306.77
  4872.6  308.26  5007.0  307.73  5028.5  308.71  5106.2  307.06  5148.8  307.92
  5155.5  307.20  5177.1  308.02  5212.5  307.73  5299.1  307.31  5427.3  308.33
  5532.5  311.52  5630.9  315.57  5807.3  322.84  5876.1  324.45  5914.1  325.98
#Mann=16,-1,0
  4072.2    0.12       0  4294.5    0.07       0  4357.7    0.05       0
  4399.3    0.07       0  4504.2    0.05       0  4609.1   0.035       0
  4644.2    0.05       0  4821.2    0.05       0  4825.2    0.05       0
  4836.5    0.07       0  4849.6    0.12       0  5212.5    0.07       0
  5299.1    0.12       0  5532.5    0.05       0  5630.9    0.07       0
  5876.1    0.12       0
Bank Sta=4821.2,4825.2
Exp/Cntr=0.3,0.1

Chan Stop Cuts=-1