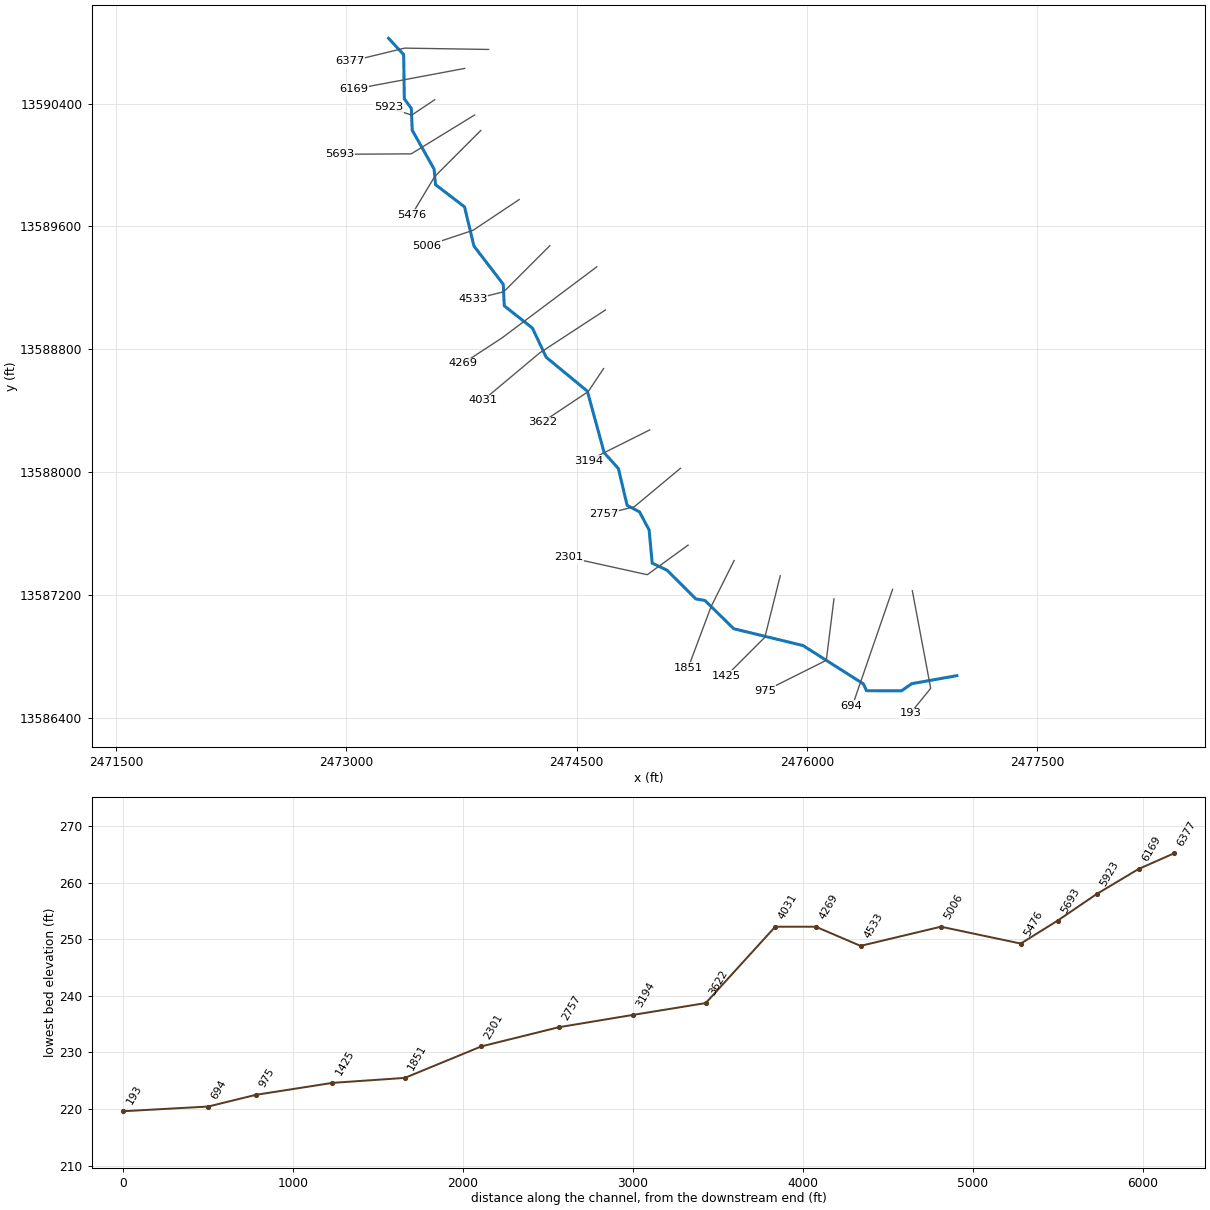
--- Stream0841.prj (project) ---

Proj Title=Stream0841 Base Level Engineering
Current Plan=p01
Default Exp/Contr=0.3,0.1
English Units
Geom File=g01
Flow File=f01
Plan File=p01
BEGIN DESCRIPTION:
Stream0841
END DESCRIPTION:

--- Stream0841.p01 (plan) ---

Plan Title=Multiple Run
Short Identifier=Multiple
Geom File=g01
Flow File=f01
Subcritical Flow
K Sum by GR= 0
Std Step Tol= 0.01
Critical Tol= 0.01
Num of Std Step Trials= 20
Max Error Tol= 0.3
Flow Tol Ratio= 0.001
Split Flow NTrial= 30
Split Flow Tol= 0.02
Split Flow Ratio= 0.02
Log Output Level= 0
Friction Slope Method= 1
Unsteady Friction Slope Method= 2
Unsteady Bridges Friction Slope Method= 1
Parabolic Critical Depth
Global Vel Dist=  1 , 1 , 1
Global Log Level= 0
CheckData=True
Encroach Param= -1, 0, 0, 0
BEGIN DESCRIPTION:
Multiple Run
END DESCRIPTION:

--- Stream0841.f01 (steady flow) ---

Flow Title=Multiple
Number of Profiles=7
Profile Names=10-year,25-year,50-year,1pct_min,100-year,1pct_plu,500-year
River Rch & RM= Stream0841,Reach-1,6377
     702    1145    1550    1017    2029    4049    3446
River Rch & RM= Stream0841,Reach-1,1851
    1111    1860    2563    1708    3408    6800    5973
Boundary for River Rch & Prof#=Stream0841,Reach-1,1
Up Type=0
Dn Type=3
Dn Slope=0.005
Boundary for River Rch & Prof#=Stream0841,Reach-1,2
Up Type=0
Dn Type=3
Dn Slope=0.005
Boundary for River Rch & Prof#=Stream0841,Reach-1,3
Up Type=0
Dn Type=3
Dn Slope=0.005
Boundary for River Rch & Prof#=Stream0841,Reach-1,4
Up Type=0
Dn Type=3
Dn Slope=0.005
Boundary for River Rch & Prof#=Stream0841,Reach-1,5
Up Type=0
Dn Type=3
Dn Slope=0.005
Boundary for River Rch & Prof#=Stream0841,Reach-1,6
Up Type=0
Dn Type=3
Dn Slope=0.005
Boundary for River Rch & Prof#=Stream0841,Reach-1,7
Up Type=0
Dn Type=3
Dn Slope=0.005

--- Stream0841.g01 (geometry) ---

Geom Title=Existing Conditions

River Reach=Stream0841,Reach-1
Reach XY= 30
      2473275.00     13590825.00      2473372.98     13590719.16
      2473377.26     13590430.94      2473422.73     13590369.06
      2473428.76     13590226.56      2473571.17     13589973.41
      2473580.42     13589872.33      2473769.48     13589727.44
      2473830.54     13589472.58      2474021.44     13589223.52
      2474028.08     13589083.31      2474211.38     13588938.22
      2474301.27     13588748.12      2474569.17     13588527.30
      2474678.62     13588126.50      2474771.38     13588023.50
      2474828.19     13587783.35      2474908.43     13587742.02
      2474971.25     13587623.45      2474991.27     13587407.86
      2475088.20     13587361.36      2475275.00     13587175.00
      2475334.79     13587164.48      2475522.57     13586980.52
      2475973.42     13586871.18      2476366.50     13586621.44
      2476386.97     13586576.96      2476614.50     13586576.22
      2476680.94     13586622.73      2476975.00     13586675.00

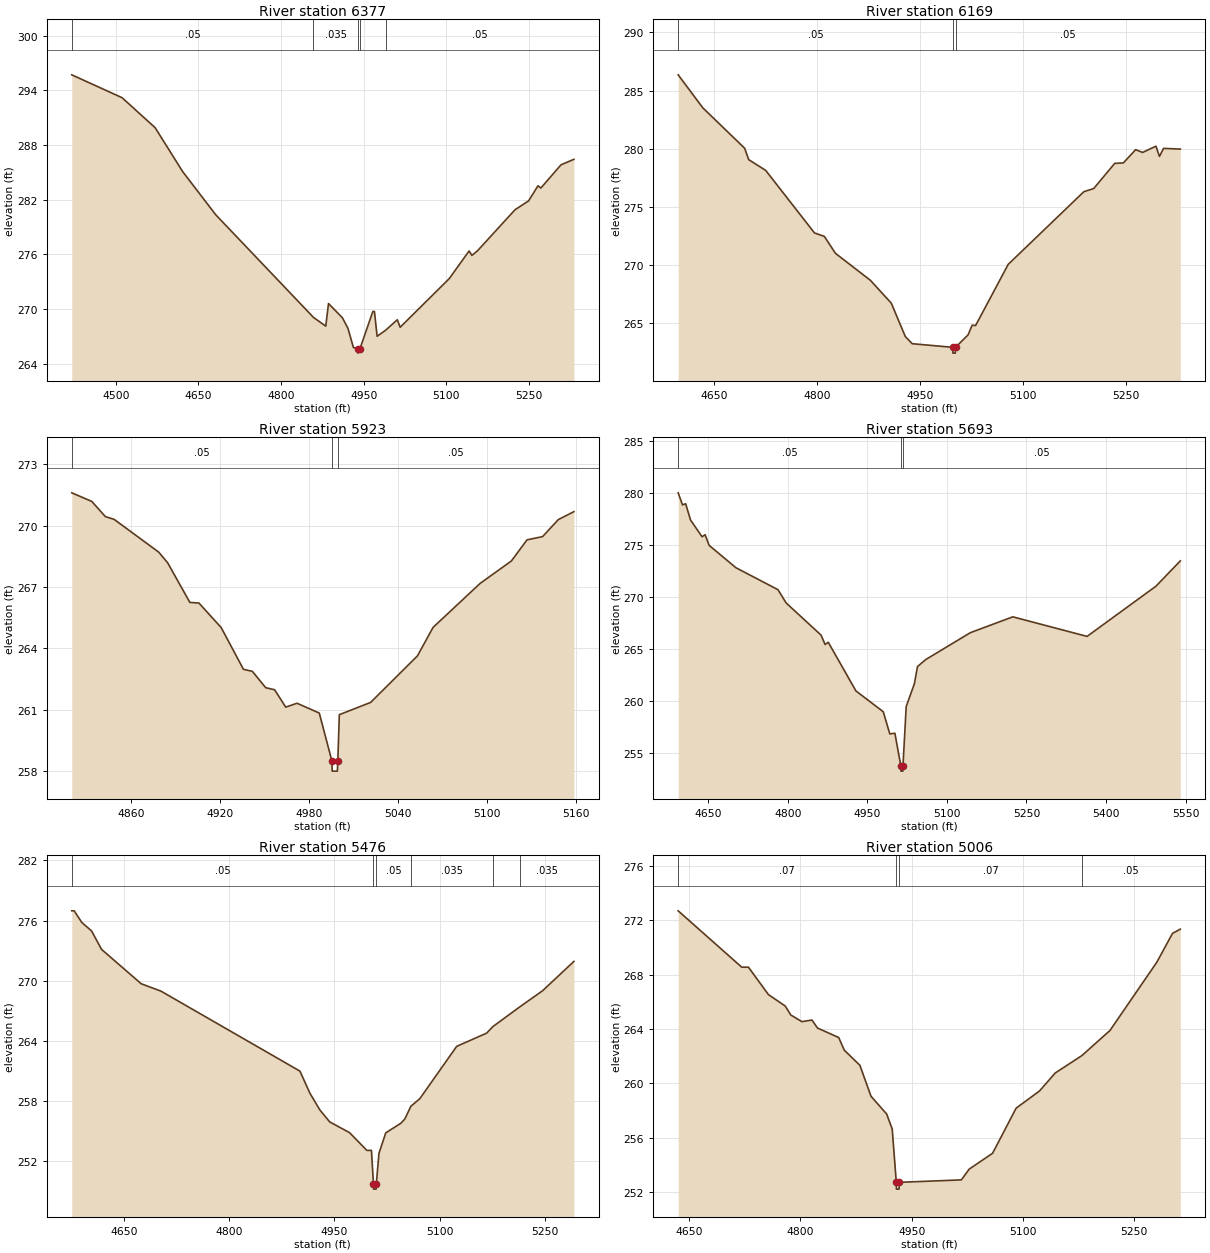
Type RM Length L Ch R = 1,6377,208,208,208
BEGIN DESCRIPTION:
Stream0841 13.0
END DESCRIPTION:
XS GIS Cut Line= 3
      2473926.38     13590752.60      2473379.51     13590761.28
      2473025.00     13590675.00
#Sta/Elev= 30
  4420.0  295.69  4511.4  293.18  4571.4  289.89  4621.4  285.07  4681.4  280.34
  4858.9  269.08  4881.2  268.12  4886.2  270.60  4911.4  269.04  4921.4  267.90
  4931.4  265.78  4939.4  265.66  4939.7  265.16  4943.4  265.66  4966.7  269.73
  4969.6  269.73  4974.5  267.01  4989.9  267.67  5011.1  268.82  5016.3  268.00
  5105.4  273.33  5141.5  276.37  5146.6  275.88  5156.8  276.39  5224.9  280.89
  5249.5  281.86  5266.6  283.52  5271.8  283.27  5308.4  285.82  5331.8  286.42
#Mann=5,-1,0
  4420.0    0.05       0  4858.9   0.035       0  4939.4    0.05       0
  4943.4   0.035       0  4989.9    0.05       0
Bank Sta=4939.4,4943.4
Exp/Cntr=0.3,0.1

Type RM Length L Ch R = 1,6169,246,246,246
BEGIN DESCRIPTION:
H21131
END DESCRIPTION:
XS GIS Cut Line= 2
      2473770.28     13590629.10      2473051.02     13590494.23
#Sta/Elev= 30
  4597.8  286.35  4633.7  283.51  4694.7  280.03  4700.6  279.05  4725.3  278.13
  4796.5  272.74  4810.8  272.45  4827.0  270.99  4877.9  268.67  4908.4  266.70
  4928.8  263.83  4938.9  263.21  4998.0  262.90  4998.2  262.40  5001.7  262.40
  5002.0  262.90  5020.3  263.97  5026.2  264.80  5031.3  264.78  5078.8  270.04
  5189.0  276.29  5203.5  276.57  5234.0  278.73  5246.6  278.77  5264.5  279.91
  5274.7  279.67  5294.1  280.21  5299.2  279.33  5305.2  280.02  5329.6  279.96
#Mann=3,-1,0
  4597.8    0.05       0  4998.0    0.05       0  5002.0    0.05       0
Bank Sta=4998,5002
Exp/Cntr=0.3,0.1

Type RM Length L Ch R = 1,5923,230,230,230
BEGIN DESCRIPTION:
Stream0841 12.0
END DESCRIPTION:
XS GIS Cut Line= 3
      2473575.02     13590425.01      2473425.00     13590325.00
      2473275.01     13590375.00
#Sta/Elev= 30
  4820.1  271.60  4833.6  271.18  4842.7  270.44  4848.7  270.30  4878.7  268.70
  4884.7  268.18  4899.7  266.24  4905.8  266.21  4920.8  265.01  4935.8  262.97
  4941.8  262.87  4950.8  262.07  4956.8  261.97  4964.3  261.12  4971.9  261.31
  4986.9  260.83  4995.4  258.49  4995.6  257.99  4999.1  257.99  4999.4  258.49
  5000.4  260.75  5021.5  261.35  5053.1  263.63  5063.6  265.02  5095.3  267.17
  5116.4  268.27  5126.9  269.30  5137.4  269.46  5148.0  270.29  5158.5  270.68
#Mann=3,-1,0
  4820.1    0.05       0  4995.4    0.05       0  4999.4    0.05       0
Bank Sta=4995.4,4999.4
Exp/Cntr=0.3,0.1

Type RM Length L Ch R = 1,5693,217,217,217
BEGIN DESCRIPTION:
H21130
END DESCRIPTION:
XS GIS Cut Line= 3
      2473834.84     13590325.65      2473421.89     13590072.82
      2472959.20     13590070.02
#Sta/Elev= 30
  4593.2  280.04  4601.4  278.88  4607.3  278.99  4616.5  277.43  4638.2  275.82
  4644.0  276.01  4651.6  274.99  4702.1  272.84  4781.4  270.73  4796.9  269.45
  4862.7  266.36  4870.3  265.46  4876.2  265.68  4928.4  261.00  4979.9  259.00
  4992.3  256.87  5001.9  256.93  5013.1  253.79  5013.4  253.29  5016.9  253.29
  5017.1  253.79  5023.2  259.50  5038.6  261.68  5044.5  263.34  5059.9  264.01
  5144.3  266.60  5224.3  268.12  5364.3  266.24  5494.3  271.07  5540.1  273.50
#Mann=3,-1,0
  4593.2    0.05       0  5013.1    0.05       0  5017.1    0.05       0
Bank Sta=5013.1,5017.1
Exp/Cntr=0.3,0.1

Type RM Length L Ch R = 1,5476,470,470,470
BEGIN DESCRIPTION:
Stream0841 11.0
END DESCRIPTION:
XS GIS Cut Line= 3
      2473875.01     13590225.01      2473575.00     13589925.00
      2473425.01     13589675.02
#Sta/Elev= 30
  4575.6  276.97  4579.1  276.97  4589.8  275.82  4603.9  274.96  4618.0  273.13
  4674.6  269.70  4702.9  268.96  4900.9  260.99  4915.0  258.80  4929.2  257.13
  4943.3  255.93  4971.6  254.86  4996.3  253.09  5002.8  253.09  5005.7  249.73
  5005.9  249.23  5009.4  249.23  5009.7  249.73  5013.5  252.80  5023.2  254.84
  5044.6  255.79  5050.4  256.22  5059.0  257.49  5071.8  258.25  5124.3  263.46
  5167.0  264.78  5175.9  265.43  5213.9  267.38  5246.7  269.00  5291.4  271.93
#Mann=6,-1,0
  4575.6    0.05       0  5005.7    0.05       0  5009.7    0.05       0
  5059.0   0.035       0  5175.9    0.05       0  5213.9   0.035       0
Bank Sta=5005.7,5009.7
Exp/Cntr=0.3,0.1

Type RM Length L Ch R = 1,5006,473,473,473
BEGIN DESCRIPTION:
Stream0841 10.0
END DESCRIPTION:
XS GIS Cut Line= 3
      2474125.03     13589775.02      2473825.00     13589575.00
      2473525.02     13589475.01
#Sta/Elev= 30
  4635.2  272.70  4720.9  268.55  4729.9  268.55  4756.9  266.53  4779.5  265.69
  4787.0  265.03  4802.0  264.54  4815.5  264.66  4823.0  264.07  4851.6  263.37
  4859.1  262.44  4880.1  261.33  4895.1  259.05  4916.2  257.74  4923.7  256.64
  4929.2  252.71  4929.4  252.21  4932.9  252.21  4933.2  252.71  5016.9  252.89
  5027.4  253.68  5059.0  254.85  5090.7  258.17  5122.3  259.44  5143.4  260.76
  5179.3  262.04  5217.2  263.89  5280.4  268.92  5301.5  271.04  5312.0  271.35
#Mann=4,-1,0
  4635.2    0.07       0  4929.2    0.05       0  4933.2    0.07       0
  5179.3    0.05       0
Bank Sta=4929.2,4933.2
Exp/Cntr=0.3,0.1

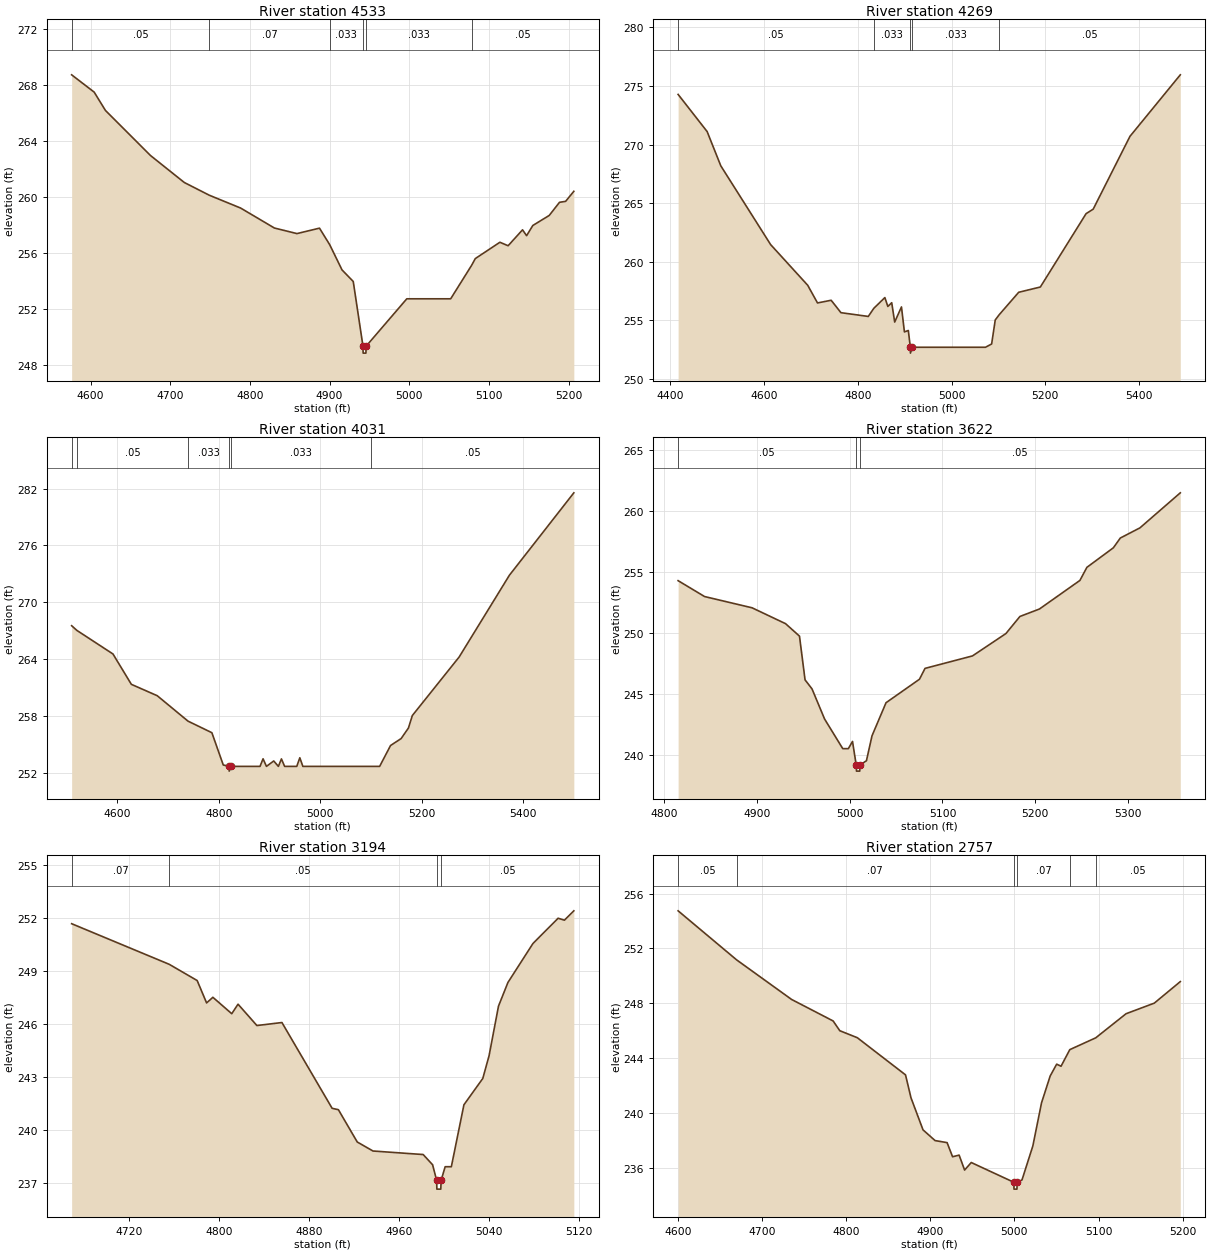
Type RM Length L Ch R = 1,4533,264,264,264
BEGIN DESCRIPTION:
Stream0841 9.0
END DESCRIPTION:
XS GIS Cut Line= 3
      2474324.99     13589474.99      2474025.00     13589175.00
      2473825.00     13589125.00
#Sta/Elev= 30
  4576.2  268.75  4604.5  267.51  4618.6  266.20  4675.2  262.97  4717.6  261.04
  4748.9  260.13  4788.3  259.21  4830.7  257.78  4859.0  257.38  4887.3  257.77
  4900.2  256.58  4915.6  254.78  4929.7  253.95  4941.9  249.32  4942.1  248.82
  4945.6  248.82  4945.9  249.32  4996.9  252.71  5052.0  252.71  5078.2  255.10
  5082.9  255.59  5113.8  256.76  5124.1  256.51  5142.2  257.65  5147.3  257.23
  5155.1  257.96  5175.7  258.68  5188.6  259.62  5196.3  259.69  5206.6  260.41
#Mann=6,-1,0
  4576.2    0.05       0  4748.9    0.07       0  4900.2   0.033       0
  4941.9   0.033       0  4945.9   0.033       0  5078.2    0.05       0
Bank Sta=4941.9,4945.9
Exp/Cntr=0.3,0.1

Type RM Length L Ch R = 1,4269,238,238,238
BEGIN DESCRIPTION:
H21129
END DESCRIPTION:
XS GIS Cut Line= 3
      2474629.96     13589336.76      2474011.87     13588873.20
      2473761.80     13588710.23
#Sta/Elev= 30
  4416.8  274.28  4478.7  271.11  4507.8  268.19  4614.1  261.47  4693.2  258.00
  4714.1  256.49  4743.2  256.72  4764.1  255.66  4822.4  255.34  4834.4  256.04
  4857.8  256.95  4864.1  256.19  4872.4  256.51  4878.7  254.86  4893.2  256.15
  4899.5  254.02  4907.8  254.14  4912.1  252.71  4912.3  252.21  4916.1  252.71
  5072.4  252.71  5085.5  252.99  5093.2  255.04  5101.5  255.48  5143.2  257.40
  5189.4  257.85  5287.0  264.11  5302.1  264.49  5380.5  270.70  5487.9  275.95
#Mann=5,-1,0
  4416.8    0.05       0  4834.4   0.033       0  4912.1   0.033       0
  4916.1   0.033       0  5101.5    0.05       0
Bank Sta=4912.1,4916.1
Exp/Cntr=0.3,0.1

Type RM Length L Ch R = 1,4031,409,409,409
BEGIN DESCRIPTION:
Stream0841 8.0
END DESCRIPTION:
XS GIS Cut Line= 3
      2474686.17     13589055.83      2474256.30     13588774.86
      2473891.89     13588469.32
#Sta/Elev= 30
  4510.2  267.54  4520.4  267.05  4591.6  264.56  4627.8  261.36  4678.8  260.16
  4739.4  257.48  4786.4  256.26  4808.8  252.86  4820.2  252.71  4820.5  252.21
  4824.2  252.71  4881.2  252.71  4887.2  253.51  4893.9  252.71  4908.2  253.28
  4917.4  252.71  4923.4  253.50  4929.7  252.71  4953.6  252.71  4959.6  253.62
  4965.6  252.71  5100.4  252.71  5116.8  252.71  5138.3  254.91  5159.1  255.64
  5173.5  256.75  5181.2  258.07  5273.4  264.24  5372.5  272.87  5499.3  281.55
#Mann=6,-1,0
  4510.2    0.07       0  4520.4    0.05       0  4739.4   0.033       0
  4820.2   0.033       0  4824.2   0.033       0  5100.4    0.05       0
Bank Sta=4820.2,4824.2
Exp/Cntr=0.3,0.1

Type RM Length L Ch R = 1,3622,428,428,428
BEGIN DESCRIPTION:
Stream0841 7.0
END DESCRIPTION:
XS GIS Cut Line= 3
      2474675.00     13588675.00      2474575.00     13588525.00
      2474275.03     13588325.02
#Sta/Elev= 30
  4815.3  254.31  4843.8  253.01  4894.9  252.09  4931.0  250.79  4946.0  249.77
  4952.0  246.19  4959.5  245.45  4973.0  242.99  4992.6  240.56  4998.6  240.56
  5003.1  241.15  5007.1  239.22  5007.4  238.72  5010.9  238.72  5011.1  239.22
  5018.1  239.57  5024.1  241.61  5039.2  244.32  5075.2  246.24  5081.2  247.13
  5132.3  248.15  5168.3  249.98  5183.4  251.38  5204.4  251.99  5248.0  254.33
  5255.5  255.40  5284.0  257.00  5291.5  257.80  5312.6  258.63  5356.1  261.50
#Mann=3,-1,0
  4815.3    0.05       0  5007.1    0.05       0  5011.1    0.05       0
Bank Sta=5007.1,5011.1
Exp/Cntr=0.3,0.1

Type RM Length L Ch R = 1,3194,437,437,437
BEGIN DESCRIPTION:
Stream0841 6.0
END DESCRIPTION:
XS GIS Cut Line= 3
      2474975.04     13588275.02      2474675.00     13588125.00
      2474574.96     13588074.98
#Sta/Elev= 30
  4668.5  251.67  4755.4  249.37  4780.3  248.45  4788.7  247.18  4794.3  247.50
  4811.1  246.57  4816.7  247.11  4833.5  245.90  4855.8  246.07  4900.5  241.21
  4906.1  241.13  4922.9  239.30  4936.9  238.79  4981.6  238.59  4990.0  238.01
  4993.6  237.13  4993.8  236.63  4997.3  236.63  4997.6  237.13  5001.2  237.90
  5006.7  237.90  5017.9  241.41  5034.7  242.90  5040.3  244.19  5048.7  247.00
  5057.1  248.34  5079.4  250.55  5101.8  251.98  5107.4  251.87  5115.8  252.40
#Mann=4,-1,0
  4668.5    0.07       0  4755.4    0.05       0  4993.6    0.05       0
  4997.6    0.05       0
Bank Sta=4993.6,4997.6
Exp/Cntr=0.3,0.1

Type RM Length L Ch R = 1,2757,456,456,456
BEGIN DESCRIPTION:
Stream0841 5.0
END DESCRIPTION:
XS GIS Cut Line= 3
      2475175.04     13588025.03      2474875.00     13587775.00
      2474675.02     13587725.00
#Sta/Elev= 30
  4600.5  254.74  4669.9  251.17  4735.3  248.28  4784.7  246.71  4792.6  246.00
  4813.4  245.49  4870.7  242.78  4877.2  241.11  4891.5  238.77  4905.8  237.99
  4920.1  237.84  4926.6  236.81  4934.4  236.93  4940.9  235.84  4948.8  236.39
  4999.4  234.95  4999.6  234.45  5003.1  234.45  5003.4  234.95  5009.1  235.12
  5022.0  237.60  5032.3  240.74  5042.6  242.70  5050.3  243.56  5055.5  243.41
  5065.9  244.62  5096.7  245.48  5132.8  247.24  5166.3  248.01  5197.2  249.58
#Mann=6,-1,0
  4600.5    0.05       0  4669.9    0.07       0  4999.4    0.05       0
  5003.4    0.07       0  5065.9    0.07       0  5096.7    0.05       0
Bank Sta=4999.4,5003.4
Exp/Cntr=0.3,0.1

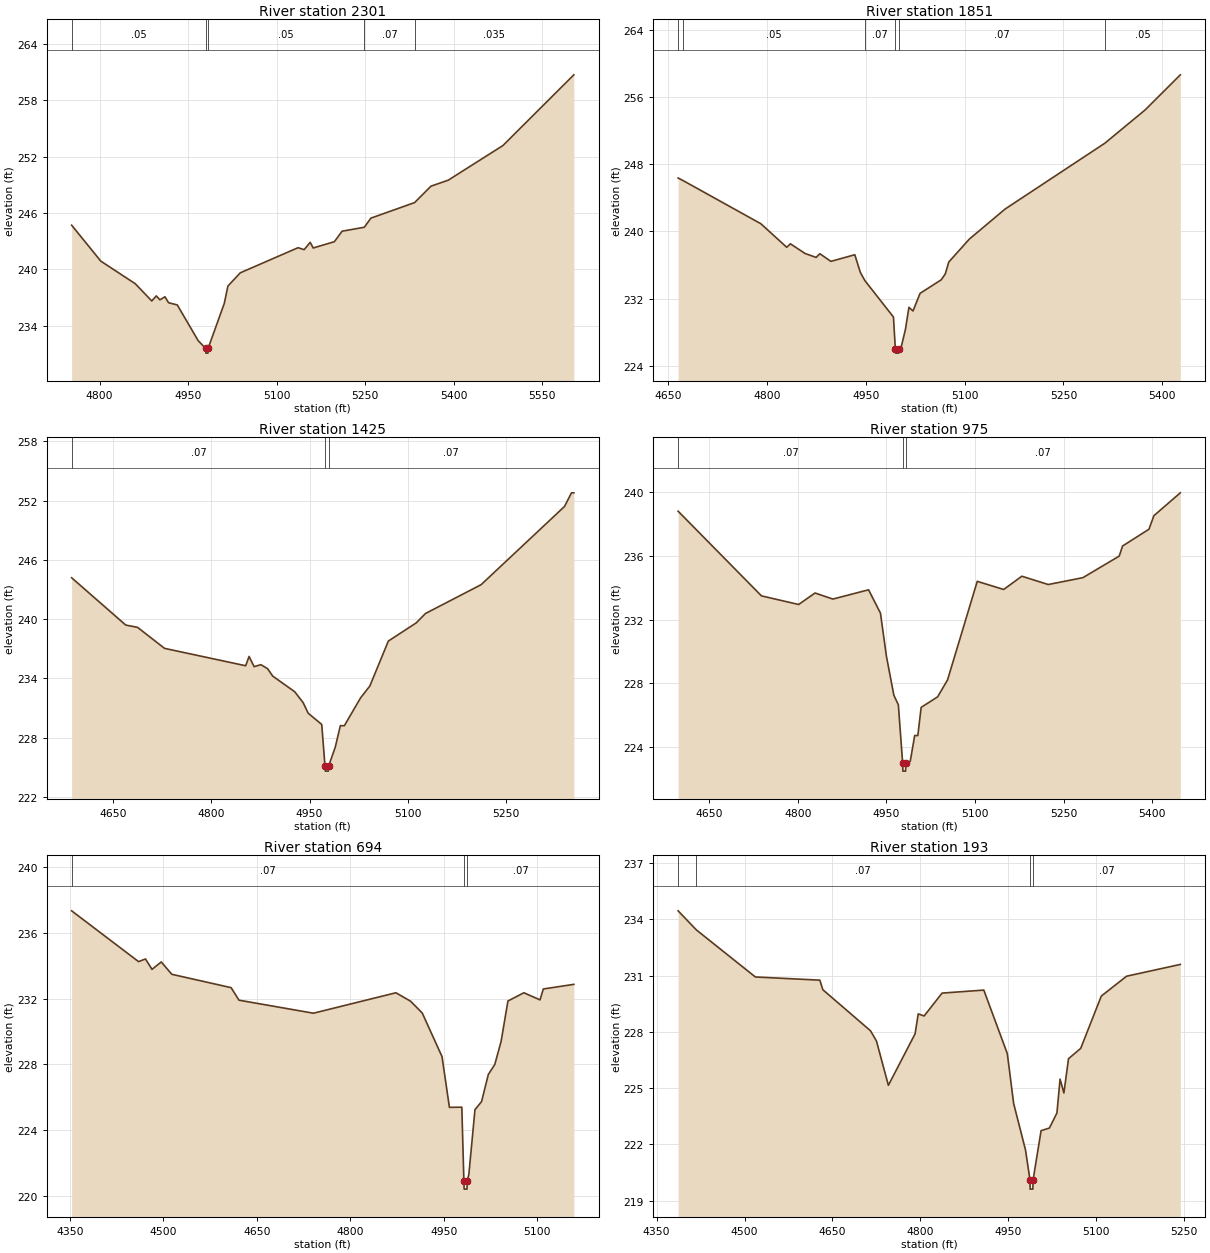
Type RM Length L Ch R = 1,2301,450,450,450
BEGIN DESCRIPTION:
Stream0841 4.0
END DESCRIPTION:
XS GIS Cut Line= 3
      2475224.97     13587524.98      2474959.38     13587332.47
      2474448.66     13587445.00
#Sta/Elev= 30
  4752.5  244.70  4801.9  240.87  4860.3  238.46  4888.3  236.62  4895.9  237.16
  4902.1  236.74  4910.6  237.07  4916.8  236.43  4931.5  236.20  4967.0  232.38
  4979.7  231.56  4980.0  231.06  4983.5  231.06  4983.7  231.56  5011.1  236.35
  5017.3  238.21  5038.2  239.62  5136.2  242.30  5146.5  242.09  5156.7  242.87
  5161.9  242.27  5197.7  242.94  5210.8  244.06  5248.5  244.48  5259.6  245.45
  5333.7  247.11  5361.5  248.86  5390.7  249.50  5483.3  253.19  5603.5  260.73
#Mann=5,-1,0
  4752.5    0.05       0  4979.7    0.05       0  4983.7    0.05       0
  5248.5    0.07       0  5333.7   0.035       0
Bank Sta=4979.7,4983.7
Exp/Cntr=0.3,0.1

Type RM Length L Ch R = 1,1851,426,426,426
BEGIN DESCRIPTION:
Stream0841 3.0
END DESCRIPTION:
XS GIS Cut Line= 3
      2475524.99     13587424.97      2475375.00     13587125.00
      2475224.99     13586724.98
#Sta/Elev= 30
  4664.8  246.36  4672.9  246.03  4790.5  240.91  4829.7  238.11  4835.3  238.52
  4857.6  237.37  4874.4  236.90  4880.0  237.34  4896.8  236.43  4933.1  237.22
  4941.5  235.12  4948.4  234.14  4991.8  229.80  4994.7  226.00  4995.1  225.50
  4999.6  225.50  5000.1  226.00  5002.9  226.00  5010.0  228.33  5015.3  230.96
  5021.5  230.52  5032.2  232.62  5064.3  234.23  5070.5  234.93  5075.8  236.35
  5107.0  239.08  5161.3  242.66  5312.9  250.51  5374.0  254.47  5427.4  258.65
#Mann=6,-1,0
  4664.8    0.07       0  4672.9    0.05       0  4948.4    0.07       0
  4994.7    0.05       0  5000.1    0.07       0  5312.9    0.05       0
Bank Sta=4994.7,5000.1
Exp/Cntr=0.3,0.1

Type RM Length L Ch R = 1,1425,450,450,450
BEGIN DESCRIPTION:
Stream0841 2.0
END DESCRIPTION:
XS GIS Cut Line= 3
      2475825.00     13587325.02      2475725.00     13586925.00
      2475474.99     13586674.99
#Sta/Elev= 30
  4587.2  244.20  4669.7  239.41  4687.7  239.18  4728.9  237.05  4852.6  235.29
  4857.8  236.23  4865.5  235.20  4875.8  235.40  4886.1  234.99  4893.9  234.24
  4927.4  232.66  4940.3  231.55  4948.0  230.48  4968.6  229.35  4973.6  225.12
  4974.1  224.62  4978.6  224.62  4979.0  225.12  4989.2  227.03  4997.0  229.22
  5003.1  229.22  5027.8  232.03  5042.0  233.24  5070.2  237.79  5112.7  239.63
  5126.8  240.58  5211.7  243.50  5338.9  251.42  5349.5  252.80  5353.1  252.80
#Mann=3,-1,0
  4587.2    0.07       0  4973.6    0.05       0  4979.0    0.07       0
Bank Sta=4973.6,4979
Exp/Cntr=0.3,0.1

Type RM Length L Ch R = 1,975,281,281,281
BEGIN DESCRIPTION:
Stream0841 1.0
END DESCRIPTION:
XS GIS Cut Line= 3
      2476175.00     13587174.99      2476125.00     13586775.00
      2475725.02     13586575.01
#Sta/Elev= 30
  4597.2  238.78  4738.3  233.48  4801.3  232.94  4829.0  233.66  4859.2  233.28
  4919.7  233.86  4939.8  232.40  4949.9  229.70  4962.5  227.26  4970.1  226.66
  4977.4  223.01  4977.8  222.51  4982.4  222.51  4982.8  223.01  4990.2  223.12
  4997.8  224.74  5003.1  224.74  5008.7  226.50  5036.6  227.16  5053.4  228.22
  5103.7  234.39  5148.4  233.88  5179.2  234.71  5223.9  234.19  5282.6  234.62
  5344.1  235.97  5349.7  236.60  5394.4  237.65  5402.8  238.50  5447.5  239.93
#Mann=3,-1,0
  4597.2    0.07       0  4977.4    0.05       0  4982.8    0.07       0
Bank Sta=4977.4,4982.8
Exp/Cntr=0.3,0.1

Type RM Length L Ch R = 1,694,501,501,501
BEGIN DESCRIPTION:
XS7820
END DESCRIPTION:
XS GIS Cut Line= 3
      2476556.59     13587236.97      2476304.86     13586507.81
      2476284.18     13586479.93
#Sta/Elev= 30
  4352.7  237.32  4460.1  234.24  4471.2  234.40  4481.7  233.77  4496.5  234.22
  4513.5  233.47  4608.7  232.66  4621.3  231.90  4740.8  231.11  4873.2  232.35
  4896.7  231.84  4915.5  231.12  4947.2  228.48  4959.1  225.40  4979.0  225.41
  4982.3  220.94  4982.7  220.44  4987.3  220.44  4987.7  220.94  4990.3  221.34
  5000.1  225.26  5010.7  225.75  5021.5  227.39  5031.9  228.00  5042.1  229.41
  5053.0  231.85  5078.6  232.35  5104.5  231.92  5109.8  232.58  5158.8  232.86
#Mann=3,-1,0
  4352.7    0.07       0  4982.3    0.05       0  4987.7    0.07       0
Bank Sta=4982.3,4987.7
Exp/Cntr=0.3,0.1

Type RM Length L Ch R = 1,193,0,0,0
BEGIN DESCRIPTION:
H21128
END DESCRIPTION:
XS GIS Cut Line= 3
      2476685.21     13587227.49      2476804.82     13586592.46
      2476671.62     13586429.46
#Sta/Elev= 30
  4386.7  234.46  4417.9  233.44  4518.5  230.93  4628.5  230.76  4633.6  230.25
  4714.9  228.06  4725.0  227.52  4745.4  225.15  4791.0  227.90  4796.3  228.96
  4806.4  228.85  4837.0  230.07  4908.2  230.23  4948.3  226.84  4959.1  224.18
  4979.4  221.69  4986.9  220.11  4987.3  219.61  4991.9  219.61  4992.3  220.11
  5005.9  222.73  5020.1  222.87  5032.9  223.67  5038.3  225.48  5044.8  224.74
  5052.7  226.57  5073.5  227.12  5108.6  229.91  5151.7  230.97  5243.4  231.60
#Mann=4,-1,0
  4386.7    0.05       0  4417.9    0.07       0  4986.9    0.05       0
  4992.3    0.07       0
Bank Sta=4986.9,4992.3
Exp/Cntr=0.3,0.1

Chan Stop Cuts=-1