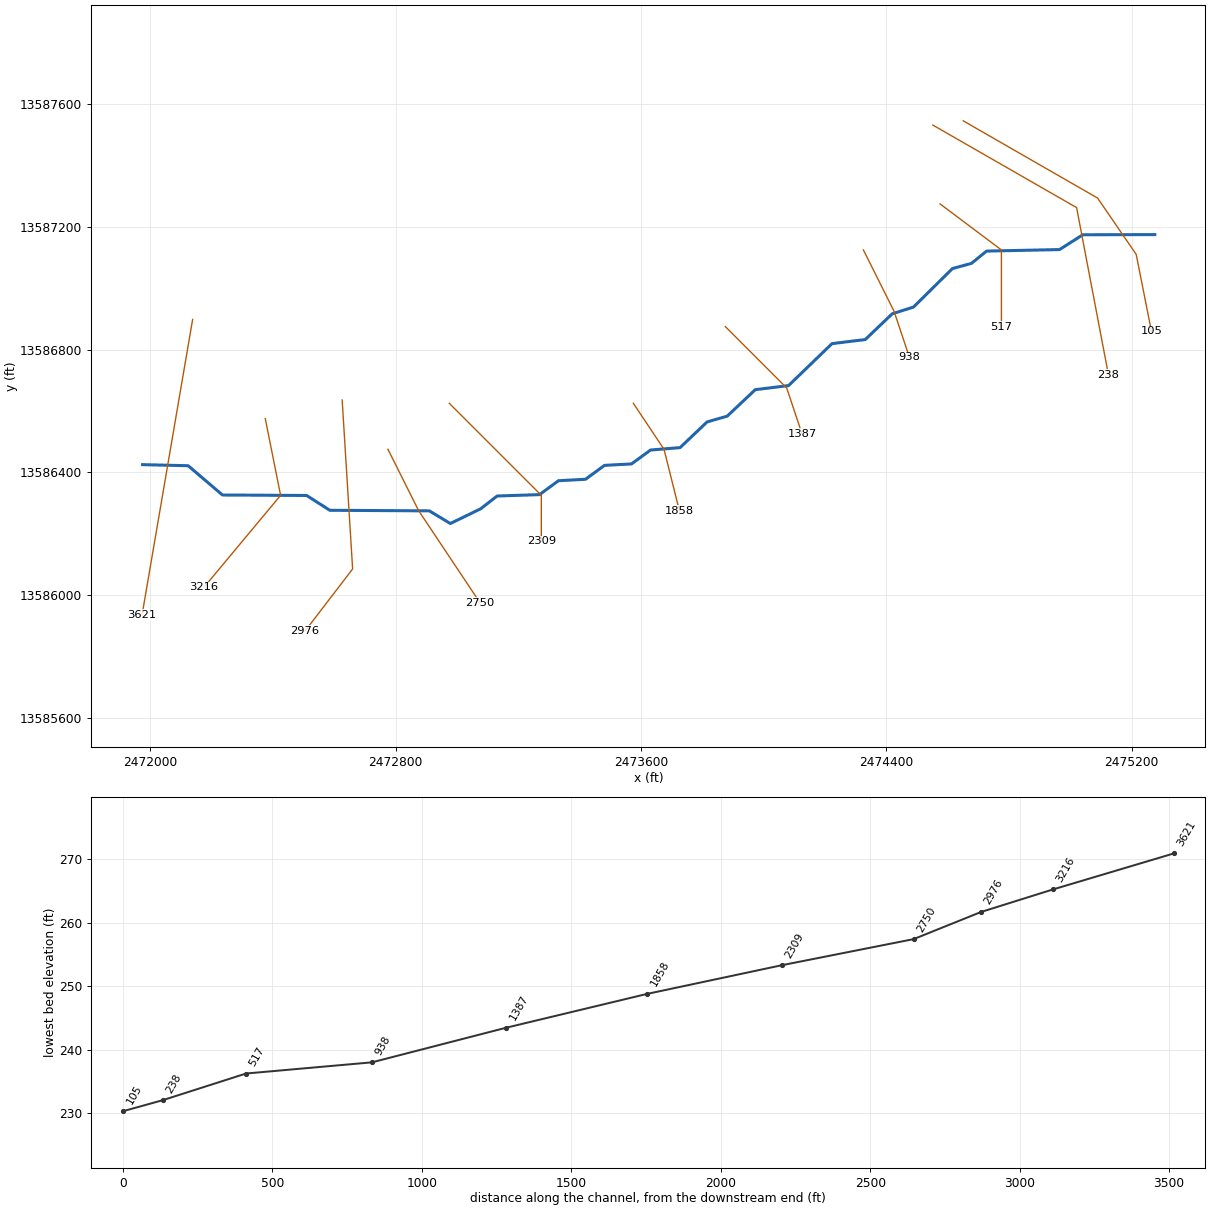
--- Stream0842.prj (project) ---

Proj Title=Stream0842 Base Level Engineering
Current Plan=p01
Default Exp/Contr=0.3,0.1
English Units
Geom File=g01
Flow File=f01
Plan File=p01
BEGIN DESCRIPTION:
Stream0842
END DESCRIPTION:

--- Stream0842.p01 (plan) ---

Plan Title=Multiple Run
Short Identifier=Multiple
Geom File=g01
Flow File=f01
Subcritical Flow
K Sum by GR= 0
Std Step Tol= 0.01
Critical Tol= 0.01
Num of Std Step Trials= 20
Max Error Tol= 0.3
Flow Tol Ratio= 0.001
Split Flow NTrial= 30
Split Flow Tol= 0.02
Split Flow Ratio= 0.02
Log Output Level= 0
Friction Slope Method= 1
Unsteady Friction Slope Method= 2
Unsteady Bridges Friction Slope Method= 1
Parabolic Critical Depth
Global Vel Dist=  1 , 1 , 1
Global Log Level= 0
CheckData=True
Encroach Param= -1, 0, 0, 0
BEGIN DESCRIPTION:
Multiple Run
END DESCRIPTION:

--- Stream0842.f01 (steady flow) ---

Flow Title=Multiple
Number of Profiles=7
Profile Names=10-year,25-year,50-year,1pct_min,100-year,1pct_plu,500-year
River Rch & RM= Stream0842,Reach-1,3621
     551     883    1181     767    1529    3052    2537
River Rch & RM= Stream0842,Reach-1,105
    1111    1860    2563    1708    3408    6800    5973
Boundary for River Rch & Prof#=Stream0842,Reach-1,1
Up Type=0
Dn Type=3
Dn Slope=0.005
Boundary for River Rch & Prof#=Stream0842,Reach-1,2
Up Type=0
Dn Type=3
Dn Slope=0.005
Boundary for River Rch & Prof#=Stream0842,Reach-1,3
Up Type=0
Dn Type=3
Dn Slope=0.005
Boundary for River Rch & Prof#=Stream0842,Reach-1,4
Up Type=0
Dn Type=3
Dn Slope=0.005
Boundary for River Rch & Prof#=Stream0842,Reach-1,5
Up Type=0
Dn Type=3
Dn Slope=0.005
Boundary for River Rch & Prof#=Stream0842,Reach-1,6
Up Type=0
Dn Type=3
Dn Slope=0.005
Boundary for River Rch & Prof#=Stream0842,Reach-1,7
Up Type=0
Dn Type=3
Dn Slope=0.005

--- Stream0842.g01 (geometry) ---

Geom Title=Existing Conditions

River Reach=Stream0842,Reach-1
Reach XY= 30
      2471975.00     13586425.00      2472123.55     13586421.49
      2472235.44     13586326.06      2472509.78     13586324.48
      2472585.50     13586276.22      2472909.84     13586274.34
      2472978.32     13586233.04      2473077.17     13586281.09
      2473130.93     13586322.75      2473269.06     13586327.27
      2473330.98     13586372.64      2473419.03     13586377.35
      2473480.97     13586422.65      2473569.03     13586427.35
      2473630.98     13586472.64      2473727.42     13586480.54
      2473815.33     13586564.20      2473881.04     13586583.18
      2473972.58     13586669.46      2474081.17     13586682.86
      2474222.57     13586819.48      2474331.16     13586832.88
      2474418.96     13586916.82      2474488.21     13586938.63
      2474615.32     13587064.24      2474677.17     13587081.14
      2474726.55     13587121.25      2474964.50     13587126.22
      2475040.22     13587174.48      2475275.00     13587175.00

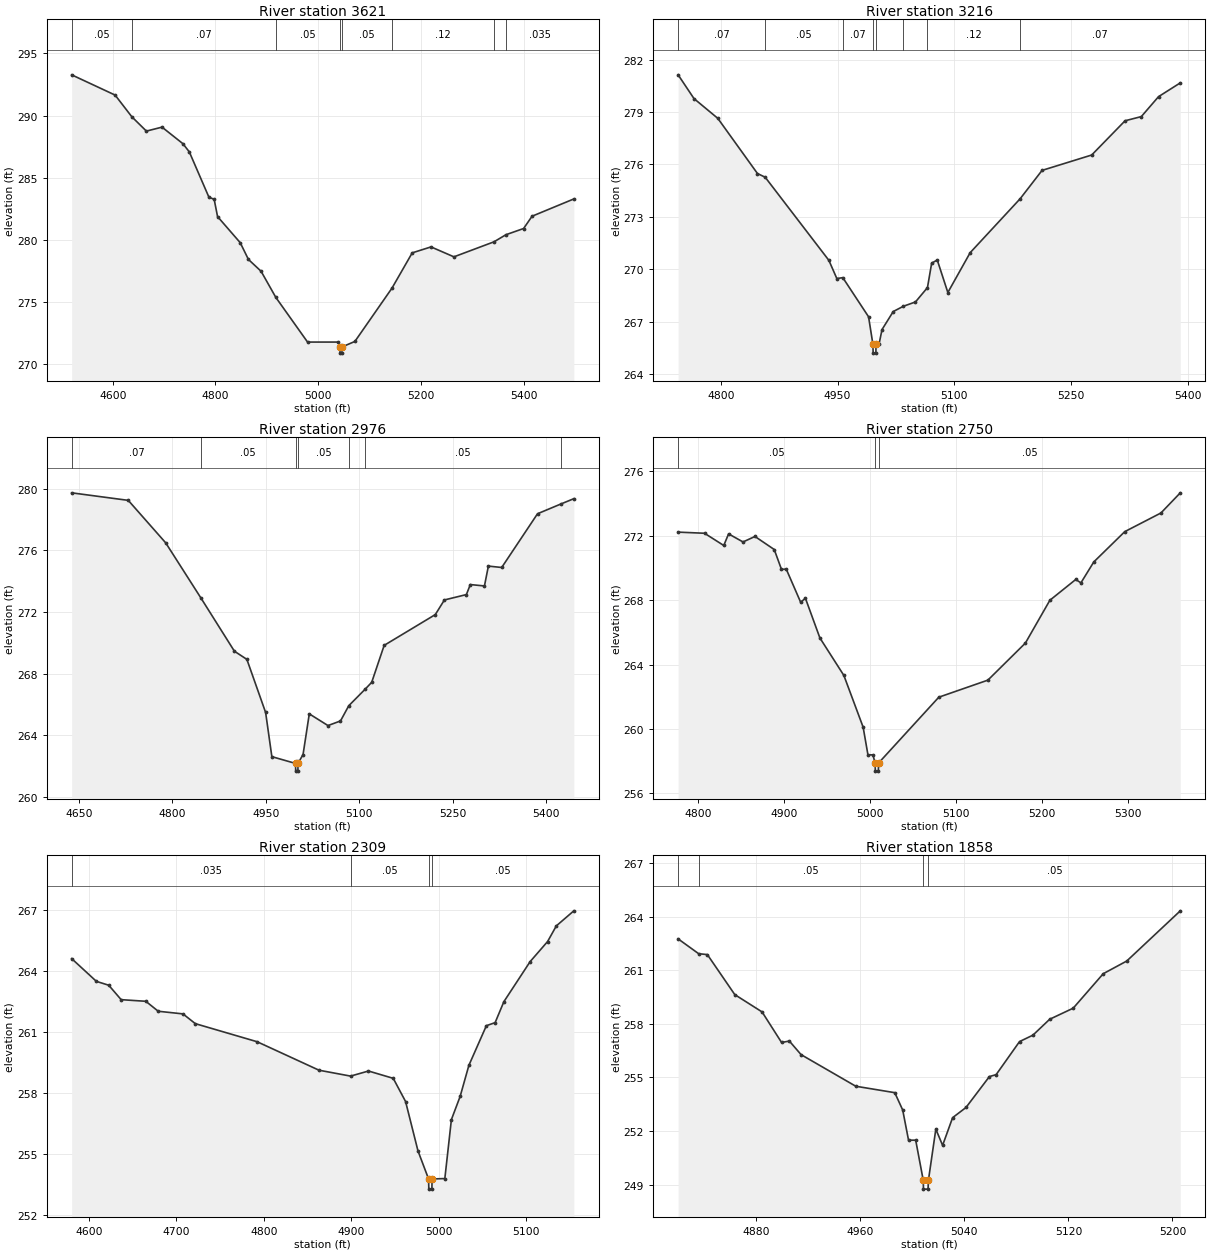
Type RM Length L Ch R = 1,3621,405,405,405
BEGIN DESCRIPTION:
XS7822
END DESCRIPTION:
XS GIS Cut Line= 2
      2472138.19     13586898.39      2471973.27     13585934.90
#Sta/Elev= 30
  4520.1  293.28  4604.7  291.65  4637.3  289.90  4665.6  288.75  4696.0  289.07
  4736.6  287.74  4749.1  287.08  4787.3  283.43  4797.5  283.26  4804.1  281.87
  4848.2  279.77  4864.2  278.42  4888.8  277.47  4917.6  275.36  4979.3  271.77
  5039.3  271.77  5042.4  271.38  5042.7  270.88  5046.2  270.88  5046.4  271.38
  5071.4  271.82  5143.6  276.11  5183.0  278.95  5219.6  279.43  5264.2  278.63
  5342.2  279.84  5365.4  280.41  5399.8  280.91  5416.3  281.90  5497.6  283.29
#Mann=8,-1,0
  4520.1    0.05       0  4637.3    0.07       0  4917.6    0.05       0
  5042.4    0.05       0  5046.4    0.05       0  5143.6    0.12       0
  5342.2    0.07       0  5365.4   0.035       0
Bank Sta=5042.4,5046.4
Exp/Cntr=0.3,0.1

Type RM Length L Ch R = 1,3216,240,240,240
BEGIN DESCRIPTION:
Stream0842 7.0
END DESCRIPTION:
XS GIS Cut Line= 3
      2472374.99     13586575.03      2472425.00     13586325.00
      2472174.99     13586024.99
#Sta/Elev= 30
  4745.1  281.13  4765.5  279.77  4796.1  278.64  4847.1  275.48  4857.0  275.27
  4938.9  270.51  4949.1  269.47  4956.8  269.52  4989.9  267.28  4995.5  265.70
  4995.8  265.20  4999.3  265.20  4999.5  265.70  5003.3  265.70  5007.2  266.55
  5021.6  267.58  5034.5  267.88  5050.2  268.13  5065.6  268.95  5071.0  270.35
  5078.2  270.53  5091.8  268.67  5120.5  270.95  5184.8  274.04  5212.9  275.66
  5276.7  276.54  5319.6  278.50  5340.5  278.74  5362.6  279.88  5390.6  280.67
#Mann=8,-1,0
  4745.1    0.07       0  4857.0    0.05       0  4956.8    0.07       0
  4995.5    0.05       0  4999.5    0.07       0  5034.5    0.05       0
  5065.6    0.12       0  5184.8    0.07       0
Bank Sta=4995.5,4999.5
Exp/Cntr=0.3,0.1

Type RM Length L Ch R = 1,2976,226,226,226
BEGIN DESCRIPTION:
H21133
END DESCRIPTION:
XS GIS Cut Line= 3
      2472625.70     13586635.76      2472659.80     13586085.00
      2472505.07     13585883.07
#Sta/Elev= 30
  4638.3  279.74  4729.2  279.25  4789.3  276.49  4846.1  272.89  4899.6  269.45
  4919.6  268.92  4949.7  265.47  4959.7  262.60  4997.7  262.16  4998.0  261.66
  5001.5  261.66  5001.7  262.16  5009.8  262.74  5019.8  265.38  5049.8  264.62
  5069.9  264.92  5083.2  265.91  5109.4  266.98  5120.0  267.43  5140.0  269.83
  5222.1  271.83  5236.7  272.78  5272.0  273.13  5278.3  273.78  5301.0  273.69
  5307.3  274.98  5328.7  274.89  5386.2  278.38  5423.4  279.01  5444.5  279.36
#Mann=7,-1,0
  4638.3    0.07       0  4846.1    0.05       0  4997.7    0.05       0
  5001.7    0.05       0  5083.2    0.07       0  5109.4    0.05       0
  5423.4    0.07       0
Bank Sta=4997.7,5001.7
Exp/Cntr=0.3,0.1

Type RM Length L Ch R = 1,2750,441,441,441
BEGIN DESCRIPTION:
Stream0842 6.0
END DESCRIPTION:
XS GIS Cut Line= 3
      2472775.01     13586474.99      2472875.00     13586275.00
      2473074.97     13585975.04
#Sta/Elev= 30
  4776.8  272.22  4807.5  272.15  4829.9  271.39  4835.5  272.11  4852.3  271.61
  4866.2  271.95  4888.6  271.14  4897.0  269.91  4902.6  269.92  4919.3  267.87
  4924.9  268.11  4941.7  265.65  4969.6  263.32  4992.0  260.11  4997.6  258.39
  5003.4  258.39  5005.9  257.88  5006.2  257.38  5009.7  257.38  5009.9  257.88
  5080.0  261.97  5137.1  263.03  5180.7  265.33  5209.2  267.99  5239.3  269.28
  5245.3  269.07  5260.3  270.37  5296.3  272.25  5338.4  273.41  5360.9  274.66
#Mann=3,-1,0
  4776.8    0.05       0  5005.9    0.05       0  5009.9    0.05       0
Bank Sta=5005.9,5009.9
Exp/Cntr=0.3,0.1

Type RM Length L Ch R = 1,2309,451,451,451
BEGIN DESCRIPTION:
Stream0842 5.0
END DESCRIPTION:
XS GIS Cut Line= 3
      2472975.01     13586624.99      2473275.00     13586325.00
      2473275.00     13586175.05
#Sta/Elev= 30
  4580.3  264.61  4608.6  263.49  4622.7  263.30  4636.9  262.59  4665.1  262.51
  4679.3  262.02  4707.6  261.89  4721.7  261.41  4792.4  260.52  4863.1  259.12
  4899.2  258.83  4919.7  259.08  4948.0  258.72  4962.1  257.58  4976.3  255.15
  4988.4  253.77  4988.7  253.27  4992.2  253.27  4992.4  253.77  5007.0  253.79
  5014.5  256.69  5024.5  257.83  5034.5  259.36  5054.5  261.31  5064.5  261.46
  5074.5  262.49  5104.5  264.46  5124.5  265.45  5134.5  266.22  5154.5  266.96
#Mann=4,-1,0
  4580.3   0.035       0  4899.2    0.05       0  4988.4    0.05       0
  4992.4    0.05       0
Bank Sta=4988.4,4992.4
Exp/Cntr=0.3,0.1

Type RM Length L Ch R = 1,1858,471,471,471
BEGIN DESCRIPTION:
Stream0842 4.0
END DESCRIPTION:
XS GIS Cut Line= 3
      2473575.01     13586624.99      2473675.00     13586475.00
      2473725.00     13586275.02
#Sta/Elev= 30
  4819.7  262.76  4835.5  261.93  4842.2  261.88  4863.3  259.64  4884.3  258.67
  4899.3  256.96  4905.3  257.04  4914.3  256.28  4956.4  254.51  4986.4  254.15
  4992.5  253.18  4997.0  251.49  5002.5  251.49  5008.3  249.25  5008.5  248.75
  5012.0  248.75  5012.3  249.25  5018.0  252.11  5023.2  251.20  5030.9  252.75
  5041.2  253.32  5059.2  255.05  5064.4  255.16  5082.4  257.01  5092.7  257.37
  5105.6  258.26  5123.7  258.88  5146.8  260.81  5164.9  261.52  5206.1  264.33
#Mann=4,-1,0
  4819.7   0.035       0  4835.5    0.05       0  5008.3    0.05       0
  5012.3    0.05       0
Bank Sta=5008.3,5012.3
Exp/Cntr=0.3,0.1

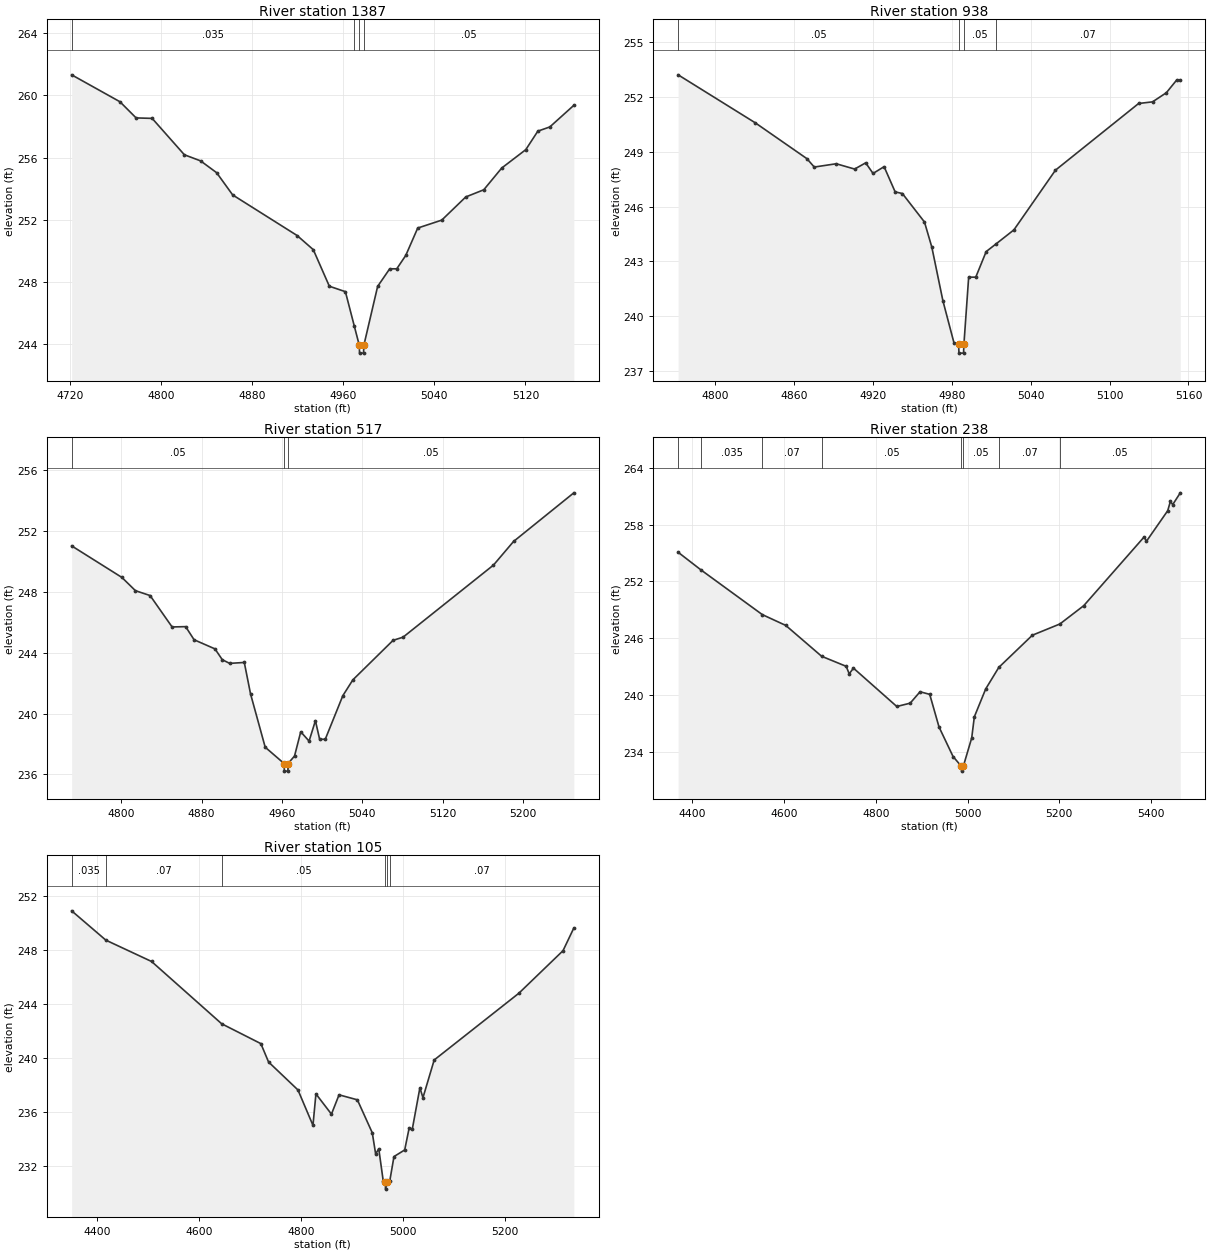
Type RM Length L Ch R = 1,1387,449,449,449
BEGIN DESCRIPTION:
Stream0842 3.0
END DESCRIPTION:
XS GIS Cut Line= 3
      2473874.98     13586875.02      2474075.00     13586675.00
      2474125.01     13586524.98
#Sta/Elev= 30
  4721.5  261.32  4763.9  259.59  4778.1  258.55  4792.2  258.52  4820.5  256.18
  4834.7  255.79  4848.8  255.03  4862.9  253.60  4919.5  250.99  4933.7  250.08
  4947.8  247.73  4961.9  247.38  4969.6  245.20  4974.1  243.93  4974.3  243.43
  4977.8  243.43  4978.1  243.93  4990.2  247.72  5000.8  248.85  5007.0  248.85
  5014.9  249.71  5025.4  251.47  5046.5  251.98  5067.6  253.47  5083.4  253.93
  5099.2  255.33  5120.3  256.51  5130.9  257.70  5141.4  257.97  5162.5  259.36
#Mann=4,-1,0
  4721.5   0.035       0  4969.6    0.05       0  4974.1    0.05       0
  4978.1    0.05       0
Bank Sta=4974.1,4978.1
Exp/Cntr=0.3,0.1

Type RM Length L Ch R = 1,938,421,421,421
BEGIN DESCRIPTION:
Stream0842 2.0
END DESCRIPTION:
XS GIS Cut Line= 3
      2474324.98     13587125.04      2474425.00     13586925.00
      2474475.01     13586774.97
#Sta/Elev= 30
  4772.0  253.22  4830.7  250.59  4869.9  248.63  4875.5  248.17  4892.2  248.35
  4906.2  248.06  4914.6  248.40  4920.2  247.82  4928.6  248.19  4937.0  246.81
  4942.5  246.72  4959.3  245.16  4964.9  243.78  4973.3  240.85  4981.7  238.55
  4985.3  238.48  4985.5  237.98  4989.0  237.98  4989.3  238.48  4992.9  242.14
  4998.3  242.14  5006.2  243.54  5013.7  243.96  5027.3  244.73  5058.9  248.00
  5122.1  251.65  5132.7  251.74  5143.2  252.24  5151.1  252.94  5153.8  252.94
#Mann=4,-1,0
  4772.0    0.05       0  4985.3    0.05       0  4989.3    0.05       0
  5013.7    0.07       0
Bank Sta=4985.3,4989.3
Exp/Cntr=0.3,0.1

Type RM Length L Ch R = 1,517,279,279,279
BEGIN DESCRIPTION:
Stream0842 1.0
END DESCRIPTION:
XS GIS Cut Line= 3
      2474575.02     13587274.99      2474775.00     13587125.00
      2474775.00     13586874.98
#Sta/Elev= 30
  4750.7  251.00  4800.7  248.93  4814.2  248.06  4828.8  247.74  4850.7  245.68
  4864.2  245.70  4872.6  244.84  4893.4  244.24  4900.7  243.53  4908.0  243.29
  4922.6  243.35  4928.8  241.29  4943.4  237.79  4962.2  236.72  4962.5  236.22
  4966.0  236.22  4966.2  236.72  4972.6  237.21  4978.8  238.80  4987.1  238.19
  4993.4  239.53  4997.6  238.31  5003.2  238.31  5020.7  241.17  5030.7  242.21
  5070.7  244.80  5080.7  245.01  5170.7  249.74  5190.7  251.29  5250.7  254.48
#Mann=3,-1,0
  4750.7    0.05       0  4962.2    0.05       0  4966.2    0.05       0
Bank Sta=4962.2,4966.2
Exp/Cntr=0.3,0.1

Type RM Length L Ch R = 1,238,133,133,133
BEGIN DESCRIPTION:
XS7821
END DESCRIPTION:
XS GIS Cut Line= 3
      2474551.39     13587532.12      2475020.14     13587263.02
      2475123.93     13586718.11
#Sta/Elev= 30
  4368.9  255.08  4418.4  253.23  4552.5  248.51  4603.7  247.37  4681.9  244.12
  4735.5  243.06  4742.0  242.27  4751.3  242.87  4845.8  238.83  4875.0  239.18
  4896.5  240.38  4917.6  240.11  4937.9  236.67  4968.5  233.56  4986.8  232.52
  4987.1  232.02  4990.8  232.52  5009.2  235.52  5014.9  237.74  5039.7  240.68
  5068.3  242.95  5141.5  246.34  5201.4  247.52  5253.5  249.45  5385.2  256.69
  5390.3  256.24  5436.7  259.46  5442.5  260.44  5447.5  260.10  5464.1  261.34
#Mann=8,-1,0
  4368.9    0.05       0  4418.4   0.035       0  4552.5    0.07       0
  4681.9    0.05       0  4986.8    0.05       0  4990.8    0.05       0
  5068.3    0.07       0  5201.4    0.05       0
Bank Sta=4986.8,4990.8
Exp/Cntr=0.3,0.1

Type RM Length L Ch R = 1,105,0,0,0
BEGIN DESCRIPTION:
H21132
END DESCRIPTION:
XS GIS Cut Line= 4
      2474650.55     13587545.91      2475088.54     13587294.13
      2475214.44     13587110.53      2475264.16     13586859.32
#Sta/Elev= 30
  4350.4  250.88  4417.4  248.71  4507.0  247.13  4644.3  242.52  4721.1  241.05
  4736.2  239.69  4793.8  237.62  4823.2  235.00  4829.0  237.33  4859.4  235.83
  4874.3  237.26  4910.2  236.89  4939.4  234.45  4946.0  232.88  4952.1  233.27
  4960.9  230.87  4965.0  230.78  4965.3  230.28  4969.0  230.78  4973.8  230.91
  4981.9  232.69  5002.9  233.18  5011.7  234.81  5017.8  234.72  5032.7  237.78
  5038.7  237.05  5060.7  239.84  5226.6  244.78  5313.1  247.93  5334.3  249.61
#Mann=6,-1,0
  4350.4   0.035       0  4417.4    0.07       0  4644.3    0.05       0
  4965.0    0.05       0  4969.0    0.05       0  4973.8    0.07       0
Bank Sta=4965,4969
Exp/Cntr=0.3,0.1

Chan Stop Cuts=-1