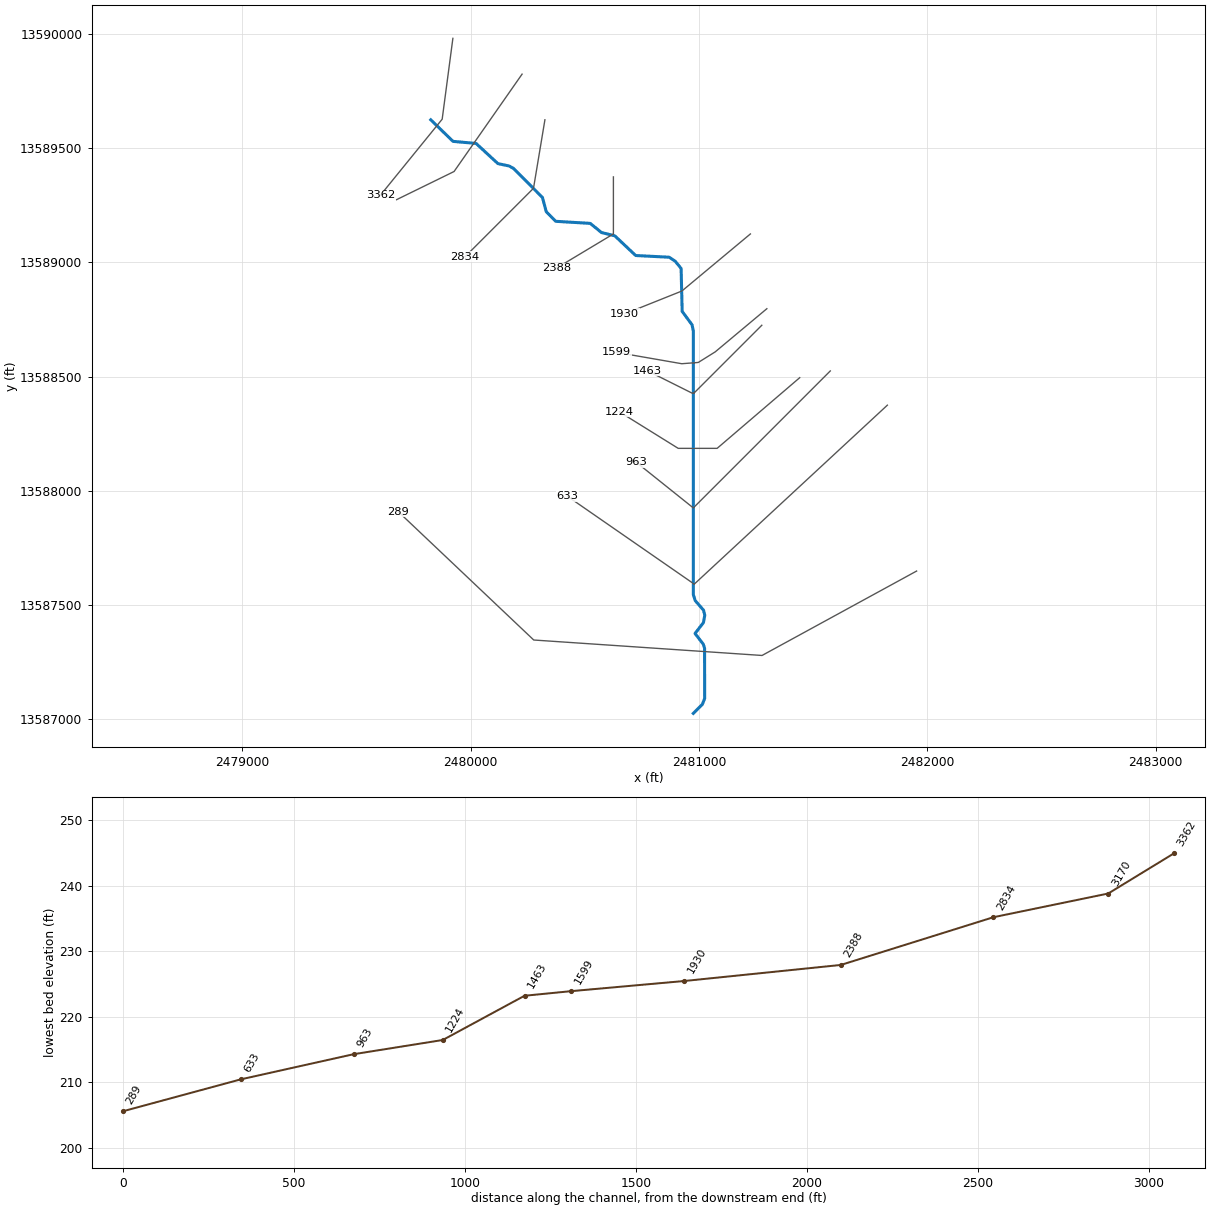
--- Stream0843.prj (project) ---

Proj Title=Stream0843 Base Level Engineering
Current Plan=p01
Default Exp/Contr=0.3,0.1
English Units
Geom File=g01
Flow File=f01
Plan File=p01
BEGIN DESCRIPTION:
Stream0843
END DESCRIPTION:

--- Stream0843.p01 (plan) ---

Plan Title=Multiple Run
Short Identifier=Multiple
Geom File=g01
Flow File=f01
Subcritical Flow
K Sum by GR= 0
Std Step Tol= 0.01
Critical Tol= 0.01
Num of Std Step Trials= 20
Max Error Tol= 0.3
Flow Tol Ratio= 0.001
Split Flow NTrial= 30
Split Flow Tol= 0.02
Split Flow Ratio= 0.02
Log Output Level= 0
Friction Slope Method= 1
Unsteady Friction Slope Method= 2
Unsteady Bridges Friction Slope Method= 1
Parabolic Critical Depth
Global Vel Dist=  1 , 1 , 1
Global Log Level= 0
CheckData=True
Encroach Param= -1, 0, 0, 0
BEGIN DESCRIPTION:
Multiple Run
END DESCRIPTION:

--- Stream0843.f01 (steady flow) ---

Flow Title=Multiple
Number of Profiles=7
Profile Names=10-year,25-year,50-year,1pct_min,100-year,1pct_plu,500-year
River Rch & RM= Stream0843,Reach-1,3362
     414     654     867     559    1115    2225    1823
Boundary for River Rch & Prof#=Stream0843,Reach-1,1
Up Type=0
Dn Type=3
Dn Slope=0.005
Boundary for River Rch & Prof#=Stream0843,Reach-1,2
Up Type=0
Dn Type=3
Dn Slope=0.005
Boundary for River Rch & Prof#=Stream0843,Reach-1,3
Up Type=0
Dn Type=3
Dn Slope=0.005
Boundary for River Rch & Prof#=Stream0843,Reach-1,4
Up Type=0
Dn Type=3
Dn Slope=0.005
Boundary for River Rch & Prof#=Stream0843,Reach-1,5
Up Type=0
Dn Type=3
Dn Slope=0.005
Boundary for River Rch & Prof#=Stream0843,Reach-1,6
Up Type=0
Dn Type=3
Dn Slope=0.005
Boundary for River Rch & Prof#=Stream0843,Reach-1,7
Up Type=0
Dn Type=3
Dn Slope=0.005

--- Stream0843.g01 (geometry) ---

Geom Title=Existing Conditions

River Reach=Stream0843,Reach-1
Reach XY= 30
      2479825.00     13589625.00      2479922.55     13589530.46
      2480023.50     13589521.38      2480118.96     13589433.18
      2480168.95     13589422.47      2480188.21     13589411.37
      2480314.21     13589284.66      2480330.74     13589222.43
      2480372.30     13589180.36      2480523.44     13589171.24
      2480572.83     13589131.14      2480631.05     13589116.84
      2480722.56     13589030.48      2480869.35     13589023.02
      2480895.66     13589005.60      2480921.57     13588973.78
      2480926.22     13588785.51      2480969.25     13588727.33
      2480975.20     13588700.08      2480975.09     13587545.03
      2480983.19     13587518.92      2481019.60     13587477.17
      2481025.21     13587454.79      2481019.35     13587422.71
      2480982.59     13587375.01      2481018.98     13587327.45
      2481024.34     13587309.84      2481024.64     13587090.15
      2481014.95     13587065.02      2480975.00     13587025.00

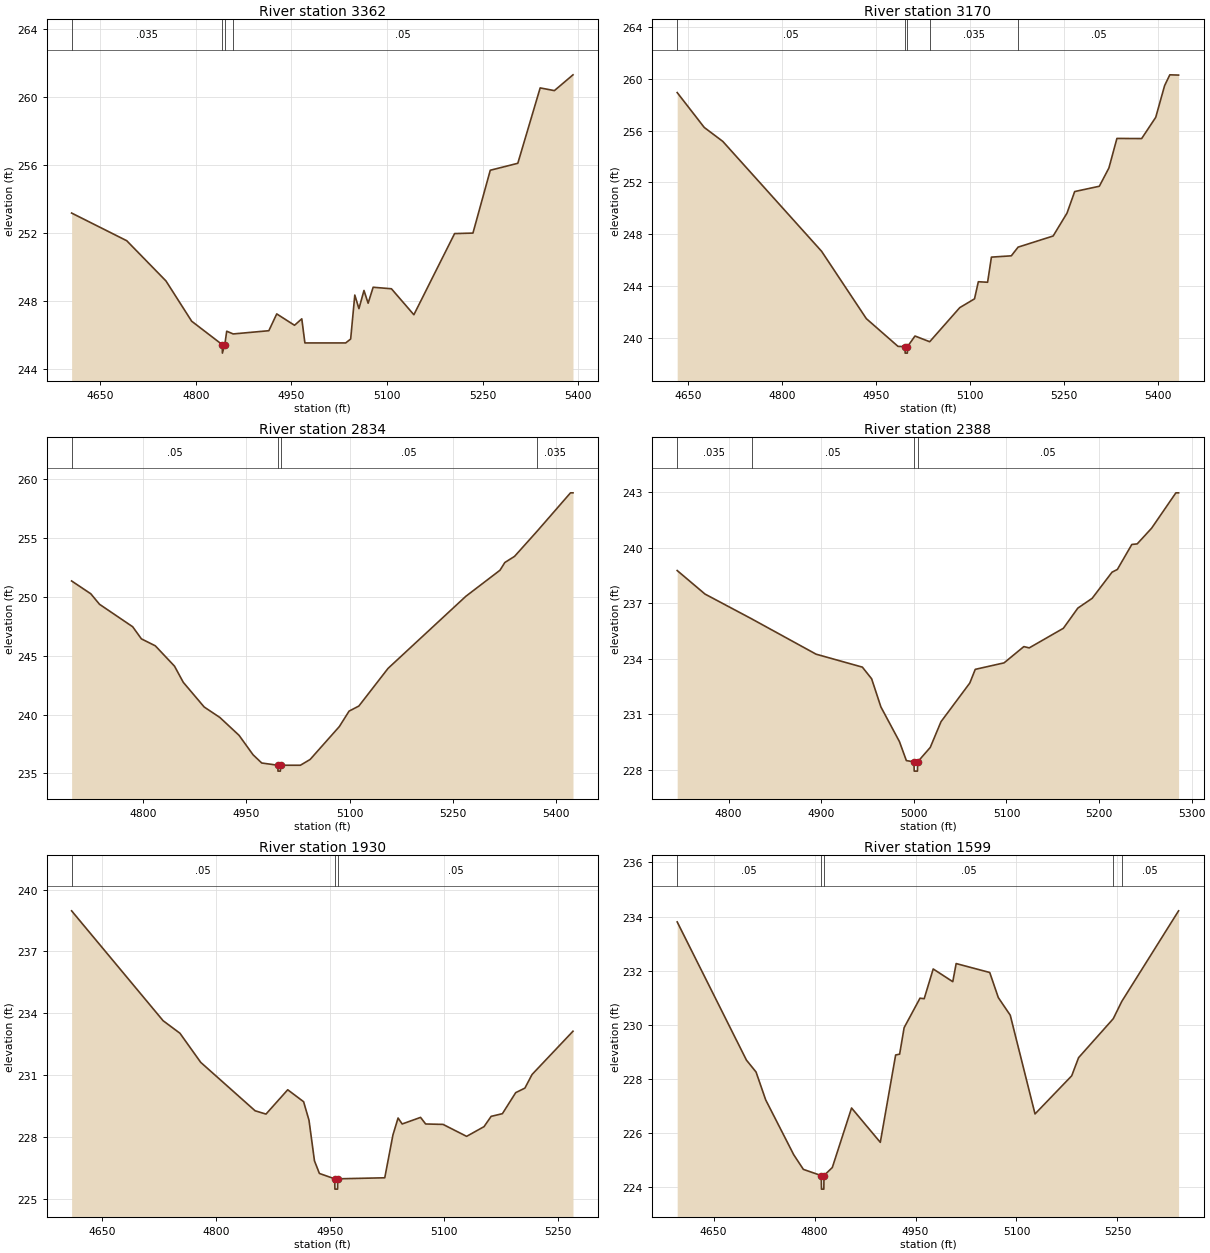
Type RM Length L Ch R = 1,3362,192,192,192
BEGIN DESCRIPTION:
XS7823
END DESCRIPTION:
XS GIS Cut Line= 3
      2479921.88     13589981.80      2479875.00     13589627.60
      2479604.15     13589294.25
#Sta/Elev= 30
  4605.2  253.19  4691.7  251.56  4753.3  249.19  4793.6  246.82  4841.6  245.44
  4841.8  244.94  4845.6  245.44  4848.6  246.23  4858.8  246.07  4914.7  246.26
  4927.1  247.25  4955.0  246.58  4966.4  246.96  4971.3  245.54  5035.3  245.54
  5043.1  245.77  5049.6  248.36  5056.1  247.56  5064.0  248.63  5070.5  247.88
  5078.4  248.82  5107.1  248.73  5142.3  247.20  5206.2  251.98  5235.0  252.01
  5262.2  255.71  5305.4  256.12  5340.5  260.56  5362.8  260.40  5392.0  261.33
#Mann=4,-1,0
  4605.2   0.035       0  4841.6    0.05       0  4845.6   0.035       0
  4858.8    0.05       0
Bank Sta=4841.6,4845.6
Exp/Cntr=0.3,0.1

Type RM Length L Ch R = 1,3170,336,336,336
BEGIN DESCRIPTION:
Stream0843 7.0
END DESCRIPTION:
XS GIS Cut Line= 3
      2480225.01     13589825.01      2479927.08     13589398.44
      2479675.00     13589275.00
#Sta/Elev= 30
  4632.6  258.93  4675.8  256.24  4705.5  255.16  4863.3  246.68  4934.8  241.48
  4985.4  239.34  4996.5  239.32  4996.8  238.82  5000.3  238.82  5000.5  239.32
  5012.5  240.14  5036.0  239.70  5084.0  242.33  5107.6  243.01  5113.7  244.33
  5128.5  244.29  5134.6  246.23  5166.4  246.33  5177.2  247.00  5233.2  247.86
  5255.4  249.63  5267.6  251.29  5307.0  251.70  5322.3  253.11  5335.1  255.39
  5374.6  255.38  5397.1  257.02  5411.3  259.47  5419.6  260.30  5433.6  260.28
#Mann=5,-1,0
  4632.6    0.05       0  4996.5    0.05       0  5000.5    0.05       0
  5036.0   0.035       0  5177.2    0.05       0
Bank Sta=4996.5,5000.5
Exp/Cntr=0.3,0.1

Type RM Length L Ch R = 1,2834,446,446,446
BEGIN DESCRIPTION:
Stream0843 6.0
END DESCRIPTION:
XS GIS Cut Line= 3
      2480325.00     13589624.98      2480275.00     13589325.00
      2479974.98     13589024.98
#Sta/Elev= 30
  4696.2  251.36  4724.1  250.27  4736.7  249.38  4784.9  247.47  4797.6  246.44
  4817.8  245.85  4845.7  244.12  4858.4  242.75  4888.8  240.65  4911.6  239.76
  4939.5  238.24  4959.8  236.59  4972.4  235.89  4995.8  235.70  4996.0  235.20
  4999.5  235.20  4999.8  235.70  5028.6  235.70  5042.7  236.19  5085.2  238.99
  5099.3  240.30  5113.5  240.73  5155.9  243.93  5269.0  250.06  5318.5  252.27
  5325.6  252.93  5339.7  253.45  5372.5  255.59  5421.0  258.85  5424.6  258.85
#Mann=4,-1,0
  4696.2    0.05       0  4995.8    0.05       0  4999.8    0.05       0
  5372.5   0.035       0
Bank Sta=4995.8,4999.8
Exp/Cntr=0.3,0.1

Type RM Length L Ch R = 1,2388,458,458,458
BEGIN DESCRIPTION:
Stream0843 5.0
END DESCRIPTION:
XS GIS Cut Line= 3
      2480625.00     13589374.96      2480625.00     13589125.00
      2480375.01     13588975.00
#Sta/Elev= 30
  4744.4  238.76  4774.4  237.49  4824.8  236.15  4894.4  234.24  4944.4  233.54
  4954.4  232.91  4964.4  231.39  4984.4  229.52  4991.9  228.49  5000.1  228.42
  5000.4  227.92  5003.9  227.92  5004.1  228.42  5017.7  229.20  5029.3  230.59
  5060.4  232.68  5066.3  233.42  5097.4  233.77  5118.8  234.65  5124.6  234.58
  5161.5  235.64  5177.1  236.73  5192.6  237.26  5214.0  238.67  5219.8  238.82
  5235.4  240.17  5241.2  240.20  5256.8  241.05  5283.0  242.96  5285.9  242.96
#Mann=4,-1,0
  4744.4   0.035       0  4824.8    0.05       0  5000.1    0.05       0
  5004.1    0.05       0
Bank Sta=5000.1,5004.1
Exp/Cntr=0.3,0.1

Type RM Length L Ch R = 1,1930,331,331,331
BEGIN DESCRIPTION:
Stream0843 4.0
END DESCRIPTION:
XS GIS Cut Line= 3
      2481225.01     13589125.01      2480925.00     13588875.00
      2480674.99     13588775.00
#Sta/Elev= 30
  4609.5  238.97  4729.9  233.64  4752.1  233.03  4779.4  231.62  4851.0  229.27
  4865.3  229.11  4893.9  230.29  4914.8  229.71  4921.9  228.81  4929.1  226.84
  4935.6  226.23  4955.7  225.97  4956.0  225.47  4959.5  225.47  4959.7  225.97
  5021.6  226.02  5032.3  228.09  5039.1  228.92  5044.5  228.63  5068.7  228.95
  5075.4  228.63  5098.3  228.61  5129.3  228.03  5152.2  228.50  5161.6  229.00
  5176.4  229.13  5193.9  230.15  5206.0  230.37  5215.4  231.03  5269.3  233.13
#Mann=3,-1,0
  4609.5    0.05       0  4955.7    0.05       0  4959.7    0.05       0
Bank Sta=4955.7,4959.7
Exp/Cntr=0.3,0.1

Type RM Length L Ch R = 1,1599,136,136,136
BEGIN DESCRIPTION:
Stream0843 3.0a
END DESCRIPTION:
XS GIS Cut Line= 5
      2481297.12     13588797.55      2481070.97     13588608.47
      2480996.80     13588562.12      2480924.50     13588556.55
      2480638.56     13588606.36
#Sta/Elev= 30
  4595.9  233.80  4698.8  228.69  4713.1  228.25  4727.4  227.22  4769.1  225.19
  4783.4  224.65  4810.0  224.42  4810.3  223.92  4813.8  223.92  4814.0  224.42
  4826.4  224.72  4855.0  226.92  4897.7  225.65  4920.5  228.88  4926.4  228.91
  4933.1  229.89  4956.7  230.98  4962.9  230.96  4976.3  232.06  5005.4  231.59
  5010.4  232.26  5060.3  231.93  5073.1  231.00  5090.8  230.35  5127.6  226.70
  5182.1  228.11  5192.3  228.78  5243.8  230.22  5256.5  230.86  5340.9  234.21
#Mann=5,-1,0
  4595.9    0.05       0  4810.0    0.05       0  4814.0    0.05       0
  5243.8    0.12       0  5256.5    0.05       0
Bank Sta=4810,4814
Exp/Cntr=0.3,0.1

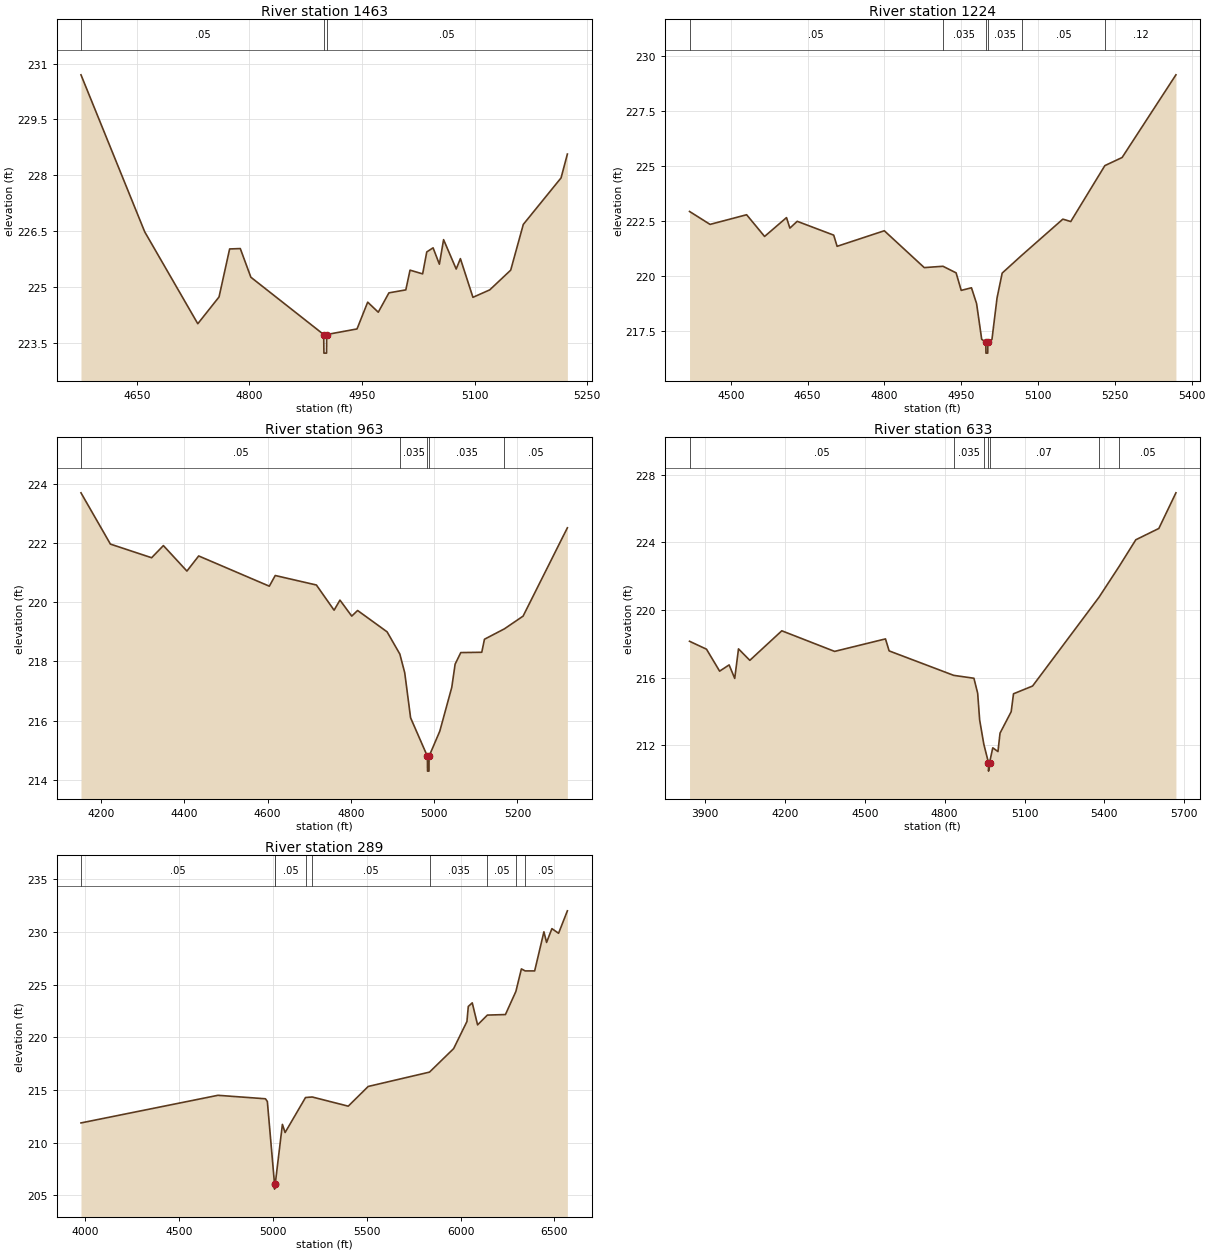
Type RM Length L Ch R = 1,1463,239,239,239
BEGIN DESCRIPTION:
Stream0843 3.0
END DESCRIPTION:
XS GIS Cut Line= 3
      2481275.03     13588725.03      2480975.00     13588425.00
      2480775.01     13588524.99
#Sta/Elev= 30
  4575.7  230.70  4660.6  226.48  4731.3  224.01  4759.6  224.73  4773.7  226.02
  4787.9  226.03  4802.0  225.26  4899.0  223.72  4899.3  223.22  4902.8  223.22
  4903.0  223.72  4943.4  223.87  4957.6  224.59  4971.7  224.32  4985.9  224.84
  5008.4  224.92  5014.0  225.45  5030.8  225.35  5036.3  225.94  5044.7  226.05
  5053.1  225.61  5058.7  226.27  5075.5  225.48  5081.1  225.76  5097.8  224.72
  5120.2  224.92  5148.1  225.45  5164.9  226.68  5215.2  227.93  5223.6  228.57
#Mann=3,-1,0
  4575.7    0.05       0  4899.0    0.05       0  4903.0    0.05       0
Bank Sta=4899,4903
Exp/Cntr=0.3,0.1

Type RM Length L Ch R = 1,1224,261,261,261
BEGIN DESCRIPTION:
H21134
END DESCRIPTION:
XS GIS Cut Line= 4
      2481441.18     13588495.50      2481079.32     13588185.83
      2480908.83     13588185.83      2480651.39     13588345.86
#Sta/Elev= 30
  4419.4  222.93  4459.5  222.34  4530.9  222.78  4566.0  221.79  4608.8  222.65
  4615.4  222.17  4629.7  222.48  4701.0  221.85  4707.6  221.34  4799.8  222.05
  4877.8  220.37  4914.4  220.43  4940.0  220.13  4950.0  219.33  4970.0  219.45
  4980.0  218.73  4990.0  217.10  4998.0  216.97  4998.3  216.47  5001.8  216.47
  5002.0  216.97  5010.0  217.09  5020.0  218.99  5030.0  220.12  5068.7  220.94
  5148.5  222.58  5163.9  222.47  5230.5  225.02  5264.2  225.39  5369.3  229.16
#Mann=6,-1,0
  4419.4    0.05       0  4914.4   0.035       0  4998.0   0.035       0
  5002.0   0.035       0  5068.7    0.05       0  5230.5    0.12       0
Bank Sta=4998,5002
Exp/Cntr=0.3,0.1

Type RM Length L Ch R = 1,963,330,330,330
BEGIN DESCRIPTION:
Stream0843 2.0
END DESCRIPTION:
XS GIS Cut Line= 3
      2481574.97     13588524.97      2480975.00     13587925.00
      2480725.04     13588124.97
#Sta/Elev= 30
  4151.5  223.69  4222.2  221.96  4321.2  221.50  4349.5  221.91  4406.0  221.05
  4434.3  221.56  4604.0  220.54  4618.2  220.90  4717.1  220.58  4759.6  219.73
  4773.7  220.07  4802.0  219.53  4816.1  219.72  4886.9  219.00  4917.6  218.25
  4929.3  217.62  4943.4  216.10  4983.8  214.80  4984.1  214.30  4987.6  214.30
  4987.8  214.80  5013.6  215.65  5042.4  217.13  5050.4  217.91  5064.0  218.30
  5114.4  218.31  5120.9  218.75  5168.7  219.10  5213.7  219.53  5320.1  222.51
#Mann=5,-1,0
  4151.5    0.05       0  4917.6   0.035       0  4983.8   0.035       0
  4987.8   0.035       0  5168.7    0.05       0
Bank Sta=4983.8,4987.8
Exp/Cntr=0.3,0.1

Type RM Length L Ch R = 1,633,344,344,344
BEGIN DESCRIPTION:
Stream0843 1.0
END DESCRIPTION:
XS GIS Cut Line= 3
      2481825.02     13588375.02      2480979.17     13587591.15
      2480424.96     13587975.03
#Sta/Elev= 30
  3841.4  218.15  3905.2  217.68  3954.5  216.38  3990.2  216.75  4011.2  215.95
  4025.4  217.70  4067.9  217.02  4188.1  218.77  4386.5  217.55  4577.6  218.29
  4591.3  217.58  4834.1  216.13  4909.9  215.96  4924.0  215.07  4931.4  213.49
  4947.1  212.05  4964.6  210.96  4964.8  210.46  4968.6  210.96  4980.7  211.84
  5000.2  211.62  5008.0  212.71  5049.9  213.98  5058.6  215.04  5130.3  215.50
  5379.9  220.76  5455.0  222.57  5518.1  224.16  5604.6  224.83  5668.8  226.94
#Mann=7,-1,0
  3841.4    0.05       0  4834.1   0.035       0  4947.1    0.07       0
  4964.6    0.05       0  4968.6    0.07       0  5379.9   0.035       0
  5455.0    0.05       0
Bank Sta=4964.6,4968.6
Exp/Cntr=0.3,0.1

Type RM Length L Ch R = 1,289,0,0,0
BEGIN DESCRIPTION:
XS7824
END DESCRIPTION:
XS GIS Cut Line= 4
      2481953.10     13587648.42      2481276.04     13587278.65
      2480276.04     13587346.35      2479682.31     13587908.83
#Sta/Elev= 30
  3977.2  211.88  4707.0  214.50  4960.2  214.17  4970.2  213.91  5008.3  206.10
  5008.5  205.60  5012.3  206.10  5050.4  211.74  5064.8  210.97  5173.6  214.29
  5209.3  214.34  5401.2  213.47  5507.6  215.34  5834.2  216.70  5962.8  218.93
  6033.6  221.50  6040.9  222.93  6062.0  223.27  6090.3  221.18  6142.5  222.11
  6238.7  222.16  6294.4  224.35  6323.7  226.49  6344.0  226.30  6394.5  226.30
  6443.8  230.01  6458.0  229.00  6486.3  230.31  6521.9  229.87  6568.8  232.00
#Mann=9,-1,0
  3977.2    0.05       0  5008.3    0.05       0  5012.3    0.05       0
  5173.6    0.07       0  5209.3    0.05       0  5834.2   0.035       0
  6142.5    0.05       0  6294.4   0.035       0  6344.0    0.05       0
Bank Sta=5008.3,5012.3
Exp/Cntr=0.3,0.1

Chan Stop Cuts=-1