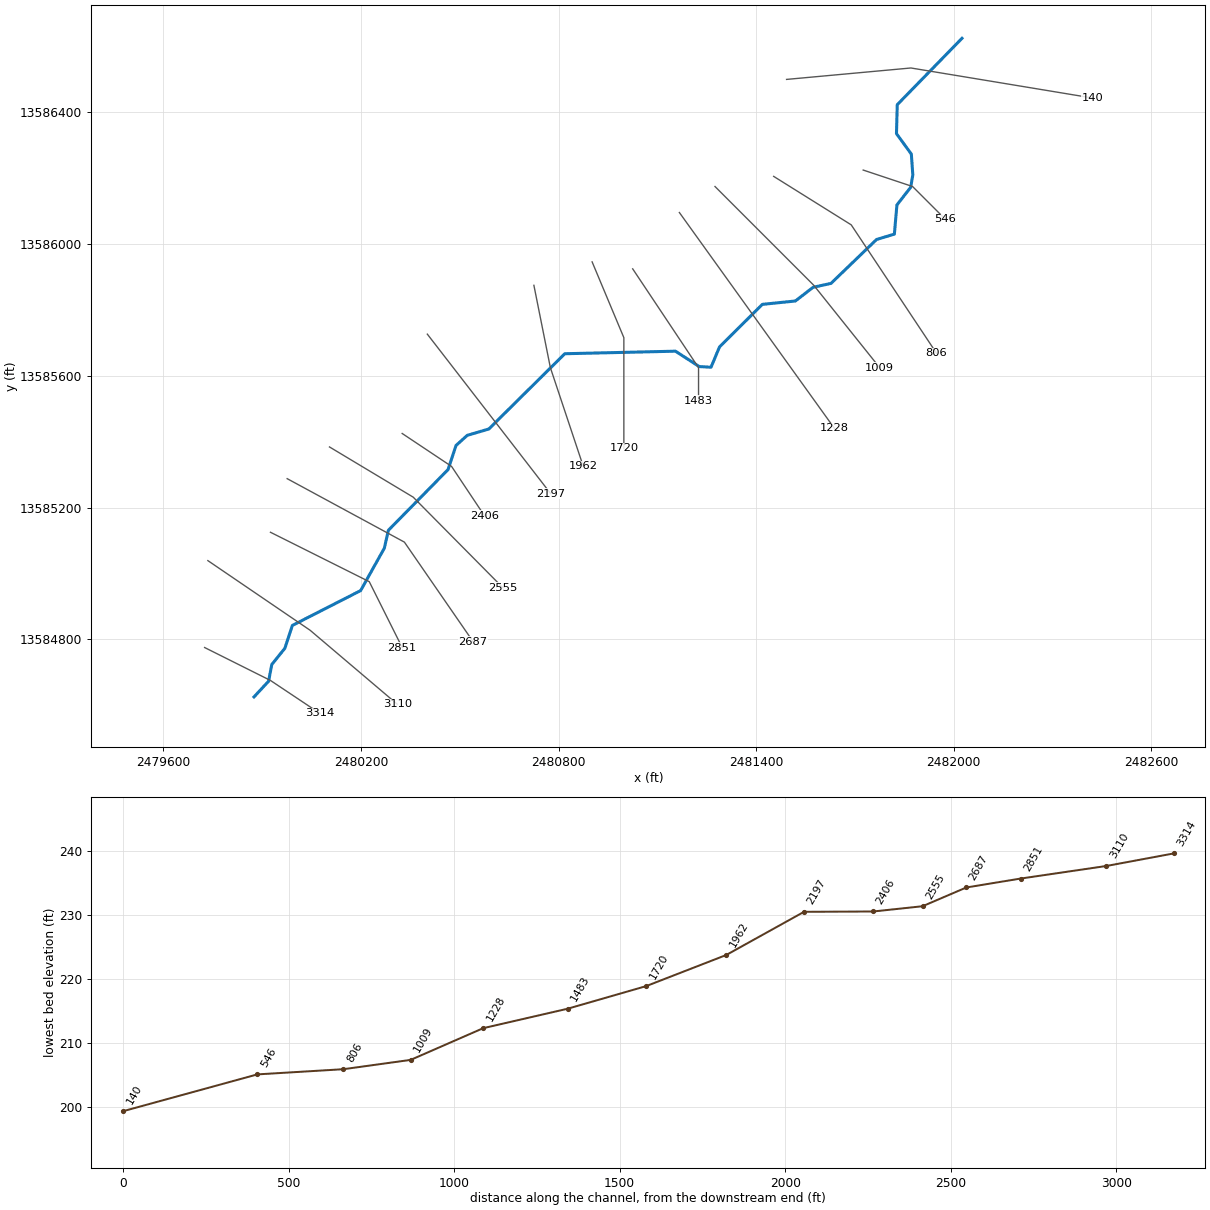
--- Stream0844.prj (project) ---

Proj Title=Stream0844 Base Level Engineering
Current Plan=p01
Default Exp/Contr=0.3,0.1
English Units
Geom File=g01
Flow File=f01
Plan File=p01
Y Axis Title=Elevation
X Axis Title(PF)=Main Channel Distance
X Axis Title(XS)=Station
BEGIN DESCRIPTION:
Stream0844
END DESCRIPTION:
DSS Export Rating Curves= 0
DSS Export Rating Curve Sorted= 0
DSS Export Volume Flow Curves= 0
DXF OffsetX= 0
DXF OffsetY= 0
DXF ScaleX= 1
DXF ScaleY= 10

--- Stream0844.p01 (plan) ---

Plan Title=Multiple Run
Short Identifier=Multiple
Geom File=g01
Flow File=f01
Subcritical Flow
K Sum by GR= 0
Std Step Tol= 0.01
Critical Tol= 0.01
Num of Std Step Trials= 20
Max Error Tol= 0.3
Flow Tol Ratio= 0.001
Split Flow NTrial= 30
Split Flow Tol= 0.02
Split Flow Ratio= 0.02
Log Output Level= 0
Friction Slope Method= 1
Unsteady Friction Slope Method= 2
Unsteady Bridges Friction Slope Method= 1
Parabolic Critical Depth
Global Vel Dist=  1 , 1 , 1
Global Log Level= 0
CheckData=True
Encroach Param= -1, 0, 0, 0
BEGIN DESCRIPTION:
Multiple Run
END DESCRIPTION:

--- Stream0844.f01 (steady flow) ---

Flow Title=Multiple
Number of Profiles=7
Profile Names=10-year,25-year,50-year,1pct_min,100-year,1pct_plu,500-year
River Rch & RM= Stream0844,Reach-1,3314
     479     763    1018     659    1315    2623    2170
Boundary for River Rch & Prof#=Stream0844,Reach-1,1
Up Type=0
Dn Type=3
Dn Slope=0.005
Boundary for River Rch & Prof#=Stream0844,Reach-1,2
Up Type=0
Dn Type=3
Dn Slope=0.005
Boundary for River Rch & Prof#=Stream0844,Reach-1,3
Up Type=0
Dn Type=3
Dn Slope=0.005
Boundary for River Rch & Prof#=Stream0844,Reach-1,4
Up Type=0
Dn Type=3
Dn Slope=0.005
Boundary for River Rch & Prof#=Stream0844,Reach-1,5
Up Type=0
Dn Type=3
Dn Slope=0.005
Boundary for River Rch & Prof#=Stream0844,Reach-1,6
Up Type=0
Dn Type=3
Dn Slope=0.005
Boundary for River Rch & Prof#=Stream0844,Reach-1,7
Up Type=0
Dn Type=3
Dn Slope=0.005

--- Stream0844.g01 (geometry) ---

Geom Title=Existing Conditions
Program Version=4.10

River Reach=Stream0844      ,Reach-1
Reach XY= 30
        2479875.       13584625.      2479919.33     13584672.64
      2479929.04     13584723.33      2479968.89     13584772.83
      2479991.48     13584842.06      2480198.84     13584947.85
      2480270.81     13585076.73      2480283.14     13585131.06
      2480464.21     13585315.34      2480488.49     13585388.56
      2480522.46     13585419.25       2480588.2     13585438.64
      2480818.81     13585667.19      2481154.99     13585674.91
      2481227.11     13585628.19      2481262.99     13585626.17
      2481288.73     13585687.92      2481418.83     13585817.14
      2481519.03     13585827.33      2481572.83     13585868.86
       2481627.3     13585880.83      2481765.62      13586014.1
      2481819.74     13586030.47       2481827.4     13586118.94
      2481869.32     13586172.69      2481875.71     13586209.94
      2481871.29      13586273.4       2481826.1     13586335.55
      2481828.46      13586423.5        2482025.       13586625.

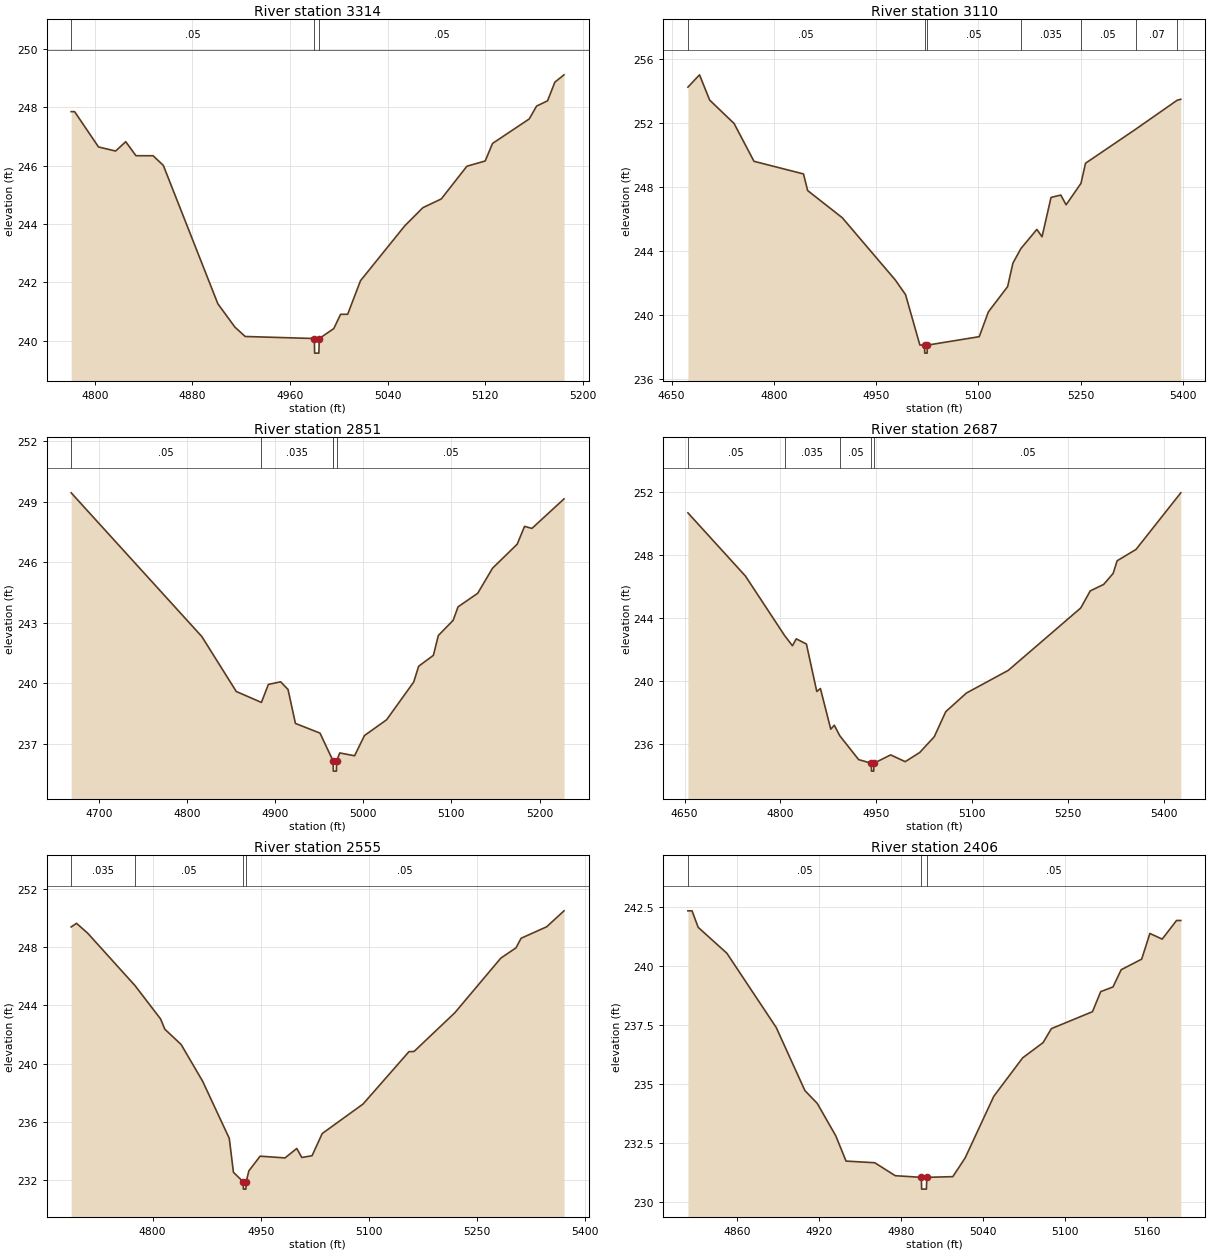
Type RM Length L Ch R = 1 ,3314    ,204,204,204
BEGIN DESCRIPTION:
Stream0844 7.0
END DESCRIPTION:
XS GIS Cut Line= 3
      2479724.98     13584775.01        2479925.       13584675.
        2480075.       13584575.
#Sta/Elev= 30
  4780.6  247.85  4783.4  247.85    4803  246.64    4817   246.5  4825.3  246.82
  4833.7  246.34  4847.7  246.34  4856.1  246.01  4900.8  241.27  4914.8  240.47
  4923.2  240.15  4979.9  240.08  4980.1  239.58  4983.6  239.58  4983.9  240.08
  4995.8  240.42  5001.4  240.91  5007.2  240.91  5017.7  242.06  5053.8  243.93
  5068.8  244.56  5083.9  244.86  5104.9  245.98  5119.9  246.16  5125.9  246.76
    5156   247.6    5162  248.04    5171  248.22    5177  248.86  5184.5  249.11
#Mann= 3 ,-1 , 0
  4780.6     .05       0  4979.9     .05       0  4983.9     .05       0
Bank Sta=4979.9,4983.9
XS Rating Curve= 0 ,0
Exp/Cntr=0.3,0.1

Type RM Length L Ch R = 1 ,3110    ,259,259,259
BEGIN DESCRIPTION:
H21141
END DESCRIPTION:
XS GIS Cut Line= 3
      2479734.92     13585038.87      2480045.38     13584827.43
      2480310.18     13584602.75
#Sta/Elev= 30
  4673.9  254.26  4690.9  255.03  4705.8  253.45  4741.7  251.98  4770.8  249.62
  4843.4  248.83  4849.5  247.79  4900.3  246.09  4978.2  242.19  4993.1  241.28
  5014.1  238.13    5021  238.12  5021.3  237.62  5024.8  237.62    5025  238.12
  5101.2  238.65  5114.6   240.2  5142.8  241.78  5150.6  243.25  5162.3  244.16
  5185.7  245.36  5193.3   244.9  5206.5  247.36  5220.8  247.51  5228.6   246.9
  5250.4  248.24  5257.1   249.5  5330.4  251.62  5391.5  253.44  5396.8   253.5
#Mann= 7 ,-1 , 0
  4673.9     .05       0    5021     .05       0    5025     .05       0
  5162.3    .035       0  5250.4     .05       0  5330.4     .07       0
  5391.5     .05       0
Bank Sta=5021,5025
XS Rating Curve= 0 ,0
Exp/Cntr=0.3,0.1

Type RM Length L Ch R = 1 ,2851    ,164,164,164
BEGIN DESCRIPTION:
Stream0844 6.0
END DESCRIPTION:
XS GIS Cut Line= 3
      2479924.96     13585125.02        2480225.       13584975.
      2480325.02     13584774.97
#Sta/Elev= 30
  4668.7  249.43  4816.9  242.32    4856   239.6  4884.5  239.06  4892.4  239.95
  4906.3  240.08  4914.7   239.7  4923.1  238.02    4951  237.54  4965.2  236.22
  4965.8  236.16  4966.1  235.66  4969.6  235.66  4969.8  236.16  4973.4  236.56
  4990.2  236.42  5001.4  237.42  5026.5   238.2  5057.3  240.07  5062.9  240.85
  5079.6  241.39  5085.2  242.37    5102  243.12  5107.6  243.79  5129.9  244.46
  5146.7   245.7  5174.7  246.89    5183  247.77  5191.4  247.67  5227.8  249.13
#Mann= 5 ,-1 , 0
  4668.7     .05       0  4884.5    .035       0  4965.2     .05       0
  4965.8     .05       0  4969.8     .05       0
Bank Sta=4965.8,4969.8
XS Rating Curve= 0 ,0
Exp/Cntr=0.3,0.1

Type RM Length L Ch R = 1 ,2687    ,132,132,132
BEGIN DESCRIPTION:
H21140
END DESCRIPTION:
XS GIS Cut Line= 3
      2479975.75      13585287.8      2480331.75     13585095.07
      2480540.28     13584792.97
#Sta/Elev= 30
  4655.1  250.65  4745.2  246.64  4806.5  242.87  4818.8  242.22  4824.8  242.66
  4840.7  242.33  4856.9  239.32  4862.6  239.51  4878.8  236.93  4884.4  237.18
    4893  236.51  4922.5     235  4942.4  234.77  4942.6  234.27  4946.1  234.27
  4946.4  234.77  4972.6   235.3  4995.4  234.87  5018.1  235.45  5040.9  236.45
  5058.9  238.04  5091.2  239.22  5156.8  240.66  5270.4  244.62  5285.2   245.7
  5306.2  246.11  5321.1  246.81  5327.3  247.61  5356.9  248.33    5427  251.92
#Mann= 5 ,-1 , 0
  4655.1     .05       0  4806.5    .035       0    4893     .05       0
  4942.4     .05       0  4946.4     .05       0
Bank Sta=4942.4,4946.4
XS Rating Curve= 0 ,0
Exp/Cntr=0.3,0.1

Type RM Length L Ch R = 1 ,2555    ,149,149,149
BEGIN DESCRIPTION:
H21139
END DESCRIPTION:
XS GIS Cut Line= 3
      2480104.26     13585384.12      2480358.52     13585231.57
      2480630.75     13584956.66
#Sta/Elev= 30
  4687.2  249.41  4694.6  249.66  4710.1  248.98  4775.9  245.36  4811.2  243.07
    4817  242.37  4839.7  241.31  4869.5  238.78  4906.4  234.85  4912.2  232.51
  4925.8  231.85    4926  231.35  4929.5  231.35  4929.8  231.85  4933.6  232.61
  4949.2  233.62  4983.7   233.5    5000  234.15    5007  233.53  5021.2  233.65
  5035.3  235.18  5091.9  237.21  5155.6  240.82  5162.6  240.83  5219.2   243.5
  5282.9  247.26    5304  247.97  5311.1  248.63  5346.5  249.42  5370.6  250.52
#Mann= 4 ,-1 , 0
  4687.2    .035       0  4775.9     .05       0  4925.8     .05       0
  4929.8     .05       0
Bank Sta=4925.8,4929.8
XS Rating Curve= 0 ,0
Exp/Cntr=0.3,0.1

Type RM Length L Ch R = 1 ,2406    ,209,209,209
BEGIN DESCRIPTION:
Stream0844 5.0
END DESCRIPTION:
XS GIS Cut Line= 3
        2480325.       13585425.        2480475.       13585325.
      2480575.03     13585174.96
#Sta/Elev= 30
  4824.2  242.34  4827.2  242.34  4831.7  241.64  4852.7  240.54  4888.8  237.39
  4909.8  234.71  4918.8  234.17  4932.4  232.79  4939.9  231.72  4960.9  231.65
  4975.9   231.1    4995  231.03  4995.2  230.53  4998.7  230.53    4999  231.03
    5018  231.06    5027  231.85    5048  234.47  5069.1   236.1  5084.1  236.75
  5090.1  237.34  5120.2  238.06  5126.2  238.91  5135.2  239.11  5141.2  239.84
  5156.2  240.29  5162.2  241.38  5171.2  241.14  5181.7  241.93  5184.8  241.93
#Mann= 3 ,-1 , 0
  4824.2     .05       0    4995     .05       0    4999     .05       0
Bank Sta=4995,4999
XS Rating Curve= 0 ,0
Exp/Cntr=0.3,0.1

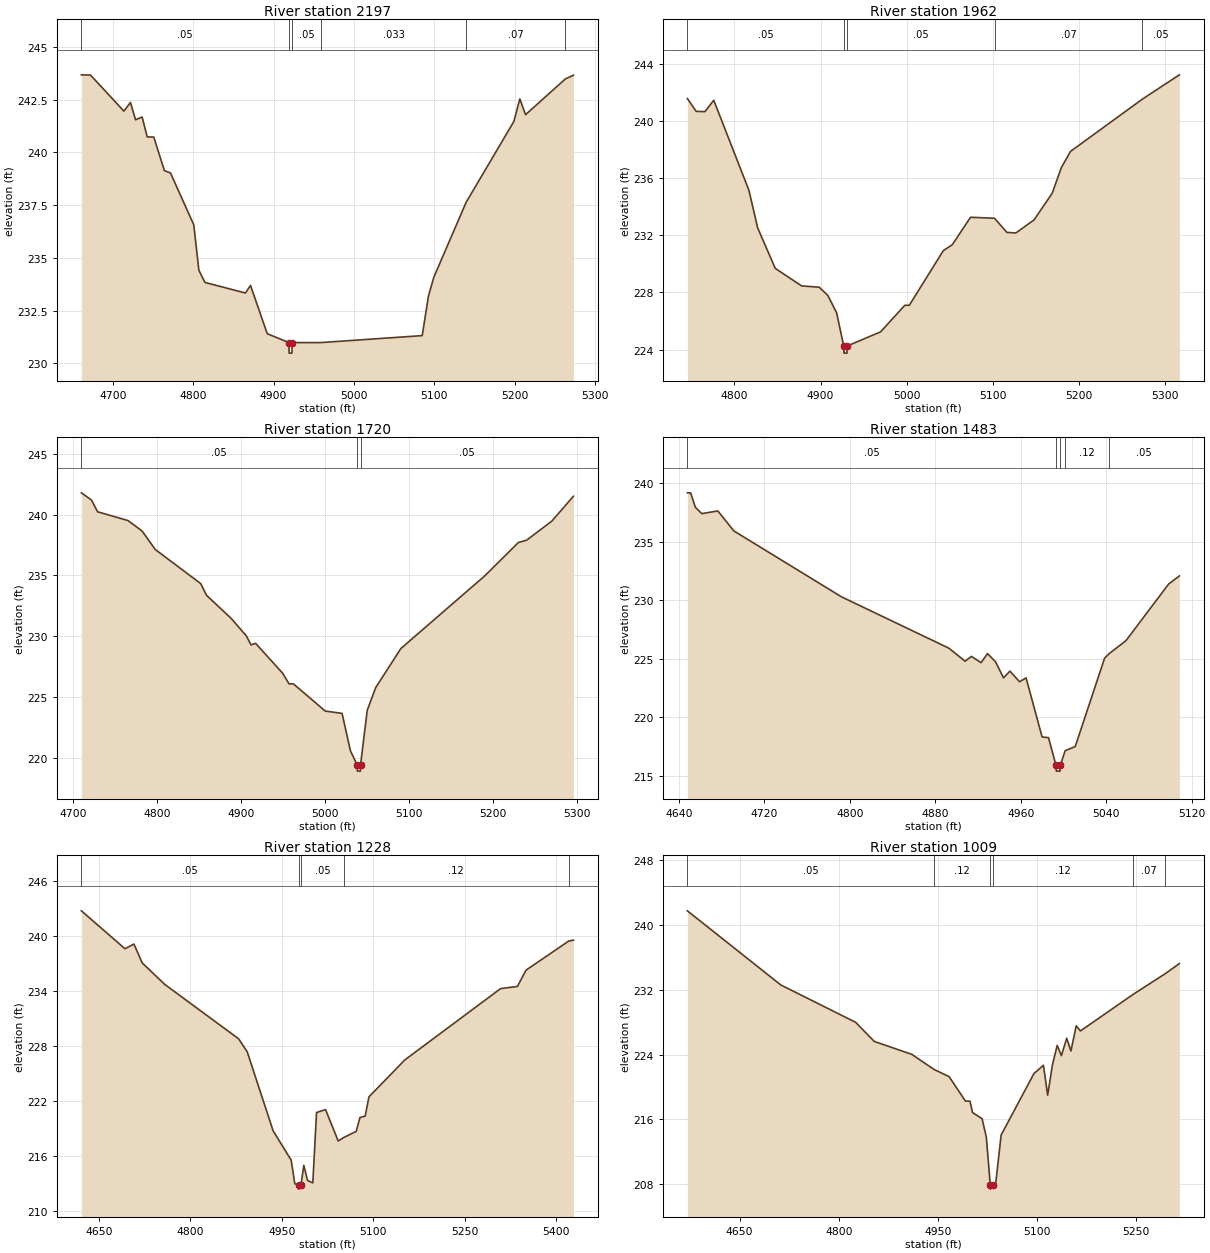
Type RM Length L Ch R = 1 ,2197    ,235,235,235
BEGIN DESCRIPTION:
H21138
END DESCRIPTION:
XS GIS Cut Line= 2
      2480401.35     13585726.69      2480776.03     13585242.28
#Sta/Elev= 30
  4660.8  243.67  4672.1  243.66  4713.7  241.95  4721.9  242.36  4728.2  241.54
  4736.4  241.67  4742.7  240.73  4750.9  240.72  4764.1  239.13  4771.7  239.02
  4800.7  236.56    4807  234.41  4814.6  233.83    4865  233.33  4871.3  233.69
  4892.1   231.4  4919.1  230.98  4919.4  230.48  4922.9  230.48  4923.1  230.98
  4958.9  230.98    5085  231.31  5092.8  233.19  5099.5  234.08  5139.7  237.63
  5199.1  241.46  5206.5  242.53  5213.6  241.78  5263.3  243.48  5273.2  243.65
#Mann= 6 ,-1 , 0
  4660.8     .05       0  4919.1    .033       0  4923.1     .05       0
  4958.9    .033       0  5139.7     .07       0  5263.3     .05       0
Bank Sta=4919.1,4923.1
XS Rating Curve= 0 ,0
Exp/Cntr=0.3,0.1

Type RM Length L Ch R = 1 ,1962    ,242,242,242
BEGIN DESCRIPTION:
Stream0844 4.0
END DESCRIPTION:
XS GIS Cut Line= 3
        2480725.     13585874.98        2480775.       13585625.
      2480875.01     13585324.96
#Sta/Elev= 30
  4745.4  241.59  4755.6  240.69  4765.8  240.67    4776  241.47  4816.8  235.17
    4827  232.53  4847.4  229.69    4878  228.46  4898.4  228.37  4908.5  227.79
  4918.7  226.57  4926.9  224.25  4927.2  223.75  4930.7  223.75  4930.9  224.25
  4969.7  225.24  4997.8   227.1    5003   227.1  5042.5  230.93    5053  231.35
  5074.1  233.27    5102   233.2  5116.3  232.21  5126.8  232.17  5147.9  233.09
    5169  234.96  5179.5  236.74  5190.1  237.88  5273.7  241.55  5316.6  243.25
#Mann= 5 ,-1 , 0
  4745.4     .05       0  4926.9     .05       0  4930.9     .05       0
    5102     .07       0  5273.7     .05       0
Bank Sta=4926.9,4930.9
XS Rating Curve= 0 ,0
Exp/Cntr=0.3,0.1

Type RM Length L Ch R = 1 ,1720    ,237,237,237
BEGIN DESCRIPTION:
H21137
END DESCRIPTION:
XS GIS Cut Line= 3
      2480901.83     13585946.16      2480998.18       13585716.
      2480998.18     13585379.41
#Sta/Elev= 30
  4709.5  241.79  4721.6  241.19  4728.8  240.23    4765  239.51  4781.8  238.65
  4797.5  237.13  4851.7  234.32  4858.6  233.36  4887.8  231.47  4905.9  230.03
  4911.6  229.28    4917  229.41  4949.3  226.95  4956.8  226.08    4962  226.08
    5000  223.84    5020  223.65    5030  220.57    5038   219.4  5038.3   218.9
  5041.8   218.9    5042   219.4    5050   223.9    5060  225.76    5090  228.98
    5190  234.96    5230   237.7    5240   237.9    5270  239.47  5295.6  241.51
#Mann= 3 ,-1 , 0
  4709.5     .05       0    5038     .05       0    5042     .05       0
Bank Sta=5038,5042
XS Rating Curve= 0 ,0
Exp/Cntr=0.3,0.1

Type RM Length L Ch R = 1 ,1483    ,255,255,255
BEGIN DESCRIPTION:
Stream0844 3.0
END DESCRIPTION:
XS GIS Cut Line= 3
      2481025.02     13585924.98        2481225.       13585625.
        2481225.     13585525.03
#Sta/Elev= 30
    4648   239.2    4651   239.2  4655.5  237.96  4661.5  237.42  4676.5  237.65
  4691.5  235.94  4792.2   230.3  4892.8   225.9  4907.9  224.79  4913.9   225.2
  4922.9  224.66  4928.9  225.44  4936.4  224.74  4943.9  223.36  4949.9  223.94
  4958.9  223.03    4965  223.36    4980  218.31    4986  218.24    4993  215.88
  4993.3  215.38  4996.8  215.38    4997  215.88  5001.6  217.13    5011  217.48
  5038.5  225.05  5042.8  225.44  5058.5  226.55  5098.5   231.4  5108.5  232.09
#Mann= 5 ,-1 , 0
    4648     .05       0    4993     .05       0    4997     .05       0
  5001.6     .12       0  5042.8     .05       0
Bank Sta=4993,4997
XS Rating Curve= 0 ,0
Exp/Cntr=0.3,0.1

Type RM Length L Ch R = 1 ,1228    ,219,219,219
BEGIN DESCRIPTION:
H21136
END DESCRIPTION:
XS GIS Cut Line= 2
      2481166.81     13586096.02      2481637.81     13585440.36
#Sta/Elev= 30
  4621.2  242.76  4692.7  238.62  4707.4  239.13    4721  237.07  4757.8  234.73
  4879.3  228.77  4893.3  227.35  4935.8  218.72  4965.3  215.53  4971.4  212.93
  4977.5  212.85  4977.8  212.35  4981.5  212.85  4986.2  214.95  4992.3   213.3
  5000.9  213.03    5007  220.72  5021.8  221.04  5042.6  217.61  5051.7  217.99
  5072.1  218.66  5078.3  220.18  5086.8  220.33    5093  222.43  5151.9  226.47
    5309  234.26  5336.6   234.5  5350.8  236.28  5421.1  239.47  5428.5  239.55
#Mann= 5 ,-1 , 0
  4621.2     .05       0  4977.5     .05       0  4981.5     .05       0
  5051.7     .12       0  5421.1     .05       0
Bank Sta=4977.5,4981.5
XS Rating Curve= 0 ,0
Exp/Cntr=0.3,0.1

Type RM Length L Ch R = 1 ,1009    ,203,203,203
BEGIN DESCRIPTION:
Stream0844 2.0
END DESCRIPTION:
XS GIS Cut Line= 3
      2481275.01     13586174.99        2481575.       13585875.
      2481774.99     13585625.01
#Sta/Elev= 30
  4570.9  241.72  4712.3  232.58  4825.4  227.98  4853.7  225.62  4910.3  224.03
  4944.2  222.16  4966.9  221.28  4991.6  218.26  4998.4  218.26  5002.4  216.85
  5016.8  216.09  5023.2  213.81  5029.2  207.91  5029.4  207.41  5033.2  207.91
  5037.6  208.25  5045.6  214.08  5095.2  221.65  5109.6  222.68    5116  218.99
  5123.2  222.72  5130.4  225.13  5136.8  223.87  5144.8  226.01  5151.2  224.44
  5159.2  227.54  5165.6  226.91  5245.5  231.43  5293.5  233.95  5315.3  235.22
#Mann= 6 ,-1 , 0
  4570.9     .05       0  4944.2     .12       0  5029.2     .05       0
  5033.2     .12       0  5245.5     .07       0  5293.5     .12       0
Bank Sta=5029.2,5033.2
XS Rating Curve= 0 ,0
Exp/Cntr=0.3,0.1

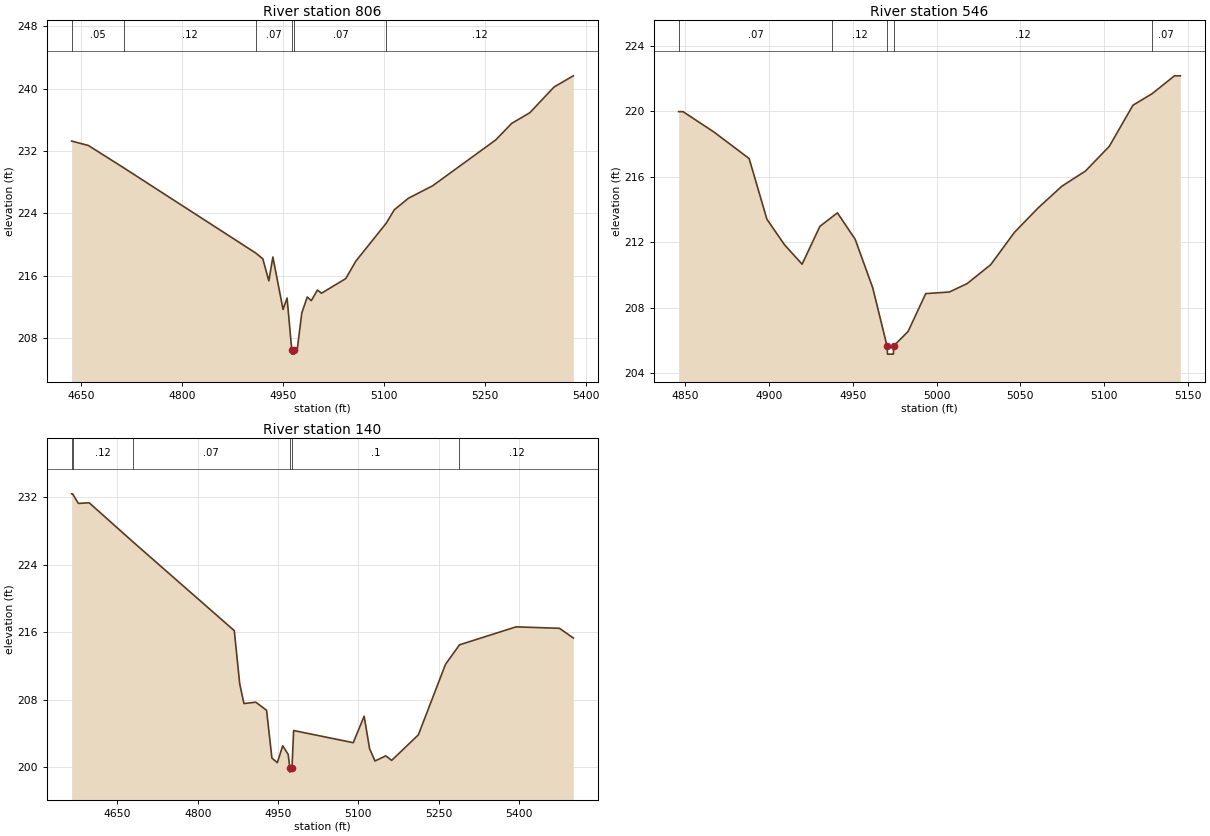
Type RM Length L Ch R = 1 ,806     ,260,260,260
BEGIN DESCRIPTION:
H21135
END DESCRIPTION:
XS GIS Cut Line= 3
      2481453.16     13586205.78      2481688.69     13586058.58
      2481947.59     13585668.89
#Sta/Elev= 30
    4636  233.29  4660.8  232.73  4714.5   229.8  4909.6  218.93  4920.1  218.19
  4929.1  215.36  4935.1  218.42  4950.2  211.69  4956.2  213.15  4963.2  206.46
  4963.4  205.96  4966.9  205.96  4967.2  206.46  4971.2  206.49  4978.1  211.25
  4986.2  213.29  4992.2  212.82  5001.3  214.18  5007.3  213.77  5043.4  215.65
  5058.4  217.89  5103.8  222.78  5115.5  224.47  5136.6  225.96  5172.6  227.56
  5266.2  233.43  5289.9  235.55    5317  236.93    5353  240.23  5381.6  241.66
#Mann= 6 ,-1 , 0
    4636     .05       0  4714.5     .12       0  4909.6     .07       0
  4963.2     .05       0  4967.2     .07       0  5103.8     .12       0
Bank Sta=4963.2,4967.2
XS Rating Curve= 0 ,0
Exp/Cntr=0.3,0.1

Type RM Length L Ch R = 1 ,546     ,406,406,406
BEGIN DESCRIPTION:
Stream0844 1.0
END DESCRIPTION:
XS GIS Cut Line= 3
      2481725.05     13586224.98        2481875.       13586175.
      2481975.01     13586074.99
#Sta/Elev= 30
    4846  219.98  4848.6  219.98    4867  218.74  4888.1  217.11  4898.7   213.4
  4909.2  211.84  4919.7  210.65  4930.3  212.96  4937.6  213.54  4940.8  213.79
  4951.4  212.17  4961.9   209.2  4970.4  205.65  4970.7  205.15  4974.2  205.15
  4974.4  205.65    4983  206.54  4993.5  208.85  5007.6  208.95  5018.2  209.46
  5032.3  210.62  5046.5   212.6  5060.6  214.09  5074.8  215.42  5088.9  216.35
  5103.1  217.86  5117.2  220.37  5128.7  221.08    5142  222.17  5145.5  222.17
#Mann= 5 ,-1 , 0
    4846     .07       0  4937.6     .12       0  4970.4     .04       0
  4974.4     .12       0  5128.7     .07       0
Bank Sta=4970.4,4974.4
XS Rating Curve= 0 ,0
Exp/Cntr=0.3,0.1

Type RM Length L Ch R = 1 ,140     ,0,0,0
BEGIN DESCRIPTION:
XS7825
END DESCRIPTION:
XS GIS Cut Line= 3
      2481492.36     13586500.26      2481869.97     13586534.98
      2482420.59     13586443.93
#Sta/Elev= 30
  4564.3   232.4  4566.1   232.4    4577  231.26  4597.1  231.34  4678.1  226.75
  4868.2  216.18  4878.3  209.89  4886.2  207.54  4908.4   207.7  4928.5  206.74
  4938.5  201.07  4948.6  200.54  4958.7  202.53  4968.9  201.51    4972  199.91
  4972.2  199.41    4976  199.91  4979.1  204.34  5090.5   202.9  5110.8  206.04
  5120.9  202.21    5131  200.73  5151.3  201.34  5162.2   200.8  5212.1  203.83
  5262.8  212.19  5288.9   214.5  5394.6  216.63  5475.7  216.46  5501.6  215.31
#Mann= 6 ,-1 , 0
  4564.3     .05       0  4566.1     .12       0  4678.1     .07       0
    4972     .05       0    4976      .1       0  5288.9     .12       0
Bank Sta=4972,4976
XS Rating Curve= 0 ,0
Exp/Cntr=0.3,0.1

Chan Stop Cuts=-1
Use User Specified Reach Order=0
Composite Channel Slope=5