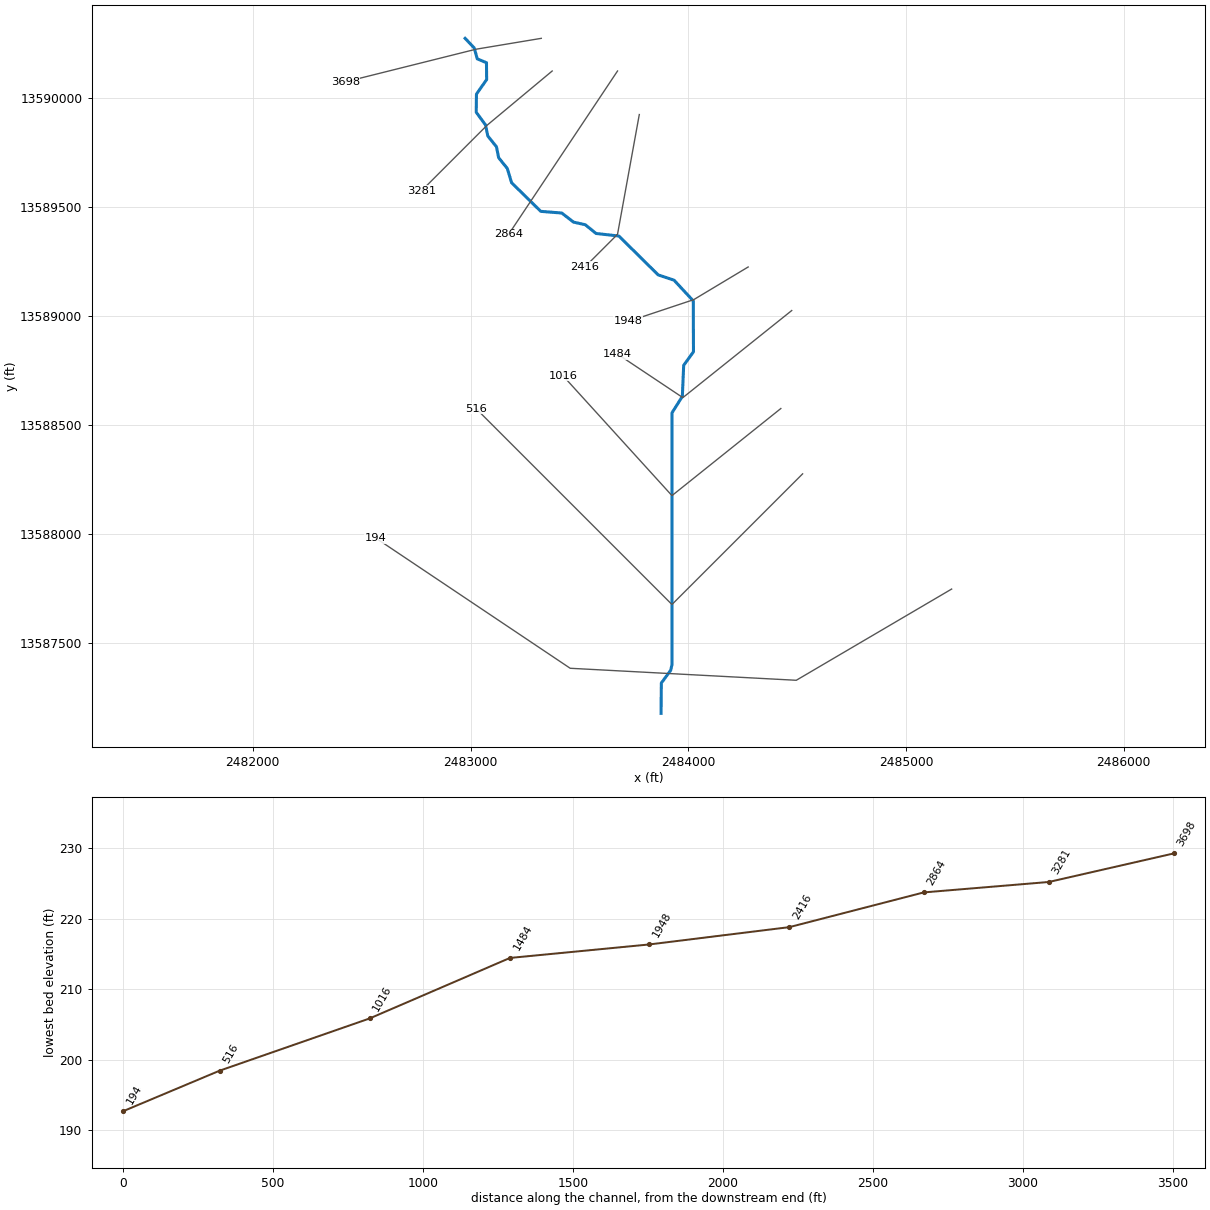
--- Stream0845.prj (project) ---

Proj Title=Stream0845 Base Level Engineering
Current Plan=p01
Default Exp/Contr=0.3,0.1
English Units
Geom File=g01
Flow File=f01
Plan File=p01
BEGIN DESCRIPTION:
Stream0845
END DESCRIPTION:

--- Stream0845.p01 (plan) ---

Plan Title=Multiple Run
Short Identifier=Multiple
Geom File=g01
Flow File=f01
Subcritical Flow
K Sum by GR= 0
Std Step Tol= 0.01
Critical Tol= 0.01
Num of Std Step Trials= 20
Max Error Tol= 0.3
Flow Tol Ratio= 0.001
Split Flow NTrial= 30
Split Flow Tol= 0.02
Split Flow Ratio= 0.02
Log Output Level= 0
Friction Slope Method= 1
Unsteady Friction Slope Method= 2
Unsteady Bridges Friction Slope Method= 1
Parabolic Critical Depth
Global Vel Dist=  1 , 1 , 1
Global Log Level= 0
CheckData=True
Encroach Param= -1, 0, 0, 0
BEGIN DESCRIPTION:
Multiple Run
END DESCRIPTION:

--- Stream0845.f01 (steady flow) ---

Flow Title=Multiple
Number of Profiles=7
Profile Names=10-year,25-year,50-year,1pct_min,100-year,1pct_plu,500-year
River Rch & RM= Stream0845,Reach-1,3698
     442     700     930     599    1196    2386    1957
Boundary for River Rch & Prof#=Stream0845,Reach-1,1
Up Type=0
Dn Type=3
Dn Slope=0.005
Boundary for River Rch & Prof#=Stream0845,Reach-1,2
Up Type=0
Dn Type=3
Dn Slope=0.005
Boundary for River Rch & Prof#=Stream0845,Reach-1,3
Up Type=0
Dn Type=3
Dn Slope=0.005
Boundary for River Rch & Prof#=Stream0845,Reach-1,4
Up Type=0
Dn Type=3
Dn Slope=0.005
Boundary for River Rch & Prof#=Stream0845,Reach-1,5
Up Type=0
Dn Type=3
Dn Slope=0.005
Boundary for River Rch & Prof#=Stream0845,Reach-1,6
Up Type=0
Dn Type=3
Dn Slope=0.005
Boundary for River Rch & Prof#=Stream0845,Reach-1,7
Up Type=0
Dn Type=3
Dn Slope=0.005

--- Stream0845.g01 (geometry) ---

Geom Title=Existing Conditions

River Reach=Stream0845,Reach-1
Reach XY= 30
      2482975.00     13590275.00      2483016.96     13590230.73
      2483030.93     13590180.70      2483073.22     13590163.03
      2483073.93     13590085.65      2483027.17     13590019.03
      2483026.09     13589935.54      2483068.88     13589877.18
      2483079.16     13589826.72      2483118.92     13589777.20
      2483129.16     13589726.72      2483168.90     13589677.19
      2483188.62     13589611.78      2483322.57     13589480.52
      2483419.03     13589472.67      2483472.82     13589431.11
      2483527.18     13589418.89      2483576.59     13589378.83
      2483681.17     13589367.14      2483861.79     13589188.63
      2483934.70     13589164.23      2484022.95     13589069.16
      2484023.78     13588835.50      2483978.79     13588773.43
      2483972.73     13588630.94      2483925.07     13588554.97
      2483925.20     13587399.92      2483919.26     13587372.66
      2483876.17     13587314.52      2483875.00     13587175.00

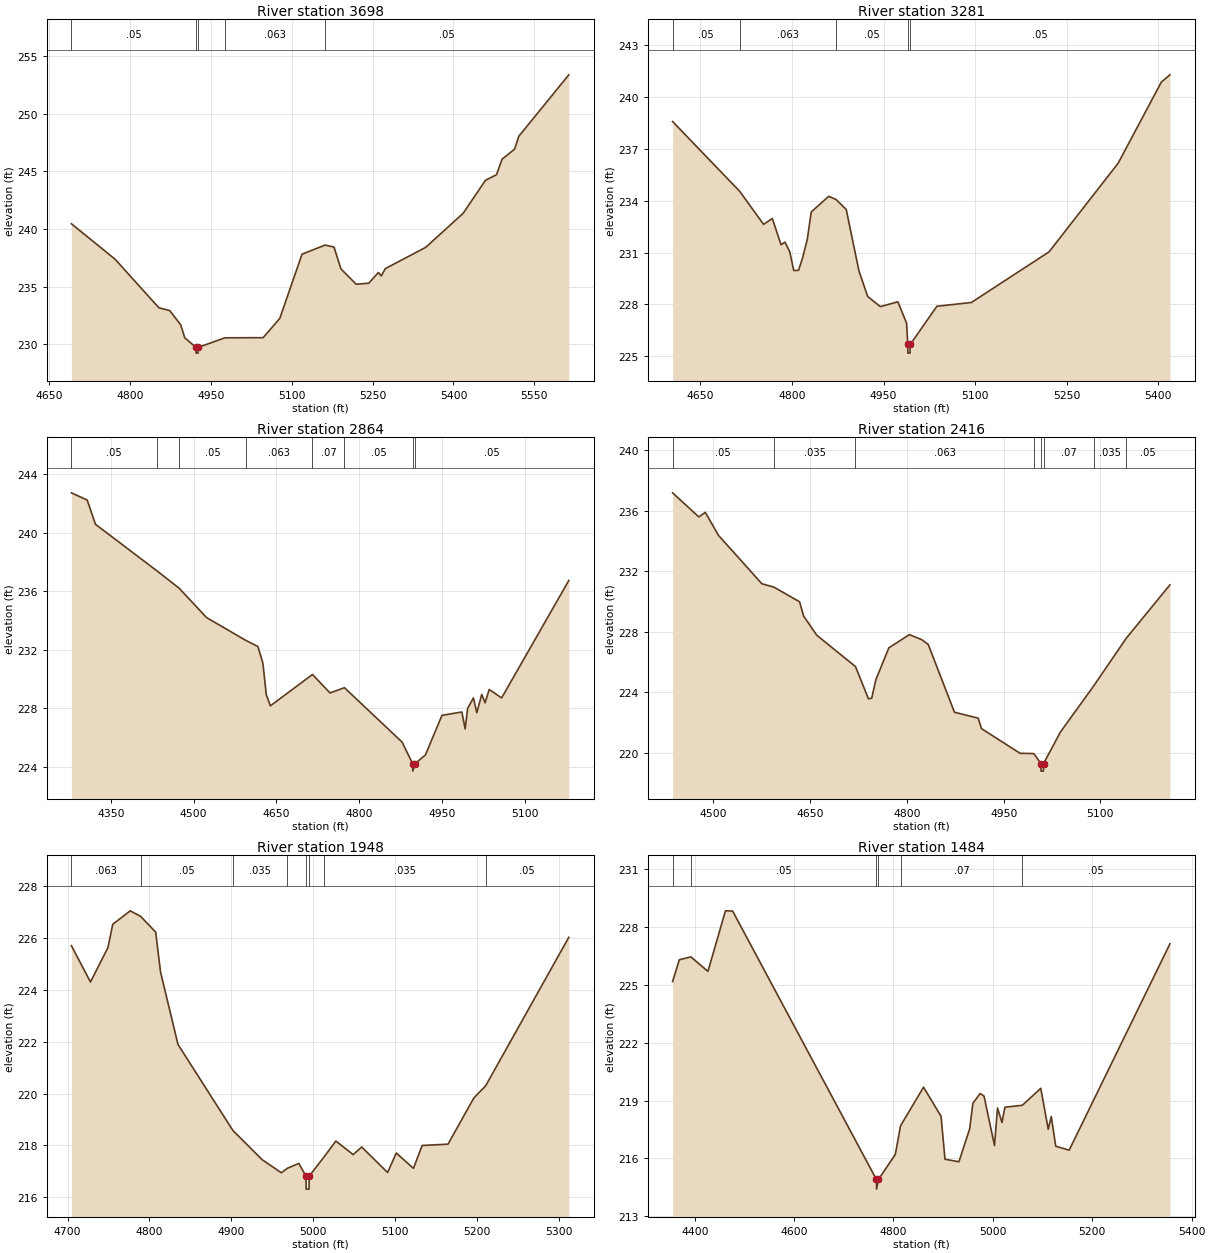
Type RM Length L Ch R = 1,3698,417,417,417
BEGIN DESCRIPTION:
Stream0845 8.0
END DESCRIPTION:
XS GIS Cut Line= 3
      2483324.97     13590275.00      2483025.00     13590225.00
      2482424.97     13590074.99
#Sta/Elev= 30
  4691.3  240.46  4772.4  237.38  4853.5  233.17  4873.8  232.92  4894.0  231.69
  4901.6  230.56  4922.4  229.73  4922.7  229.23  4926.2  229.23  4926.4  229.73
  4976.1  230.56  5046.9  230.57  5077.9  232.25  5119.1  237.82  5161.8  238.61
  5178.4  238.44  5191.3  236.54  5219.6  235.21  5242.8  235.30  5260.8  236.23
  5266.0  235.93  5273.7  236.57  5348.4  238.41  5418.0  241.37  5459.3  244.23
  5479.9  244.72  5490.2  246.07  5513.4  246.94  5521.1  248.05  5613.9  253.39
#Mann=5,-1,0
  4691.3    0.05       0  4922.4    0.05       0  4926.4    0.05       0
  4976.1   0.063       0  5161.8    0.05       0
Bank Sta=4922.4,4926.4
Exp/Cntr=0.3,0.1

Type RM Length L Ch R = 1,3281,417,417,417
BEGIN DESCRIPTION:
Stream0845 7.0
END DESCRIPTION:
XS GIS Cut Line= 3
      2483375.03     13590125.02      2483075.00     13589875.00
      2482775.01     13589575.01
#Sta/Elev= 30
  4604.4  238.58  4714.4  234.54  4753.5  232.63  4767.8  232.97  4782.1  231.45
  4788.6  231.60  4796.4  231.04  4802.9  229.96  4810.8  229.97  4817.3  230.68
  4825.1  231.76  4831.6  233.35  4860.2  234.25  4872.2  234.07  4888.9  233.49
  4909.7  229.94  4924.0  228.46  4944.8  227.87  4973.5  228.15  4987.8  226.91
  4989.7  225.68  4989.9  225.18  4993.4  225.18  4993.7  225.68  5037.4  227.89
  5093.9  228.11  5221.2  231.04  5334.4  236.17  5405.1  240.86  5419.2  241.28
#Mann=5,-1,0
  4604.4    0.05       0  4714.4   0.063       0  4872.2    0.05       0
  4989.7    0.05       0  4993.7    0.05       0
Bank Sta=4989.7,4993.7
Exp/Cntr=0.3,0.1

Type RM Length L Ch R = 1,2864,448,448,448
BEGIN DESCRIPTION:
Stream0845 6.0
END DESCRIPTION:
XS GIS Cut Line= 3
      2483675.01     13590125.02      2483275.00     13589525.00
      2483175.00     13589375.01
#Sta/Elev= 30
  4278.6  242.71  4307.2  242.22  4322.2  240.56  4433.3  237.39  4474.0  236.19
  4523.5  234.19  4594.7  232.63  4616.6  232.21  4625.7  231.06  4631.7  228.93
  4639.2  228.16  4715.5  230.30  4747.3  229.04  4773.4  229.40  4878.0  225.68
  4897.1  224.20  4897.3  223.70  4901.1  224.20  4920.1  224.80  4950.2  227.51
  4986.2  227.74  4992.2  226.58  4996.7  227.99  5007.2  228.70  5013.3  227.69
  5022.3  228.94  5028.3  228.37  5035.8  229.28  5058.3  228.70  5180.0  236.72
#Mann=8,-1,0
  4278.6    0.05       0  4433.3   0.035       0  4474.0    0.05       0
  4594.7   0.063       0  4715.5    0.07       0  4773.4    0.05       0
  4897.1    0.05       0  4901.1    0.05       0
Bank Sta=4897.1,4901.1
Exp/Cntr=0.3,0.1

Type RM Length L Ch R = 1,2416,468,468,468
BEGIN DESCRIPTION:
Stream0845 5.0
END DESCRIPTION:
XS GIS Cut Line= 3
      2483775.00     13589925.02      2483675.00     13589375.00
      2483524.98     13589224.98
#Sta/Elev= 30
  4436.6  237.17  4477.3  235.58  4487.4  235.88  4507.8  234.36  4575.1  231.16
  4593.7  230.94  4633.5  229.97  4639.9  229.02  4660.2  227.76  4720.2  225.69
  4740.3  223.56  4745.4  223.60  4751.7  224.81  4772.0  226.93  4803.8  227.80
  4822.9  227.47  4833.0  227.15  4873.7  222.67  4910.5  222.28  4915.6  221.59
  4975.3  219.96  4996.7  219.94  5007.8  219.28  5008.0  218.78  5011.5  218.78
  5011.8  219.28  5038.1  221.37  5089.4  224.40  5140.2  227.57  5207.8  231.09
#Mann=8,-1,0
  4436.6    0.05       0  4593.7   0.035       0  4720.2   0.063       0
  4996.7    0.07       0  5007.8    0.05       0  5011.8    0.07       0
  5089.4   0.035       0  5140.2    0.05       0
Bank Sta=5007.8,5011.8
Exp/Cntr=0.3,0.1

Type RM Length L Ch R = 1,1948,464,464,464
BEGIN DESCRIPTION:
Stream0845 4.0
END DESCRIPTION:
XS GIS Cut Line= 3
      2484275.01     13589225.00      2484025.00     13589075.00
      2483724.98     13588974.99
#Sta/Elev= 30
  4704.6  225.69  4727.9  224.29  4749.3  225.62  4755.1  226.51  4776.5  227.03
  4789.1  226.82  4807.6  226.21  4813.5  224.68  4834.8  221.89  4901.9  218.58
  4937.8  217.45  4961.2  216.95  4968.4  217.12  4982.5  217.31  4991.2  216.82
  4991.5  216.32  4995.0  216.32  4995.2  216.82  5013.1  217.55  5027.8  218.17
  5048.9  217.65  5059.4  217.94  5091.0  216.96  5101.6  217.71  5122.6  217.12
  5133.2  218.00  5164.8  218.05  5196.4  219.83  5210.7  220.29  5312.4  226.01
#Mann=8,-1,0
  4704.6   0.063       0  4789.1    0.05       0  4901.9   0.035       0
  4968.4    0.07       0  4991.2    0.05       0  4995.2    0.07       0
  5013.1   0.035       0  5210.7    0.05       0
Bank Sta=4991.2,4995.2
Exp/Cntr=0.3,0.1

Type RM Length L Ch R = 1,1484,468,468,468
BEGIN DESCRIPTION:
Stream0845 3.0
END DESCRIPTION:
XS GIS Cut Line= 3
      2484474.97     13589024.97      2483975.00     13588625.00
      2483675.02     13588824.99
#Sta/Elev= 30
  4355.5  225.18  4369.1  226.31  4392.3  226.46  4426.7  225.71  4461.9  228.85
  4476.3  228.84  4765.7  214.91  4765.9  214.41  4769.7  214.91  4803.7  216.21
  4814.3  217.70  4860.5  219.70  4895.7  218.19  4903.7  215.96  4931.7  215.83
  4953.3  217.54  4959.8  218.86  4974.2  219.37  4982.2  219.24  5003.3  216.67
  5009.3  218.62  5018.3  217.87  5024.3  218.66  5059.2  218.76  5096.4  219.64
  5111.4  217.52  5117.5  218.18  5126.5  216.64  5153.5  216.43  5356.3  227.14
#Mann=6,-1,0
  4355.5   0.063       0  4392.3    0.05       0  4765.7    0.05       0
  4769.7    0.05       0  4814.3    0.07       0  5059.2    0.05       0
Bank Sta=4765.7,4769.7
Exp/Cntr=0.3,0.1

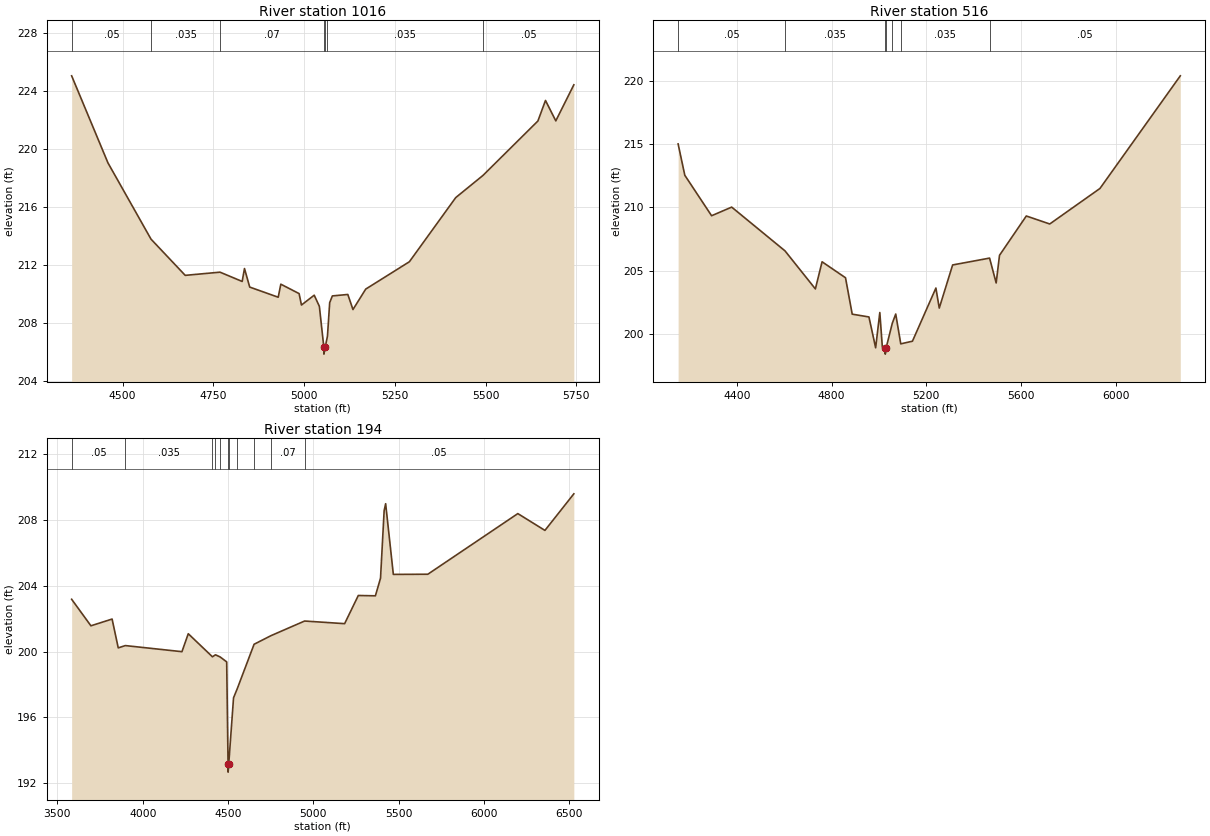
Type RM Length L Ch R = 1,1016,500,500,500
BEGIN DESCRIPTION:
Stream0845 2.0
END DESCRIPTION:
XS GIS Cut Line= 3
      2484424.98     13588574.99      2483925.00     13588175.00
      2483425.00     13588725.00
#Sta/Elev= 30
  4359.7  225.05  4459.7  219.04  4578.4  213.77  4672.6  211.27  4768.5  211.49
  4829.5  210.85  4835.9  211.74  4850.3  210.46  4928.8  209.76  4936.0  210.66
  4986.4  210.01  4992.8  209.22  5028.0  209.90  5042.2  209.13  5054.4  206.33
  5054.7  205.83  5058.4  206.33  5064.5  207.07  5070.6  209.38  5078.0  209.85
  5120.6  209.95  5134.8  208.91  5169.9  210.32  5290.2  212.21  5417.9  216.64
  5492.9  218.17  5644.3  221.93  5665.2  223.35  5693.6  221.94  5743.3  224.43
#Mann=7,-1,0
  4359.7    0.05       0  4578.4   0.035       0  4768.5    0.07       0
  5054.4    0.05       0  5058.4    0.07       0  5064.5   0.035       0
  5492.9    0.05       0
Bank Sta=5054.4,5058.4
Exp/Cntr=0.3,0.1

Type RM Length L Ch R = 1,516,322,322,322
BEGIN DESCRIPTION:
Stream0845 1.0
END DESCRIPTION:
XS GIS Cut Line= 3
      2484524.99     13588274.99      2483925.00     13587675.00
      2483025.00     13588575.00
#Sta/Elev= 30
  4151.5  215.00  4179.8  212.53  4292.9  209.34  4377.8  210.02  4603.0  206.57
  4731.3  203.57  4759.6  205.71  4858.6  204.45  4886.9  201.58  4957.6  201.36
  4985.9  198.93  5003.5  201.71  5014.2  198.99  5026.3  198.93  5026.5  198.43
  5030.3  198.93  5056.2  200.86  5070.7  201.59  5092.0  199.24  5141.4  199.45
  5240.4  203.64  5254.6  202.06  5311.1  205.46  5467.2  206.00  5495.0  204.04
  5509.1  206.22  5622.3  209.32  5721.3  208.69  5933.4  211.49  6272.8  220.37
#Mann=7,-1,0
  4151.5    0.05       0  4603.0   0.035       0  5026.3   0.035       0
  5030.3   0.035       0  5056.2    0.05       0  5092.0   0.035       0
  5467.2    0.05       0
Bank Sta=5026.3,5030.3
Exp/Cntr=0.3,0.1

Type RM Length L Ch R = 1,194,0,0,0
BEGIN DESCRIPTION:
XS7826
END DESCRIPTION:
XS GIS Cut Line= 4
      2485209.36     13587745.96      2484495.87     13587326.98
      2483457.64     13587382.12      2482564.36     13587980.53
#Sta/Elev= 30
  3583.8  203.17  3696.7  201.56  3820.8  201.97  3856.8  200.22  3898.2  200.36
  4230.0  199.99  4267.1  201.08  4408.6  199.68  4426.6  199.80  4453.8  199.67
  4492.2  199.37  4500.2  193.18  4500.5  192.68  4504.2  193.18  4532.3  197.19
  4554.0  197.74  4652.7  200.44  4751.3  200.96  4948.6  201.85  5183.2  201.69
  5263.3  203.40  5363.4  203.38  5393.5  204.45  5414.7  208.55  5423.5  208.97
  5468.6  204.68  5670.7  204.69  6198.0  208.37  6356.8  207.35  6526.1  209.57
#Mann=11,-1,0
  3583.8    0.05       0  3898.2   0.035       0  4408.6    0.12       0
  4426.6   0.035       0  4453.8    0.05       0  4500.2    0.05       0
  4504.2    0.05       0  4554.0    0.12       0  4652.7   0.035       0
  4751.3    0.07       0  4948.6    0.05       0
Bank Sta=4500.2,4504.2
Exp/Cntr=0.3,0.1

Chan Stop Cuts=-1