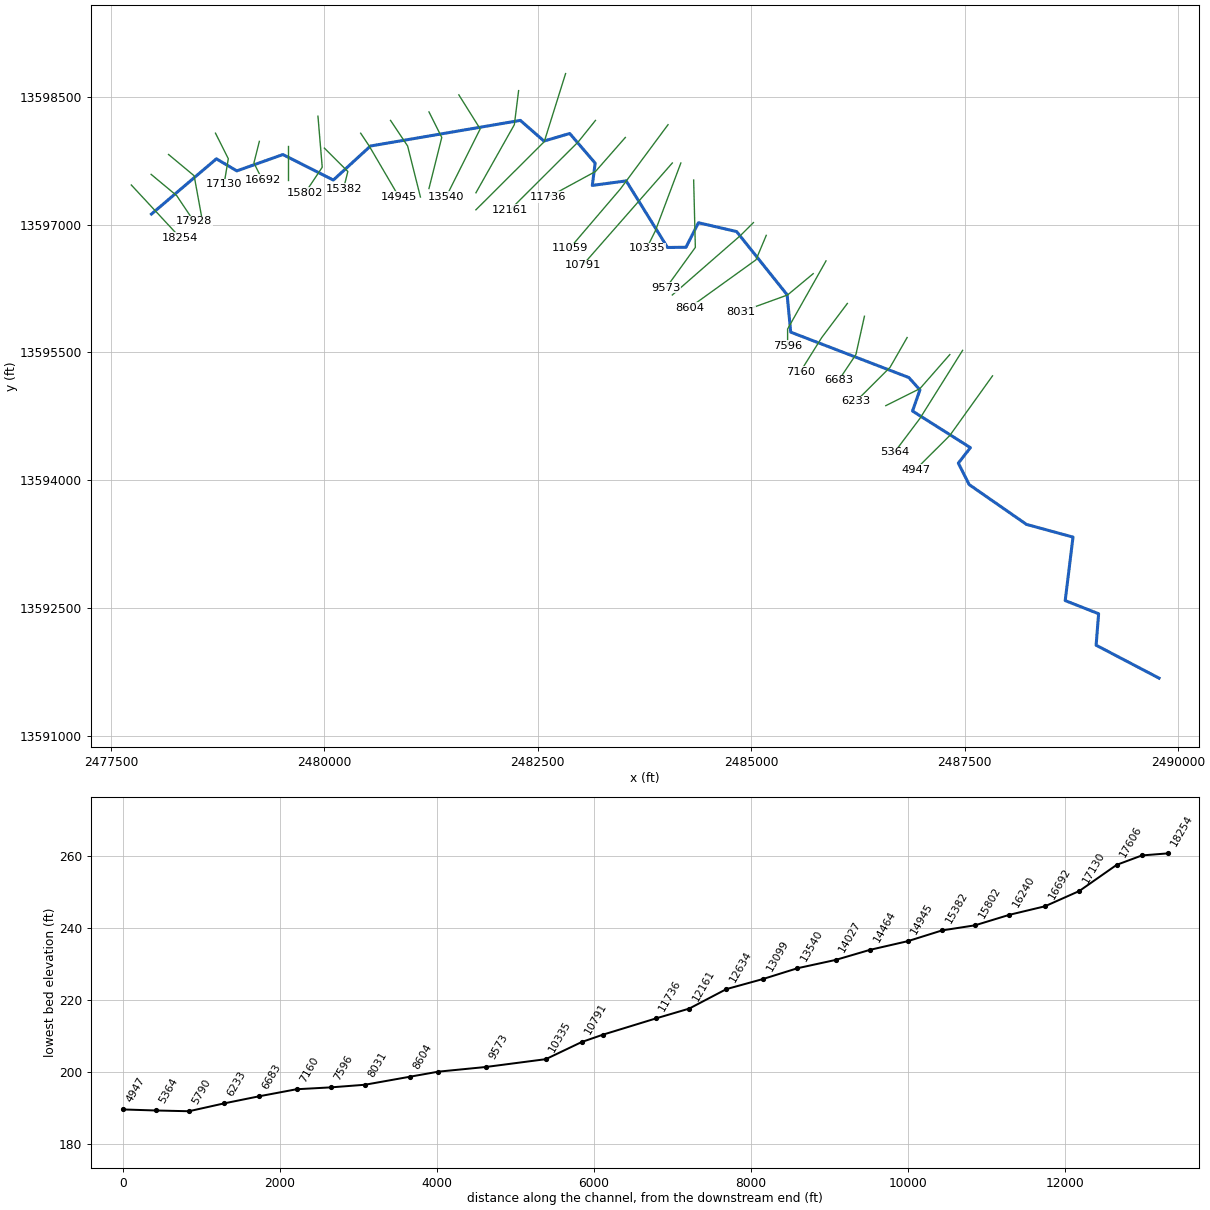
--- Stream0846.prj (project) ---

Proj Title=Stream0846 Base Level Engineering
Current Plan=p01
Default Exp/Contr=0.3,0.1
English Units
Geom File=g01
Flow File=f01
Plan File=p01
BEGIN DESCRIPTION:
Stream0846
END DESCRIPTION:

--- Stream0846.p01 (plan) ---

Plan Title=Multiple Run
Short Identifier=Multiple
Geom File=g01
Flow File=f01
Subcritical Flow
K Sum by GR= 0
Std Step Tol= 0.01
Critical Tol= 0.01
Num of Std Step Trials= 20
Max Error Tol= 0.3
Flow Tol Ratio= 0.001
Split Flow NTrial= 30
Split Flow Tol= 0.02
Split Flow Ratio= 0.02
Log Output Level= 0
Friction Slope Method= 1
Unsteady Friction Slope Method= 2
Unsteady Bridges Friction Slope Method= 1
Parabolic Critical Depth
Global Vel Dist=  1 , 1 , 1
Global Log Level= 0
CheckData=True
Encroach Param= -1, 0, 0, 0
BEGIN DESCRIPTION:
Multiple Run
END DESCRIPTION:

--- Stream0846.f01 (steady flow) ---

Flow Title=Multiple
Number of Profiles=7
Profile Names=10-year,25-year,50-year,1pct_min,100-year,1pct_plu,500-year
River Rch & RM= Stream0846,Reach-1,18254
     568     913    1225     797    1590    3173    2653
River Rch & RM= Stream0846,Reach-1,15382
     976    1609    2193    1445    2884    5754    4942
River Rch & RM= Stream0846,Reach-1,7596
    1304    2176    2990    1984    3959    7900    6884
Boundary for River Rch & Prof#=Stream0846,Reach-1,1
Up Type=0
Dn Type=3
Dn Slope=0.005
Boundary for River Rch & Prof#=Stream0846,Reach-1,2
Up Type=0
Dn Type=3
Dn Slope=0.005
Boundary for River Rch & Prof#=Stream0846,Reach-1,3
Up Type=0
Dn Type=3
Dn Slope=0.005
Boundary for River Rch & Prof#=Stream0846,Reach-1,4
Up Type=0
Dn Type=3
Dn Slope=0.005
Boundary for River Rch & Prof#=Stream0846,Reach-1,5
Up Type=0
Dn Type=3
Dn Slope=0.005
Boundary for River Rch & Prof#=Stream0846,Reach-1,6
Up Type=0
Dn Type=3
Dn Slope=0.005
Boundary for River Rch & Prof#=Stream0846,Reach-1,7
Up Type=0
Dn Type=3
Dn Slope=0.005

--- Stream0846.g01 (geometry) ---

Geom Title=Existing Conditions

River Reach=Stream0846,Reach-1
Reach XY= 30
      2477975.00     13597125.00      2478735.44     13597773.95
      2478974.66     13597632.22      2479514.29     13597824.28
      2480104.83     13597524.53      2480540.64     13597924.58
      2482295.21     13598225.36      2482571.66     13597982.60
      2482873.55     13598071.47      2483171.47     13597723.53
      2483138.11     13597461.76      2483534.68     13597514.83
      2484018.81     13596732.81      2484235.18     13596735.32
      2484381.04     13597023.43      2484827.70     13596919.64
      2485419.54     13596177.45      2485461.65     13595738.36
      2486845.09     13595205.22      2486974.76     13595059.78
      2486888.11     13594811.79      2487566.05     13594381.69
      2487424.68     13594200.11      2487551.53     13593948.01
      2488222.55     13593480.46      2488767.64     13593331.34
      2488676.19     13592585.50      2489067.64     13592431.43
      2489038.36     13592061.65      2489775.00     13591675.00

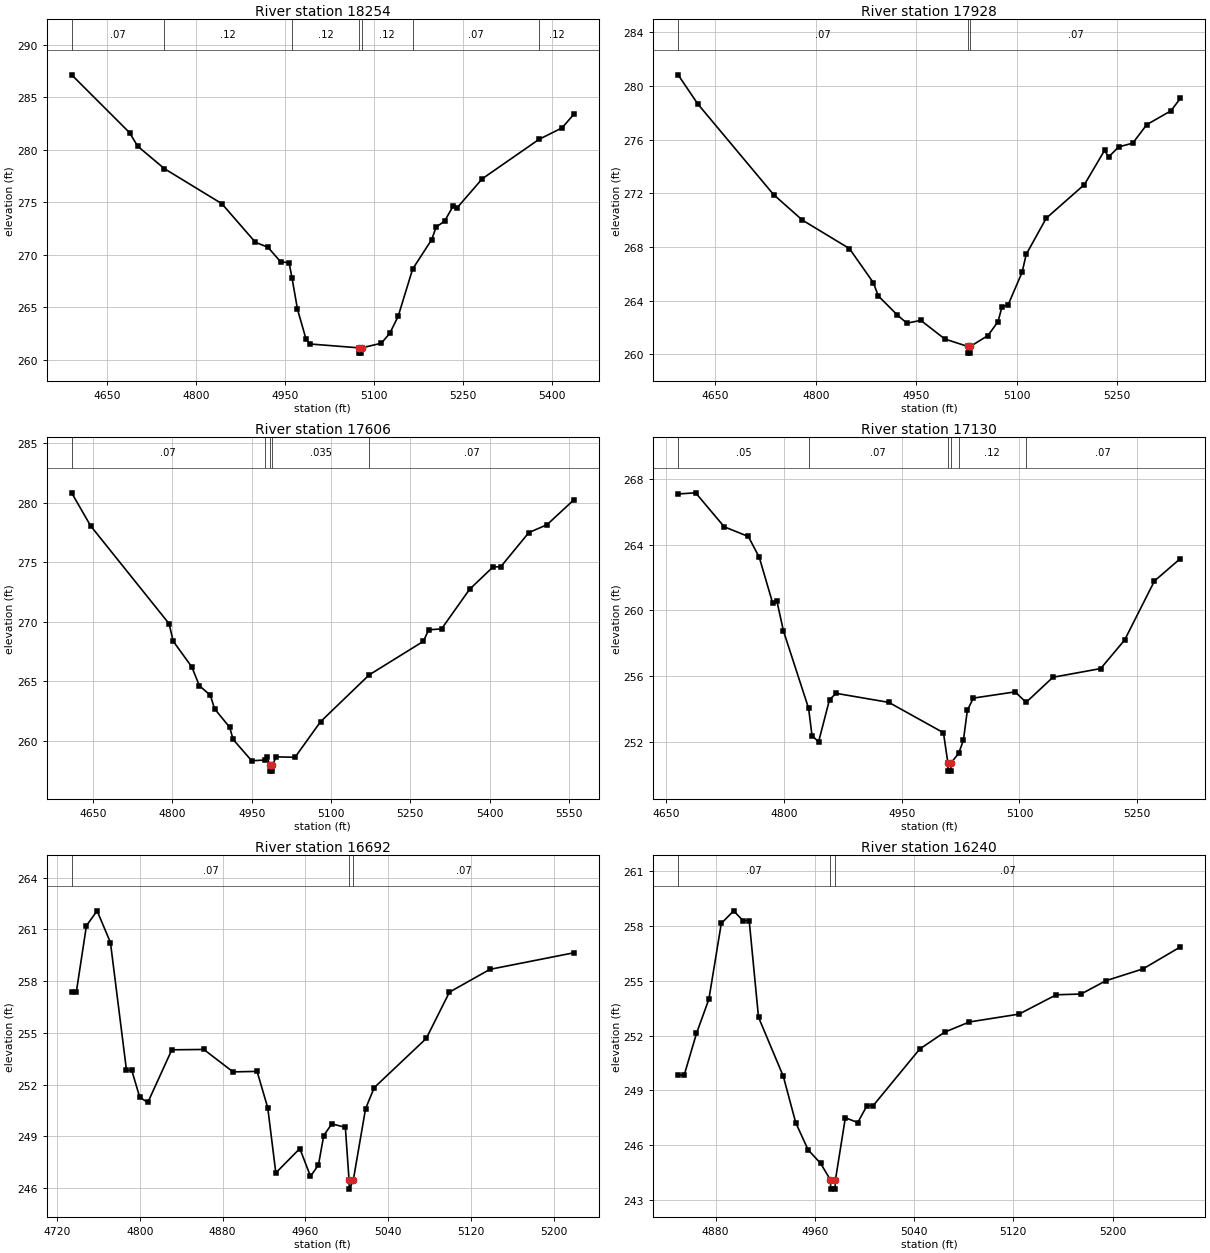
Type RM Length L Ch R = 1,18254,326,326,326
BEGIN DESCRIPTION:
XS7828
END DESCRIPTION:
XS GIS Cut Line= 2
      2477739.00     13597466.55      2478313.93     13596845.79
#Sta/Elev= 30
  4590.8  287.13  4688.3  281.63  4702.0  280.34  4747.1  278.20  4843.8  274.87
  4900.5  271.19  4921.4  270.73  4943.0  269.33  4957.1  269.26  4962.1  267.80
  4971.3  264.82  4985.5  262.02  4992.3  261.52  5075.3  261.15  5075.6  260.65
  5079.1  260.65  5079.3  261.15  5112.5  261.59  5126.7  262.53  5140.9  264.15
  5165.3  268.65  5197.5  271.46  5204.9  272.65  5219.1  273.20  5233.3  274.62
  5240.1  274.47  5282.6  277.24  5378.5  281.00  5417.0  282.08  5436.9  283.38
#Mann=7,-1,0
  4590.8    0.07       0  4747.1    0.12       0  4962.1    0.12       0
  5075.3    0.05       0  5079.3    0.12       0  5165.3    0.07       0
  5378.5    0.12       0
Bank Sta=5075.3,5079.3
Exp/Cntr=0.3,0.1

Type RM Length L Ch R = 1,17928,322,322,322
BEGIN DESCRIPTION:
Stream0846 36.0
END DESCRIPTION:
XS GIS Cut Line= 3
      2477970.82     13597591.65      2478270.82     13597341.65
      2478470.39     13597042.29
#Sta/Elev= 30
  4594.2  280.82  4623.6  278.65  4736.8  271.90  4779.8  270.00  4850.1  267.88
  4886.0  265.33  4893.1  264.36  4921.7  262.93  4936.0  262.32  4956.8  262.53
  4992.7  261.14  5026.8  260.59  5027.0  260.09  5030.5  260.09  5030.8  260.59
  5057.1  261.40  5072.1  262.43  5078.1  263.54  5087.1  263.67  5108.2  266.12
  5114.2  267.44  5144.2  270.14  5201.3  272.65  5231.3  275.19  5237.4  274.70
  5252.4  275.45  5273.4  275.73  5294.4  277.11  5330.5  278.14  5344.5  279.06
#Mann=3,-1,0
  4594.2    0.07       0  5026.8    0.05       0  5030.8    0.07       0
Bank Sta=5026.8,5030.8
Exp/Cntr=0.3,0.1

Type RM Length L Ch R = 1,17606,476,476,476
BEGIN DESCRIPTION:
Stream0846 35.0
END DESCRIPTION:
XS GIS Cut Line= 3
      2478174.98     13597825.01      2478475.00     13597575.00
      2478574.99     13597025.05
#Sta/Elev= 30
  4609.7  280.84  4645.5  278.07  4793.9  269.85  4801.7  268.38  4836.9  266.22
  4851.2  264.64  4872.0  263.84  4879.8  262.71  4908.5  261.15  4915.0  260.13
  4950.1  258.34  4974.6  258.40  4978.8  258.67  4984.6  257.97  4984.8  257.47
  4988.3  257.47  4988.6  257.97  4997.0  258.67  5032.0  258.63  5080.3  261.62
  5172.2  265.55  5274.7  268.37  5284.8  269.34  5309.0  269.41  5362.3  272.75
  5406.8  274.63  5420.8  274.62  5474.1  277.50  5508.4  278.16  5559.2  280.25
#Mann=5,-1,0
  4609.7    0.07       0  4974.6   0.035       0  4984.6   0.035       0
  4988.6   0.035       0  5172.2    0.07       0
Bank Sta=4984.6,4988.6
Exp/Cntr=0.3,0.1

Type RM Length L Ch R = 1,17130,438,438,438
BEGIN DESCRIPTION:
Stream0846 34.0
END DESCRIPTION:
XS GIS Cut Line= 3
      2478725.01     13598074.97      2478875.00     13597775.00
      2478825.00     13597475.02
#Sta/Elev= 30
  4665.3  267.09  4687.6  267.16  4724.0  265.09  4754.7  264.50  4768.7  263.22
  4785.5  260.47  4791.0  260.58  4799.4  258.75  4831.5  254.02  4835.8  252.36
  4844.2  251.99  4858.1  254.56  4866.5  254.94  4933.6  254.39  5003.2  252.54
  5008.8  250.70  5009.1  250.20  5012.6  250.20  5012.8  250.70  5022.5  251.28
  5028.6  252.08  5033.6  253.90  5041.2  254.65  5094.5  255.03  5108.4  254.39
  5142.6  255.92  5203.4  256.45  5233.9  258.19  5271.9  261.79  5304.8  263.15
#Mann=6,-1,0
  4665.3    0.05       0  4831.5    0.07       0  5008.8    0.05       0
  5012.8    0.07       0  5022.5    0.12       0  5108.4    0.07       0
Bank Sta=5008.8,5012.8
Exp/Cntr=0.3,0.1

Type RM Length L Ch R = 1,16692,452,452,452
BEGIN DESCRIPTION:
Stream0846 33.0
END DESCRIPTION:
XS GIS Cut Line= 4
      2479238.47     13597978.87      2479225.00     13597925.00
      2479175.00     13597725.00      2479275.00     13597524.99
#Sta/Elev= 30
  4734.2  257.36  4738.7  257.36  4748.5  261.21  4758.8  262.07  4771.7  260.23
  4787.2  252.83  4792.3  252.83  4800.0  251.27  4807.8  250.97  4831.0  254.02
  4861.9  254.04  4890.2  252.74  4913.4  252.77  4923.7  250.66  4931.5  246.89
  4954.7  248.30  4965.0  246.69  4972.7  247.35  4977.8  249.05  4985.6  249.73
  4998.7  249.53  5002.3  246.45  5002.5  245.95  5006.3  246.45  5018.2  250.60
  5026.6  251.83  5076.9  254.68  5099.3  257.36  5138.4  258.68  5219.5  259.64
#Mann=3,-1,0
  4734.2    0.07       0  5002.3    0.05       0  5006.3    0.07       0
Bank Sta=5002.3,5006.3
Exp/Cntr=0.3,0.1

Type RM Length L Ch R = 1,16240,438,438,438
BEGIN DESCRIPTION:
Stream0846 32.0
END DESCRIPTION:
XS GIS Cut Line= 4
      2479575.00     13597929.80      2479575.00     13597875.00
      2479575.00     13597775.00      2479575.00     13597525.00
#Sta/Elev= 30
  4849.8  249.84  4854.7  249.84  4864.6  252.12  4874.6  254.00  4884.6  258.15
  4894.6  258.84  4902.1  258.30  4907.1  258.30  4914.6  253.01  4934.6  249.77
  4944.6  247.23  4954.6  245.74  4964.6  245.01  4972.6  244.09  4972.8  243.59
  4976.3  243.59  4976.6  244.09  4984.6  247.50  4994.6  247.24  5002.1  248.17
  5007.1  248.17  5044.6  251.27  5064.6  252.19  5084.6  252.75  5124.6  253.18
  5154.6  254.24  5174.6  254.28  5194.6  255.01  5224.6  255.66  5254.6  256.86
#Mann=3,-1,0
  4849.8    0.07       0  4972.6    0.05       0  4976.6    0.07       0
Bank Sta=4972.6,4976.6
Exp/Cntr=0.3,0.1

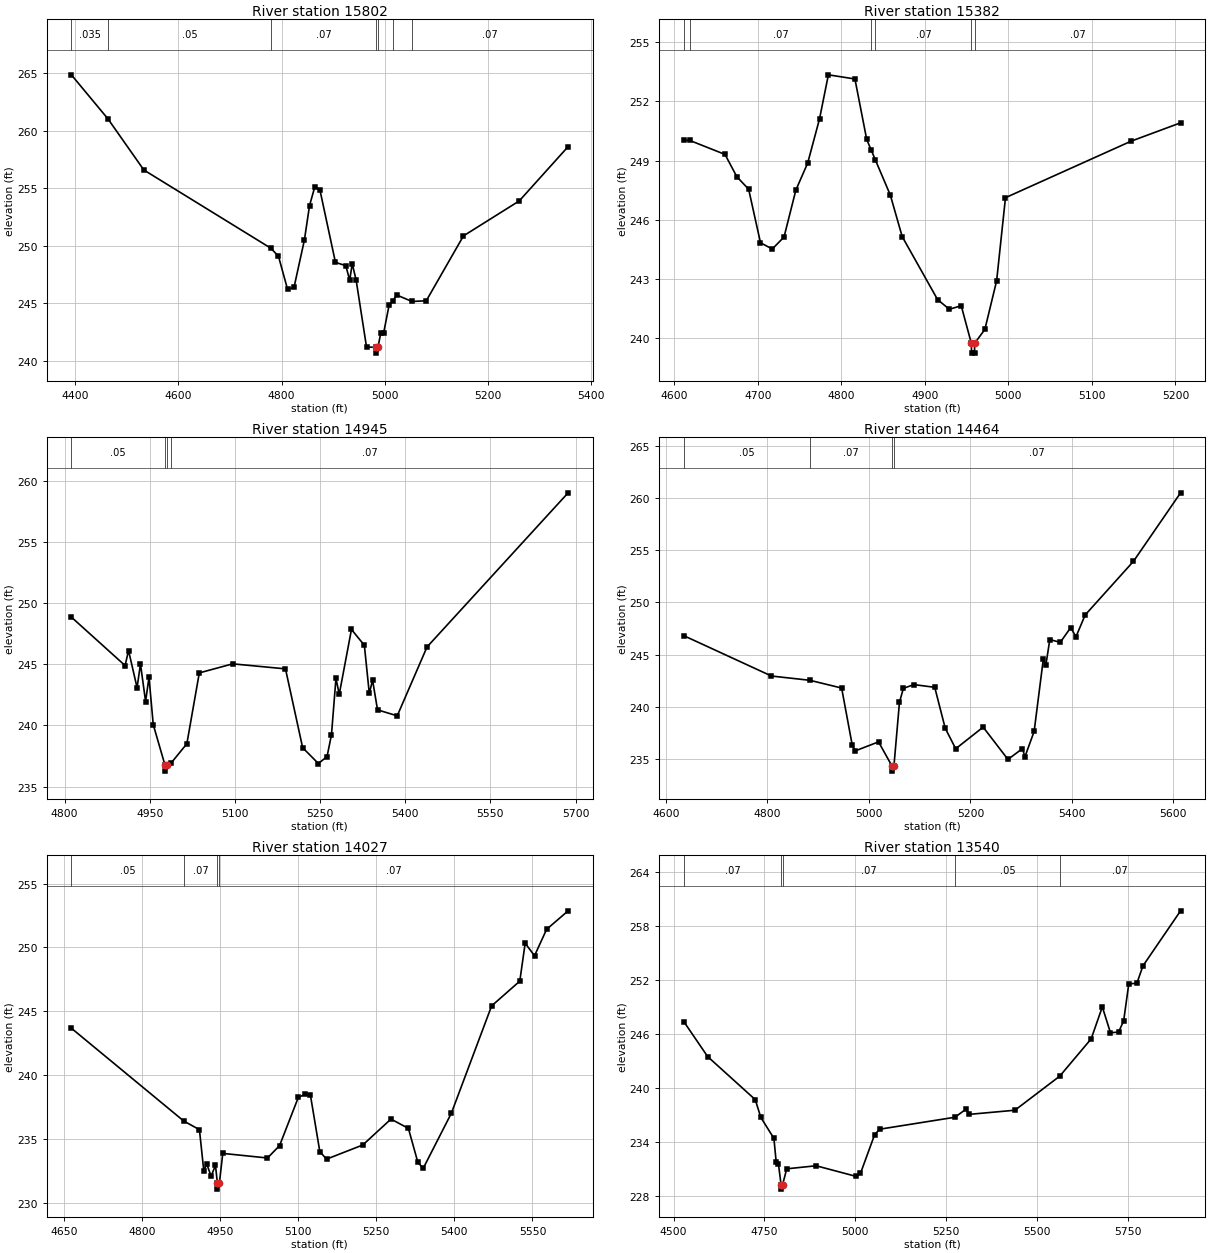
Type RM Length L Ch R = 1,15802,420,420,420
BEGIN DESCRIPTION:
Stream0846 31.0
END DESCRIPTION:
XS GIS Cut Line= 3
      2479925.00     13598274.95      2479975.00     13597675.00
      2479774.99     13597374.99
#Sta/Elev= 30
  4392.7  264.86  4463.6  261.03  4533.1  256.59  4779.2  249.79  4794.0  249.09
  4811.6  246.22  4824.1  246.38  4844.2  250.49  4854.2  253.49  4864.3  255.11
  4874.3  254.86  4904.4  248.56  4924.5  248.27  4932.0  247.01  4937.0  248.44
  4944.6  246.99  4964.6  241.21  4982.7  241.17  4982.9  240.67  4986.7  241.17
  4992.2  242.40  4997.7  242.40  5008.3  244.82  5015.1  245.19  5023.3  245.72
  5052.6  245.16  5080.4  245.22  5152.5  250.86  5260.6  253.90  5355.3  258.62
#Mann=7,-1,0
  4392.7   0.035       0  4463.6    0.05       0  4779.2    0.07       0
  4982.7    0.05       0  4986.7    0.07       0  5015.1    0.12       0
  5052.6    0.07       0
Bank Sta=4982.7,4986.7
Exp/Cntr=0.3,0.1

Type RM Length L Ch R = 1,15382,437,437,437
BEGIN DESCRIPTION:
Stream0846 30.0
END DESCRIPTION:
XS GIS Cut Line= 4
      2480000.12     13597899.88      2480125.00     13597775.00
      2480275.00     13597625.00      2480225.00     13597425.00
#Sta/Elev= 30
  4611.3  250.02  4618.3  250.02  4660.6  249.31  4674.8  248.18  4688.9  247.55
  4703.1  244.84  4717.2  244.52  4731.3  245.13  4745.5  247.51  4759.6  248.87
  4773.8  251.11  4784.4  253.34  4816.2  253.13  4830.3  250.07  4835.5  249.55
  4840.8  249.02  4858.6  247.25  4872.8  245.15  4915.2  241.96  4929.3  241.47
  4943.5  241.65  4955.6  239.75  4955.9  239.25  4959.4  239.25  4959.6  239.75
  4971.8  240.45  4985.9  242.91  4996.5  247.12  5146.9  249.98  5206.2  250.91
#Mann=6,-1,0
  4611.3    0.05       0  4618.3    0.07       0  4835.5    0.12       0
  4840.8    0.07       0  4955.6    0.05       0  4959.6    0.07       0
Bank Sta=4955.6,4959.6
Exp/Cntr=0.3,0.1

Type RM Length L Ch R = 1,14945,481,481,481
BEGIN DESCRIPTION:
Stream0846 29.0
END DESCRIPTION:
XS GIS Cut Line= 3
      2480425.00     13598075.00      2480525.00     13597925.00
      2480875.00     13597325.00
#Sta/Elev= 30
  4812.0  248.85  4906.6  244.89  4912.7  246.12  4927.7  243.08  4933.7  245.02
  4942.7  241.95  4948.7  243.93  4956.2  240.06  4976.8  236.76  4977.0  236.26
  4980.8  236.76  4988.0  236.94  5015.4  238.50  5037.3  244.29  5096.1  245.03
  5189.1  244.62  5219.3  238.18  5247.0  236.88  5262.3  237.45  5270.1  239.23
  5278.0  243.85  5283.8  242.54  5305.3  247.84  5328.0  246.55  5336.7  242.62
  5342.5  243.69  5351.2  241.27  5385.9  240.78  5438.4  246.41  5686.9  259.01
#Mann=4,-1,0
  4812.0    0.05       0  4976.8    0.05       0  4980.8    0.05       0
  4988.0    0.07       0
Bank Sta=4976.8,4980.8
Exp/Cntr=0.3,0.1

Type RM Length L Ch R = 1,14464,437,437,437
BEGIN DESCRIPTION:
Stream0846 28.0
END DESCRIPTION:
XS GIS Cut Line= 3
      2480775.01     13598224.98      2480975.00     13597925.00
      2481125.00     13597325.00
#Sta/Elev= 30
  4635.2  246.81  4807.9  242.95  4883.7  242.54  4946.2  241.80  4967.2  236.31
  4973.2  235.79  5018.9  236.65  5045.3  234.35  5045.5  233.85  5049.3  234.35
  5060.2  240.45  5067.9  241.77  5088.5  242.13  5129.7  241.87  5150.3  237.96
  5171.0  235.99  5225.1  238.06  5274.0  234.97  5302.4  236.00  5307.5  235.23
  5325.6  237.65  5343.6  244.54  5348.8  244.03  5356.5  246.44  5377.1  246.17
  5397.7  247.59  5408.0  246.70  5426.1  248.79  5521.4  253.93  5614.2  260.48
#Mann=4,-1,0
  4635.2    0.05       0  4883.7    0.07       0  5045.3    0.05       0
  5049.3    0.07       0
Bank Sta=5045.3,5049.3
Exp/Cntr=0.3,0.1

Type RM Length L Ch R = 1,14027,487,487,487
BEGIN DESCRIPTION:
Stream0846 27.0
END DESCRIPTION:
XS GIS Cut Line= 3
      2481225.01     13598324.98      2481375.00     13598025.00
      2481224.99     13597424.96
#Sta/Elev= 30
  4664.6  243.66  4880.3  236.39  4910.5  235.71  4918.9  232.48  4924.5  233.03
  4932.9  232.06  4941.3  232.92  4944.9  231.55  4945.1  231.05  4948.9  231.55
  4955.3  233.85  5041.2  233.49  5064.4  234.46  5100.5  238.25  5113.4  238.47
  5123.7  238.40  5141.7  233.99  5154.6  233.40  5224.2  234.51  5278.3  236.54
  5311.8  235.81  5329.8  233.17  5340.1  232.67  5394.3  237.00  5471.6  245.41
  5525.7  247.35  5536.0  250.32  5554.0  249.34  5577.2  251.41  5618.5  252.86
#Mann=4,-1,0
  4664.6    0.05       0  4880.3    0.07       0  4944.9    0.05       0
  4948.9    0.07       0
Bank Sta=4944.9,4948.9
Exp/Cntr=0.3,0.1

Type RM Length L Ch R = 1,13540,441,441,441
BEGIN DESCRIPTION:
Stream0846 26.0
END DESCRIPTION:
XS GIS Cut Line= 3
      2481574.99     13598525.02      2481825.00     13598125.00
      2481425.02     13597325.04
#Sta/Elev= 30
  4528.2  247.38  4593.7  243.49  4724.6  238.70  4739.9  236.72  4775.9  234.39
  4782.3  231.71  4788.2  231.59  4795.6  229.24  4795.8  228.74  4799.8  229.24
  4811.2  231.00  4892.0  231.34  5002.7  230.15  5013.9  230.48  5053.0  234.81
  5067.0  235.41  5273.8  236.74  5304.6  237.65  5313.0  237.06  5438.7  237.52
  5561.9  241.31  5648.4  245.46  5679.1  249.02  5701.5  246.14  5723.8  246.22
  5737.8  247.47  5751.8  251.57  5774.2  251.66  5790.9  253.59  5894.3  259.71
#Mann=5,-1,0
  4528.2    0.07       0  4795.6    0.05       0  4799.8    0.07       0
  5273.8    0.05       0  5561.9    0.07       0
Bank Sta=4795.6,4799.8
Exp/Cntr=0.3,0.1

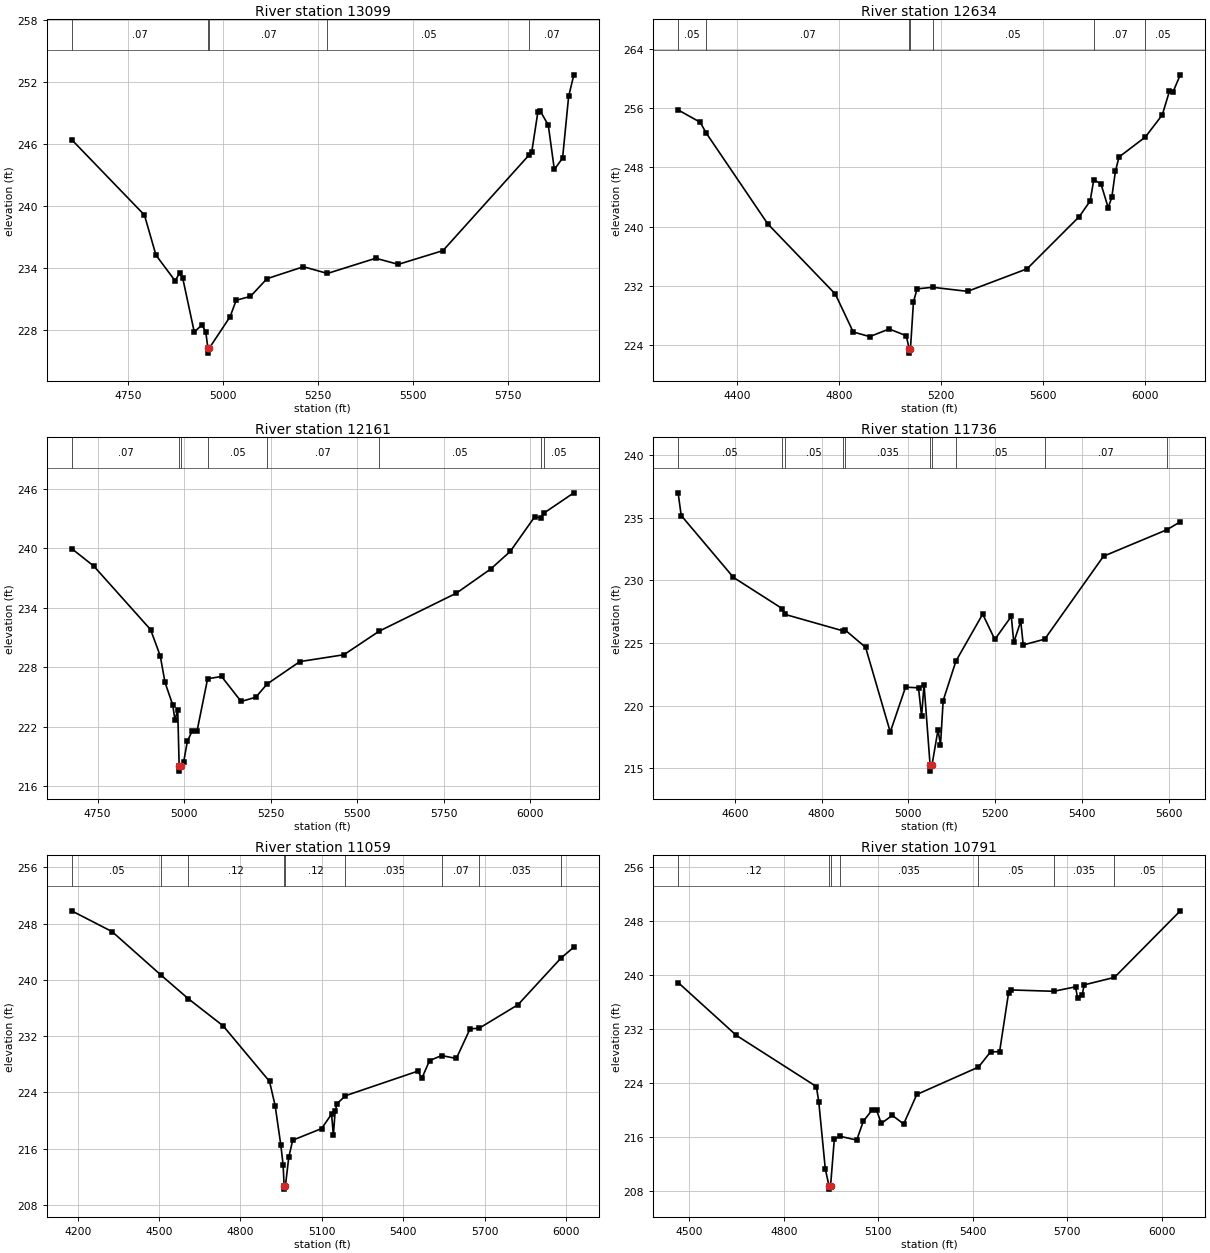
Type RM Length L Ch R = 1,13099,465,465,465
BEGIN DESCRIPTION:
Stream0846 25.0
END DESCRIPTION:
XS GIS Cut Line= 3
      2482275.01     13598575.04      2482225.00     13598175.00
      2481775.02     13597375.03
#Sta/Elev= 30
  4601.8  246.39  4793.3  239.09  4823.6  235.21  4873.9  232.73  4886.5  233.52
  4894.1  232.97  4924.3  227.78  4944.5  228.45  4954.6  227.80  4960.0  226.23
  4960.3  225.73  4964.2  226.23  5018.7  229.26  5034.6  230.85  5072.2  231.22
  5115.5  232.93  5211.5  234.09  5274.6  233.44  5401.7  234.91  5461.0  234.32
  5578.6  235.65  5806.0  244.94  5812.2  245.22  5828.2  249.07  5833.9  249.19
  5855.6  247.79  5871.5  243.50  5893.2  244.61  5909.1  250.57  5922.8  252.66
#Mann=5,-1,0
  4601.8    0.07       0  4960.0    0.05       0  4964.2    0.07       0
  5274.6    0.05       0  5806.0    0.07       0
Bank Sta=4960,4964.2
Exp/Cntr=0.3,0.1

Type RM Length L Ch R = 1,12634,473,473,473
BEGIN DESCRIPTION:
Stream0846 24.0
END DESCRIPTION:
XS GIS Cut Line= 3
      2482825.01     13598775.05      2482575.00     13597975.00
      2481774.98     13597174.98
#Sta/Elev= 30
  4169.6  255.76  4256.1  254.10  4280.0  252.63  4521.1  240.38  4786.2  230.90
  4856.4  225.78  4921.4  225.16  4997.3  226.19  5064.4  225.28  5076.4  223.43
  5076.7  222.93  5080.7  223.43  5092.7  229.86  5106.8  231.60  5167.3  231.82
  5304.8  231.27  5538.1  234.31  5743.2  241.37  5785.6  243.47  5799.8  246.33
  5828.0  245.78  5856.3  242.57  5870.5  243.95  5884.6  247.46  5898.8  249.40
  6002.2  252.11  6068.5  255.09  6096.7  258.30  6110.9  258.22  6139.2  260.50
#Mann=7,-1,0
  4169.6    0.05       0  4280.0    0.07       0  5076.4    0.05       0
  5080.7    0.07       0  5167.3    0.05       0  5799.8    0.07       0
  6002.2    0.05       0
Bank Sta=5076.4,5080.7
Exp/Cntr=0.3,0.1

Type RM Length L Ch R = 1,12161,425,425,425
BEGIN DESCRIPTION:
Stream0846 23.0
END DESCRIPTION:
XS GIS Cut Line= 3
      2483175.03     13598225.03      2482975.00     13597975.00
      2482174.98     13597174.98
#Sta/Elev= 30
  4675.0  239.95  4739.1  238.18  4903.2  231.78  4931.2  229.12  4944.8  226.47
  4967.2  224.19  4973.6  222.67  4981.6  223.69  4985.8  218.02  4986.1  217.52
  4990.2  218.02  4998.7  218.41  5009.3  220.51  5023.5  221.58  5037.6  221.59
  5068.0  226.83  5108.3  227.06  5164.9  224.54  5207.3  224.97  5240.0  226.30
  5334.6  228.56  5461.9  229.25  5564.1  231.63  5787.2  235.46  5886.2  237.89
  5942.7  239.66  6013.4  243.15  6031.0  243.05  6039.0  243.50  6126.6  245.57
#Mann=8,-1,0
  4675.0    0.07       0  4985.8    0.05       0  4990.2    0.07       0
  5068.0    0.05       0  5240.0    0.07       0  5564.1    0.05       0
  6031.0    0.07       0  6039.0    0.05       0
Bank Sta=4985.8,4990.2
Exp/Cntr=0.3,0.1

Type RM Length L Ch R = 1,11736,677,677,677
BEGIN DESCRIPTION:
Stream0846 22.0
END DESCRIPTION:
XS GIS Cut Line= 3
      2483524.98     13598024.97      2483175.00     13597625.00
      2482624.98     13597324.99
#Sta/Elev= 30
  4469.2  236.99  4476.3  235.18  4596.8  230.24  4709.7  227.74  4715.6  227.29
  4849.9  225.97  4854.4  226.04  4901.5  224.66  4958.4  217.90  4993.6  221.48
  5023.5  221.43  5030.6  219.17  5036.3  221.67  5050.2  215.28  5050.5  214.78
  5054.7  215.28  5068.5  218.08  5074.2  216.86  5080.4  220.41  5109.8  223.56
  5171.5  227.31  5199.5  225.29  5237.5  227.13  5243.2  225.06  5259.3  226.74
  5265.0  224.85  5314.5  225.31  5450.1  231.93  5596.7  234.05  5627.2  234.68
#Mann=10,-1,0
  4469.2    0.05       0  4709.7   0.035       0  4715.6    0.05       0
  4849.9    0.12       0  4854.4   0.035       0  5050.2   0.035       0
  5054.7   0.035       0  5109.8    0.05       0  5314.5    0.07       0
  5596.7    0.05       0
Bank Sta=5050.2,5054.7
Exp/Cntr=0.3,0.1

Type RM Length L Ch R = 1,11059,268,268,268
BEGIN DESCRIPTION:
Stream0846 21.0
END DESCRIPTION:
XS GIS Cut Line= 3
      2484024.97     13598174.96      2483467.46     13597420.72
      2482875.02     13596725.02
#Sta/Elev= 30
  4177.6  249.82  4326.8  246.86  4508.0  240.65  4608.4  237.30  4736.0  233.47
  4907.2  225.57  4928.0  222.10  4948.9  216.50  4957.3  213.71  4961.0  210.75
  4961.4  210.25  4966.0  210.75  4978.1  214.78  4992.8  217.21  5099.2  218.86
  5136.0  220.92  5142.6  217.90  5149.3  221.39  5156.9  222.42  5187.2  223.53
  5454.5  227.03  5468.7  225.99  5497.3  228.53  5541.8  229.24  5596.1  228.83
  5646.6  233.04  5679.9  233.12  5823.4  236.47  5982.3  243.12  6029.3  244.65
#Mann=9,-1,0
  4177.6    0.05       0  4508.0    0.07       0  4608.4    0.12       0
  4961.0    0.05       0  4966.0    0.12       0  5187.2   0.035       0
  5541.8    0.07       0  5679.9   0.035       0  5982.3    0.07       0
Bank Sta=4961,4966
Exp/Cntr=0.3,0.1

Type RM Length L Ch R = 1,10791,456,456,456
BEGIN DESCRIPTION:
Stream0846 20.0
END DESCRIPTION:
XS GIS Cut Line= 3
      2484074.98     13597724.98      2483725.00     13597325.00
      2483024.99     13596524.99
#Sta/Elev= 30
  4464.0  238.83  4648.6  231.01  4902.9  223.42  4910.5  221.19  4931.4  211.17
  4943.1  208.72  4943.5  208.22  4948.1  208.72  4959.9  215.61  4977.0  216.06
  5031.1  215.49  5051.9  218.26  5080.4  219.97  5094.7  219.87  5108.9  217.95
  5144.0  219.15  5180.1  217.87  5221.8  222.24  5417.7  226.30  5456.3  228.57
  5484.7  228.57  5513.2  237.30  5519.9  237.73  5656.6  237.53  5725.8  238.19
  5732.5  236.51  5746.7  236.92  5753.3  238.48  5849.5  239.59  6058.5  249.45
#Mann=7,-1,0
  4464.0    0.12       0  4943.1   0.035       0  4948.1    0.12       0
  4977.0   0.035       0  5417.7    0.05       0  5656.6   0.035       0
  5849.5    0.05       0
Bank Sta=4943.1,4948.1
Exp/Cntr=0.3,0.1

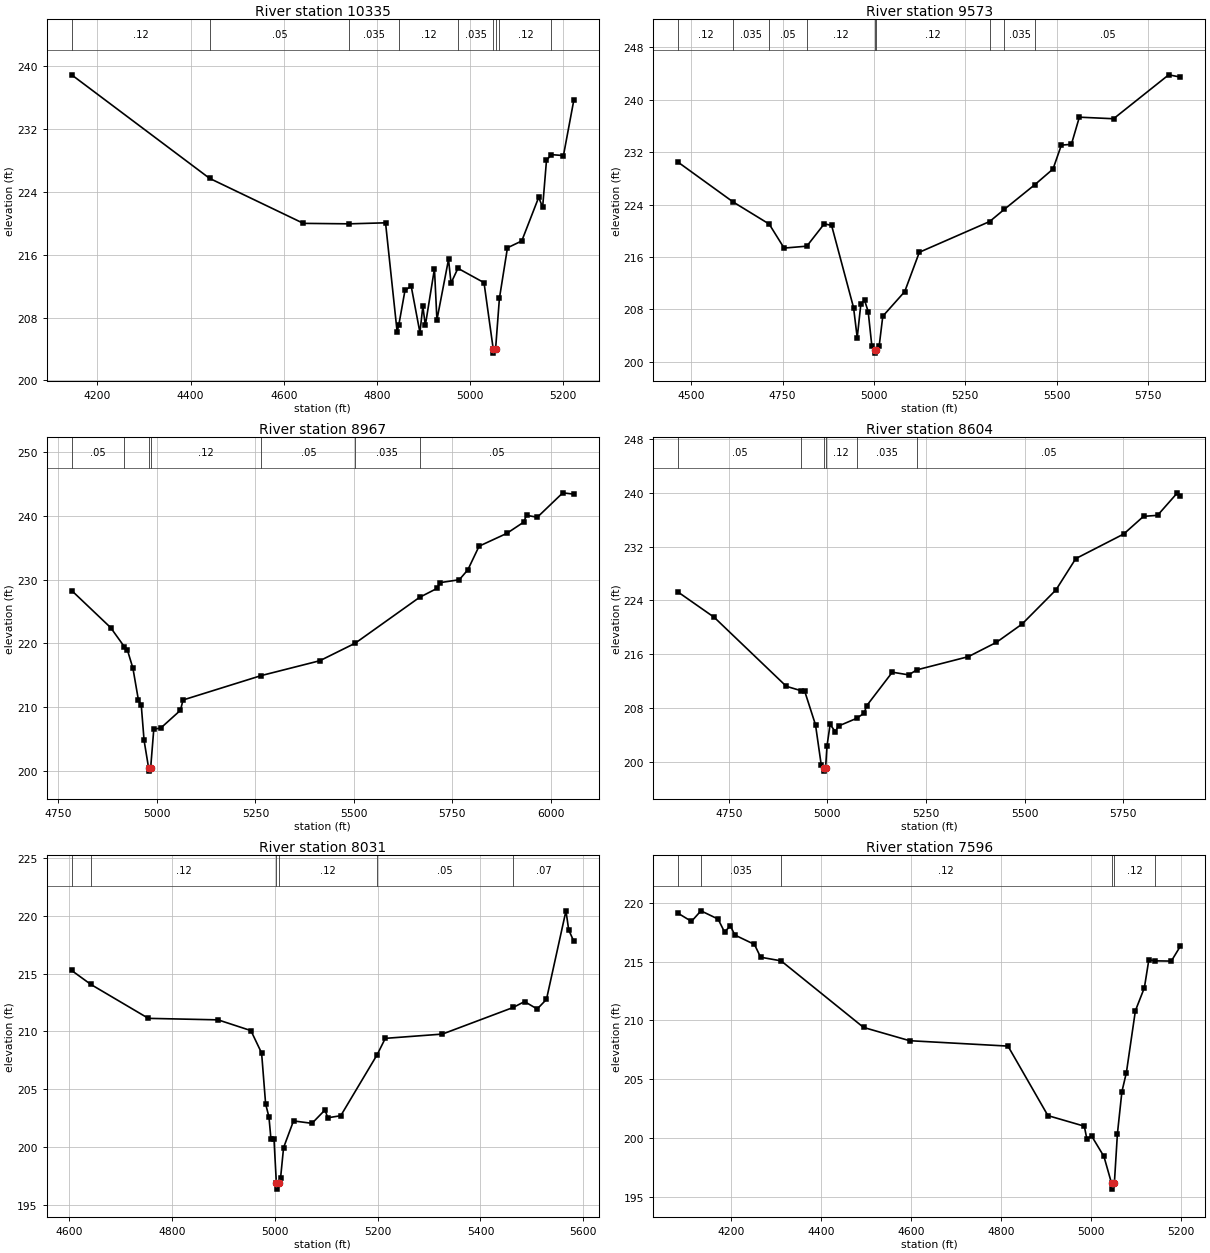
Type RM Length L Ch R = 1,10335,762,762,762
BEGIN DESCRIPTION:
Stream0846 19.0
END DESCRIPTION:
XS GIS Cut Line= 3
      2484175.01     13597725.02      2483875.00     13596925.00
      2483775.01     13596725.03
#Sta/Elev= 30
  4144.6  238.90  4440.7  225.72  4642.1  219.99  4740.6  219.93  4818.4  220.06
  4843.3  206.16  4847.0  207.10  4860.2  211.48  4873.5  211.98  4892.2  206.09
  4898.5  209.45  4903.8  207.00  4923.4  214.21  4928.7  207.70  4953.6  215.40
  4959.0  212.39  4973.8  214.27  5029.8  212.44  5049.6  203.97  5050.0  203.47
  5054.6  203.97  5062.8  210.43  5080.1  216.88  5110.8  217.75  5147.2  223.31
  5155.6  222.03  5163.9  228.02  5174.6  228.74  5200.3  228.62  5222.6  235.69
#Mann=9,-1,0
  4144.6    0.12       0  4440.7    0.05       0  4740.6   0.035       0
  4847.0    0.12       0  4973.8   0.035       0  5049.6   0.035       0
  5054.6   0.035       0  5062.8    0.12       0  5174.6    0.05       0
Bank Sta=5049.6,5054.6
Exp/Cntr=0.3,0.1

Type RM Length L Ch R = 1,9573,606,606,606
BEGIN DESCRIPTION:
Stream0846 18.0
END DESCRIPTION:
XS GIS Cut Line= 3
      2484325.00     13597525.01      2484344.74     13596733.76
      2484003.80     13596260.84
#Sta/Elev= 30
  4464.0  230.47  4614.7  224.39  4713.2  221.02  4754.1  217.35  4816.2  217.64
  4864.1  221.06  4884.1  220.81  4944.2  208.25  4954.2  203.66  4964.2  208.82
  4974.2  209.39  4984.2  207.65  4994.2  202.42  5001.6  201.80  5002.0  201.30
  5006.7  201.80  5014.2  202.34  5024.2  206.94  5084.2  210.70  5124.2  216.71
  5316.8  221.41  5356.4  223.25  5440.8  227.06  5490.1  229.43  5512.9  233.08
  5540.4  233.20  5562.2  237.35  5655.8  237.11  5806.7  243.82  5838.5  243.48
#Mann=9,-1,0
  4464.0    0.12       0  4614.7   0.035       0  4713.2    0.05       0
  4816.2    0.12       0  5001.6    0.05       0  5006.7    0.12       0
  5316.8    0.05       0  5356.4   0.035       0  5440.8    0.05       0
Bank Sta=5001.6,5006.7
Exp/Cntr=0.3,0.1

Type RM Length L Ch R = 1,8967,363,363,363
BEGIN DESCRIPTION:
Stream0846 17.0
END DESCRIPTION:
XS GIS Cut Line= 3
      2485025.01     13597025.01      2484875.00     13596875.00
      2484074.97     13596174.98
#Sta/Elev= 30
  4783.4  228.30  4882.4  222.49  4916.9  219.52  4924.8  219.01  4939.0  216.12
  4953.1  211.08  4960.2  210.30  4967.3  204.82  4978.8  200.50  4979.2  200.00
  4984.0  200.50  4992.0  206.59  5009.3  206.73  5059.6  209.53  5066.3  211.15
  5265.3  214.98  5413.6  217.30  5503.5  220.05  5666.8  227.23  5711.7  228.65
  5718.3  229.53  5767.7  229.99  5789.5  231.55  5818.0  235.25  5888.2  237.25
  5930.9  239.00  5938.5  240.08  5966.0  239.79  6030.6  243.61  6058.6  243.40
#Mann=7,-1,0
  4783.4    0.05       0  4916.9    0.12       0  4978.8    0.05       0
  4984.0    0.12       0  5265.3    0.05       0  5503.5   0.035       0
  5666.8    0.05       0
Bank Sta=4978.8,4984
Exp/Cntr=0.3,0.1

Type RM Length L Ch R = 1,8604,573,573,573
BEGIN DESCRIPTION:
Stream0846 16.0
END DESCRIPTION:
XS GIS Cut Line= 3
      2485175.00     13596874.99      2485054.76     13596587.49
      2484275.00     13596025.00
#Sta/Elev= 30
  4621.8  225.23  4713.2  221.48  4896.1  211.21  4934.0  210.55  4942.8  210.46
  4970.1  205.48  4984.5  199.56  4990.4  199.09  4990.8  198.59  4995.7  199.09
  4999.2  202.32  5007.1  205.53  5020.1  204.48  5028.7  205.31  5074.6  206.45
  5093.4  207.22  5099.8  208.32  5164.8  213.31  5206.6  212.91  5226.4  213.65
  5357.5  215.62  5428.7  217.75  5493.7  220.47  5579.6  225.55  5629.9  230.21
  5751.4  233.87  5801.7  236.50  5837.2  236.65  5887.5  240.00  5894.9  239.57
#Mann=6,-1,0
  4621.8    0.05       0  4934.0    0.12       0  4990.4    0.05       0
  4995.7    0.12       0  5074.6   0.035       0  5226.4    0.05       0
Bank Sta=4990.4,4995.7
Exp/Cntr=0.3,0.1

Type RM Length L Ch R = 1,8031,435,435,435
BEGIN DESCRIPTION:
Stream0846 15.0
END DESCRIPTION:
XS GIS Cut Line= 3
      2485725.04     13596425.03      2485425.00     13596175.00
      2484874.99     13595975.00
#Sta/Elev= 30
  4605.6  215.27  4643.1  214.06  4754.7  211.13  4890.1  211.00  4953.9  210.07
  4974.7  208.13  4982.5  203.73  4989.0  202.59  4992.9  200.66  4998.8  200.66
  5003.4  196.86  5003.8  196.36  5008.8  196.86  5011.5  197.30  5017.4  199.95
  5036.7  202.26  5072.6  202.05  5097.9  203.21  5103.2  202.53  5128.5  202.71
  5199.4  208.00  5215.0  209.40  5326.0  209.77  5463.4  212.07  5485.6  212.58
  5510.2  211.94  5528.2  212.77  5566.1  220.43  5571.4  218.78  5581.4  217.79
#Mann=6,-1,0
  4605.6   0.035       0  4643.1    0.12       0  5003.4    0.05       0
  5008.8    0.12       0  5199.4    0.05       0  5463.4    0.07       0
Bank Sta=5003.4,5008.8
Exp/Cntr=0.3,0.1

Type RM Length L Ch R = 1,7596,436,436,436
BEGIN DESCRIPTION:
Stream0846 14.0
END DESCRIPTION:
XS GIS Cut Line= 3
      2485875.01     13596575.02      2485425.00     13595775.00
      2485425.00     13595575.00
#Sta/Elev= 30
  4081.4  219.12  4111.1  218.43  4132.2  219.33  4170.3  218.63  4184.7  217.53
  4197.8  218.05  4207.6  217.27  4251.3  216.47  4265.0  215.38  4310.6  215.07
  4494.2  209.40  4596.8  208.27  4815.7  207.81  4904.6  201.89  4985.6  200.99
  4991.3  199.90  5001.8  200.16  5029.3  198.41  5046.2  196.13  5046.7  195.63
  5052.5  196.13  5059.3  200.35  5069.3  203.93  5079.3  205.56  5099.3  210.82
  5119.3  212.78  5129.3  215.17  5142.5  215.07  5179.3  215.05  5199.3  216.31
#Mann=6,-1,0
  4081.4    0.05       0  4132.2   0.035       0  4310.6    0.12       0
  5046.2    0.05       0  5052.5    0.12       0  5142.5    0.07       0
Bank Sta=5046.2,5052.5
Exp/Cntr=0.3,0.1

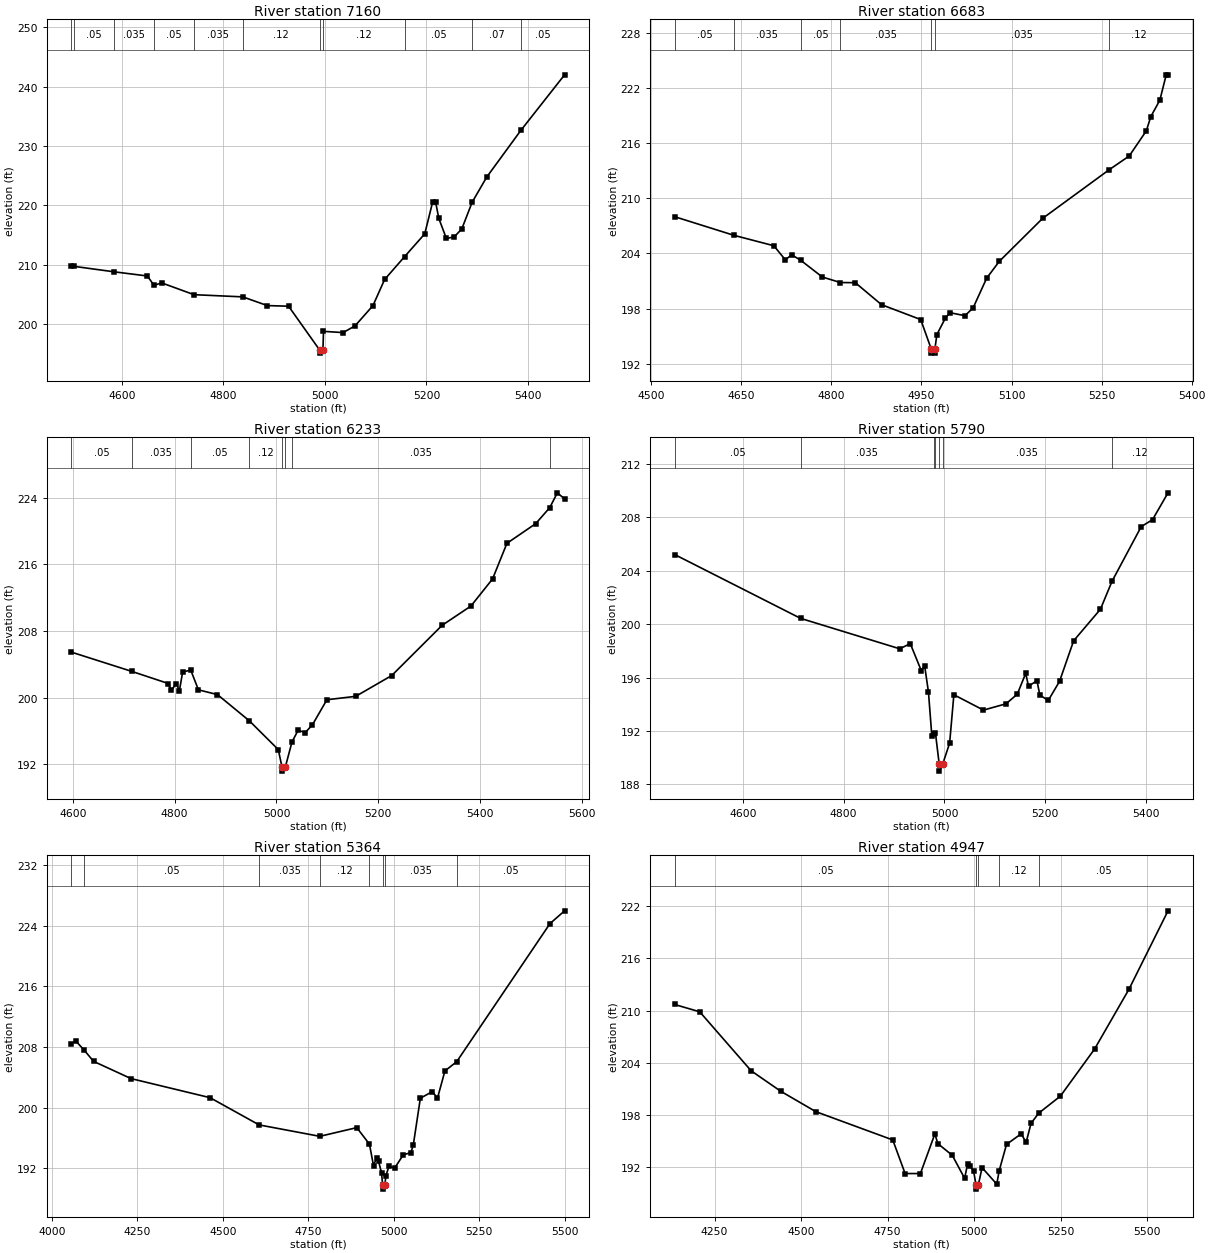
Type RM Length L Ch R = 1,7160,477,477,477
BEGIN DESCRIPTION:
Stream0846 13.0
END DESCRIPTION:
XS GIS Cut Line= 3
      2486124.99     13596074.99      2485825.00     13595675.00
      2485574.99     13595274.99
#Sta/Elev= 30
  4500.3  209.85  4506.0  209.73  4584.2  208.82  4650.3  208.11  4663.4  206.53
  4678.4  206.95  4742.2  204.96  4838.2  204.59  4886.7  203.12  4928.4  203.02
  4989.8  195.61  4990.3  195.11  4996.1  195.61  4997.2  198.78  5035.7  198.57
  5059.3  199.70  5094.6  203.12  5117.6  207.52  5156.8  211.36  5196.6  215.21
  5212.0  220.52  5217.9  220.62  5224.3  217.82  5239.1  214.45  5254.4  214.67
  5269.7  216.06  5289.9  220.53  5318.7  224.78  5386.0  232.66  5472.0  242.01
#Mann=11,-1,0
  4500.3   0.035       0  4506.0    0.05       0  4584.2   0.035       0
  4663.4    0.05       0  4742.2   0.035       0  4838.2    0.12       0
  4989.8    0.05       0  4996.1    0.12       0  5156.8    0.05       0
  5289.9    0.07       0  5386.0    0.05       0
Bank Sta=4989.8,4996.1
Exp/Cntr=0.3,0.1

Type RM Length L Ch R = 1,6683,450,450,450
BEGIN DESCRIPTION:
Stream0846 12.0
END DESCRIPTION:
XS GIS Cut Line= 3
      2486325.00     13595925.02      2486225.00     13595475.00
      2486024.98     13595174.96
#Sta/Elev= 30
  4539.0  207.99  4637.9  205.96  4704.2  204.83  4723.4  203.29  4733.7  203.85
  4748.7  203.26  4784.9  201.43  4814.9  200.83  4839.9  200.81  4883.5  198.42
  4948.8  196.80  4966.0  193.65  4966.5  193.15  4972.0  193.15  4972.5  193.65
  4975.7  195.17  4989.8  196.95  4997.4  197.55  5022.5  197.22  5036.1  198.08
  5058.6  201.30  5079.6  203.13  5151.7  207.80  5262.9  213.11  5296.0  214.59
  5324.5  217.33  5332.0  218.88  5347.0  220.66  5357.6  223.42  5360.6  223.42
#Mann=7,-1,0
  4539.0    0.05       0  4637.9   0.035       0  4748.7    0.05       0
  4814.9   0.035       0  4966.0   0.035       0  4972.5   0.035       0
  5262.9    0.12       0
Bank Sta=4966,4972.5
Exp/Cntr=0.3,0.1

Type RM Length L Ch R = 1,6233,443,443,443
BEGIN DESCRIPTION:
Stream0846 11.0
END DESCRIPTION:
XS GIS Cut Line= 3
      2486824.99     13595674.99      2486625.00     13595325.00
      2486224.99     13594924.99
#Sta/Elev= 30
  4596.9  205.47  4716.2  203.14  4787.6  201.69  4793.4  200.87  4803.5  201.69
  4809.2  200.78  4815.7  203.06  4831.6  203.31  4846.7  200.93  4884.1  200.36
  4947.0  197.19  5003.5  193.75  5010.8  191.66  5011.3  191.16  5017.4  191.66
  5030.5  194.68  5042.4  196.06  5056.6  195.80  5070.7  196.74  5099.0  199.74
  5155.6  200.15  5226.3  202.65  5325.3  208.69  5381.8  211.00  5424.3  214.26
  5452.5  218.54  5509.1  220.91  5536.6  222.83  5551.5  224.61  5565.7  223.88
#Mann=8,-1,0
  4596.9    0.05       0  4716.2   0.035       0  4831.6    0.05       0
  4947.0    0.12       0  5010.8    0.05       0  5017.4    0.12       0
  5030.5   0.035       0  5536.6    0.05       0
Bank Sta=5010.8,5017.4
Exp/Cntr=0.3,0.1

Type RM Length L Ch R = 1,5790,426,426,426
BEGIN DESCRIPTION:
Stream0846 10.0
END DESCRIPTION:
XS GIS Cut Line= 3
      2487325.00     13595475.00      2486975.00     13595075.00
      2486575.02     13594875.01
#Sta/Elev= 30
  4464.7  205.22  4714.5  200.44  4911.3  198.16  4932.1  198.55  4954.0  196.52
  4960.6  196.90  4968.2  194.92  4974.9  191.63  4979.4  191.76  4982.1  191.84
  4989.6  189.50  4990.1  189.00  4996.2  189.50  5010.2  191.10  5018.6  194.72
  5077.3  193.57  5122.0  194.04  5144.4  194.76  5161.1  196.32  5166.7  195.36
  5183.5  195.77  5189.1  194.70  5205.8  194.29  5228.2  195.72  5256.2  198.76
  5309.3  201.12  5332.4  203.22  5390.3  207.31  5412.7  207.83  5443.4  209.84
#Mann=7,-1,0
  4464.7    0.05       0  4714.5   0.035       0  4979.4    0.12       0
  4982.1   0.035       0  4989.6   0.035       0  4996.2   0.035       0
  5332.4    0.12       0
Bank Sta=4989.6,4996.2
Exp/Cntr=0.3,0.1

Type RM Length L Ch R = 1,5364,417,417,417
BEGIN DESCRIPTION:
Stream0846 9.0
END DESCRIPTION:
XS GIS Cut Line= 3
      2487474.98     13595524.97      2486975.00     13594725.00
      2486674.98     13594324.97
#Sta/Elev= 30
  4056.4  208.46  4069.9  208.79  4094.8  207.56  4121.8  206.10  4231.5  203.82
  4462.6  201.30  4606.2  197.70  4783.7  196.19  4891.9  197.34  4929.0  195.15
  4940.8  192.31  4949.6  193.33  4955.5  192.89  4964.4  191.36  4967.5  189.71
  4968.0  189.21  4974.2  189.71  4976.8  190.99  4986.2  192.21  5002.9  192.01
  5027.9  193.74  5049.8  194.03  5057.1  195.00  5077.9  201.23  5113.3  202.11
  5127.9  201.22  5149.8  204.84  5184.1  206.05  5457.1  224.31  5499.8  226.00
#Mann=8,-1,0
  4056.4   0.035       0  4094.8    0.05       0  4606.2   0.035       0
  4783.7    0.12       0  4929.0   0.035       0  4967.5   0.035       0
  4974.2   0.035       0  5184.1    0.05       0
Bank Sta=4967.5,4974.2
Exp/Cntr=0.3,0.1

Type RM Length L Ch R = 1,4947,530,530,530
BEGIN DESCRIPTION:
Stream0846 8.0
END DESCRIPTION:
XS GIS Cut Line= 3
      2487825.01     13595225.02      2487325.00     13594525.00
      2486925.03     13594125.03
#Sta/Elev= 30
  4134.7  210.71  4207.2  209.87  4355.9  203.09  4441.9  200.73  4542.7  198.40
  4765.1  195.15  4800.8  191.29  4845.0  191.29  4886.8  195.84  4895.4  194.73
  4937.2  193.38  4972.8  190.74  4981.4  192.40  4987.6  192.17  4998.5  191.63
  5005.7  190.00  5006.2  189.50  5012.5  190.00  5023.2  191.97  5065.7  190.07
  5072.7  191.62  5093.9  194.64  5136.4  195.86  5150.5  194.86  5164.7  197.05
  5187.0  198.23  5249.5  200.18  5348.5  205.60  5447.5  212.44  5560.6  221.47
#Mann=5,-1,0
  4134.7    0.05       0  5005.7    0.05       0  5012.5    0.05       0
  5072.7    0.12       0  5187.0    0.05       0
Bank Sta=5005.7,5012.5
Exp/Cntr=0.3,0.1