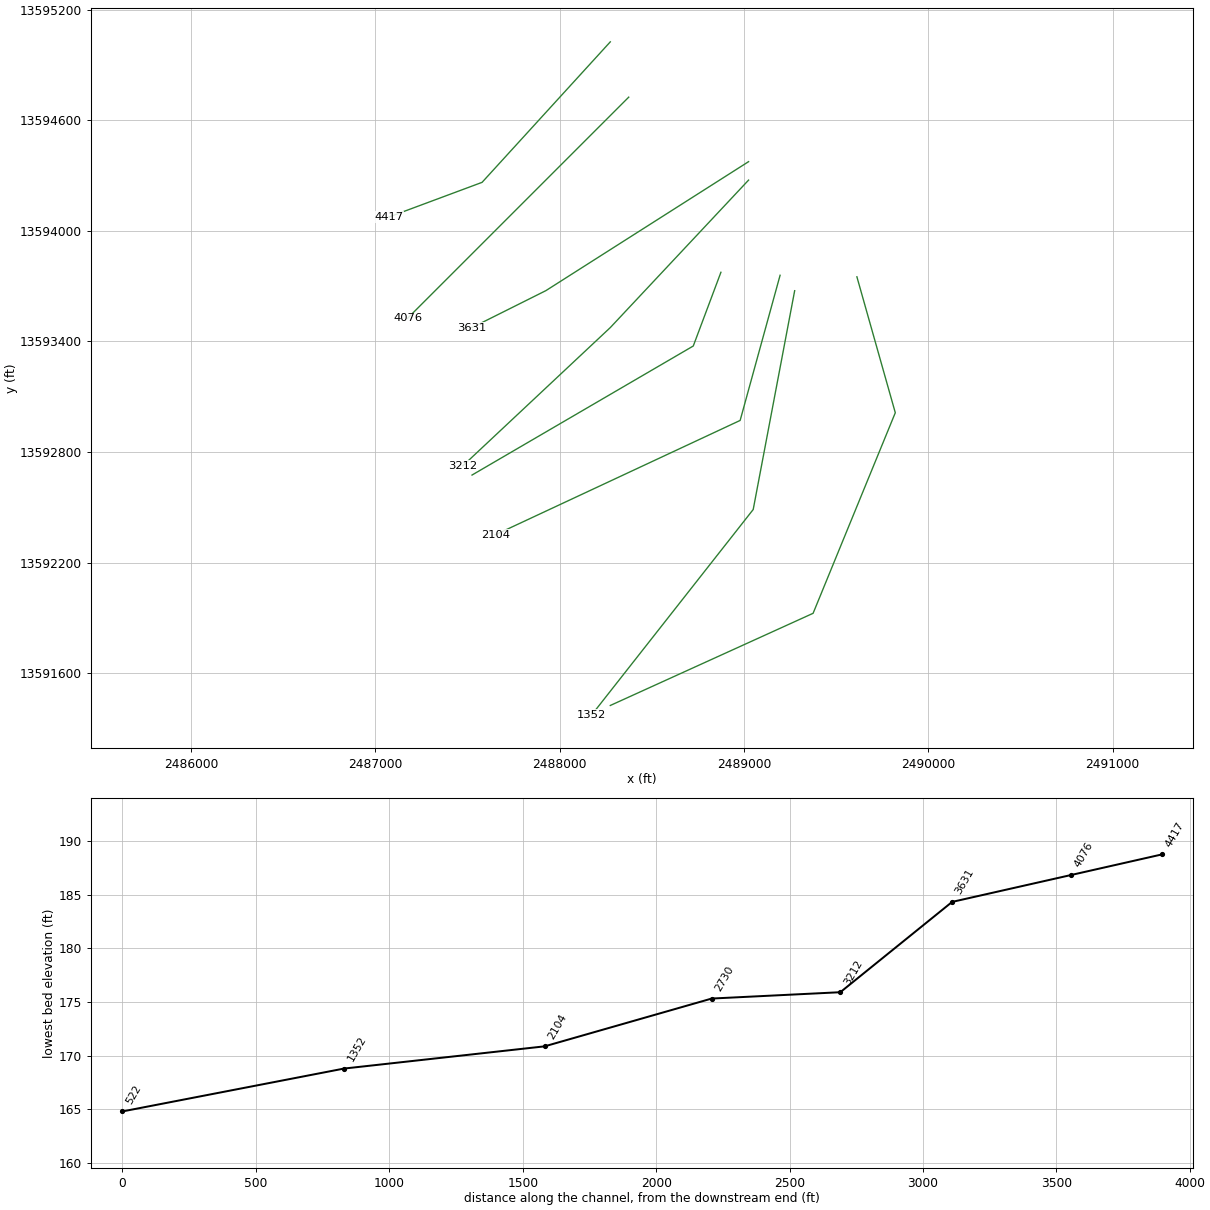
HEC-RAS study Stream0846.prj: Stream0846 Base Level Engineering

--- Stream0846.g01 (geometry) --- (continued)

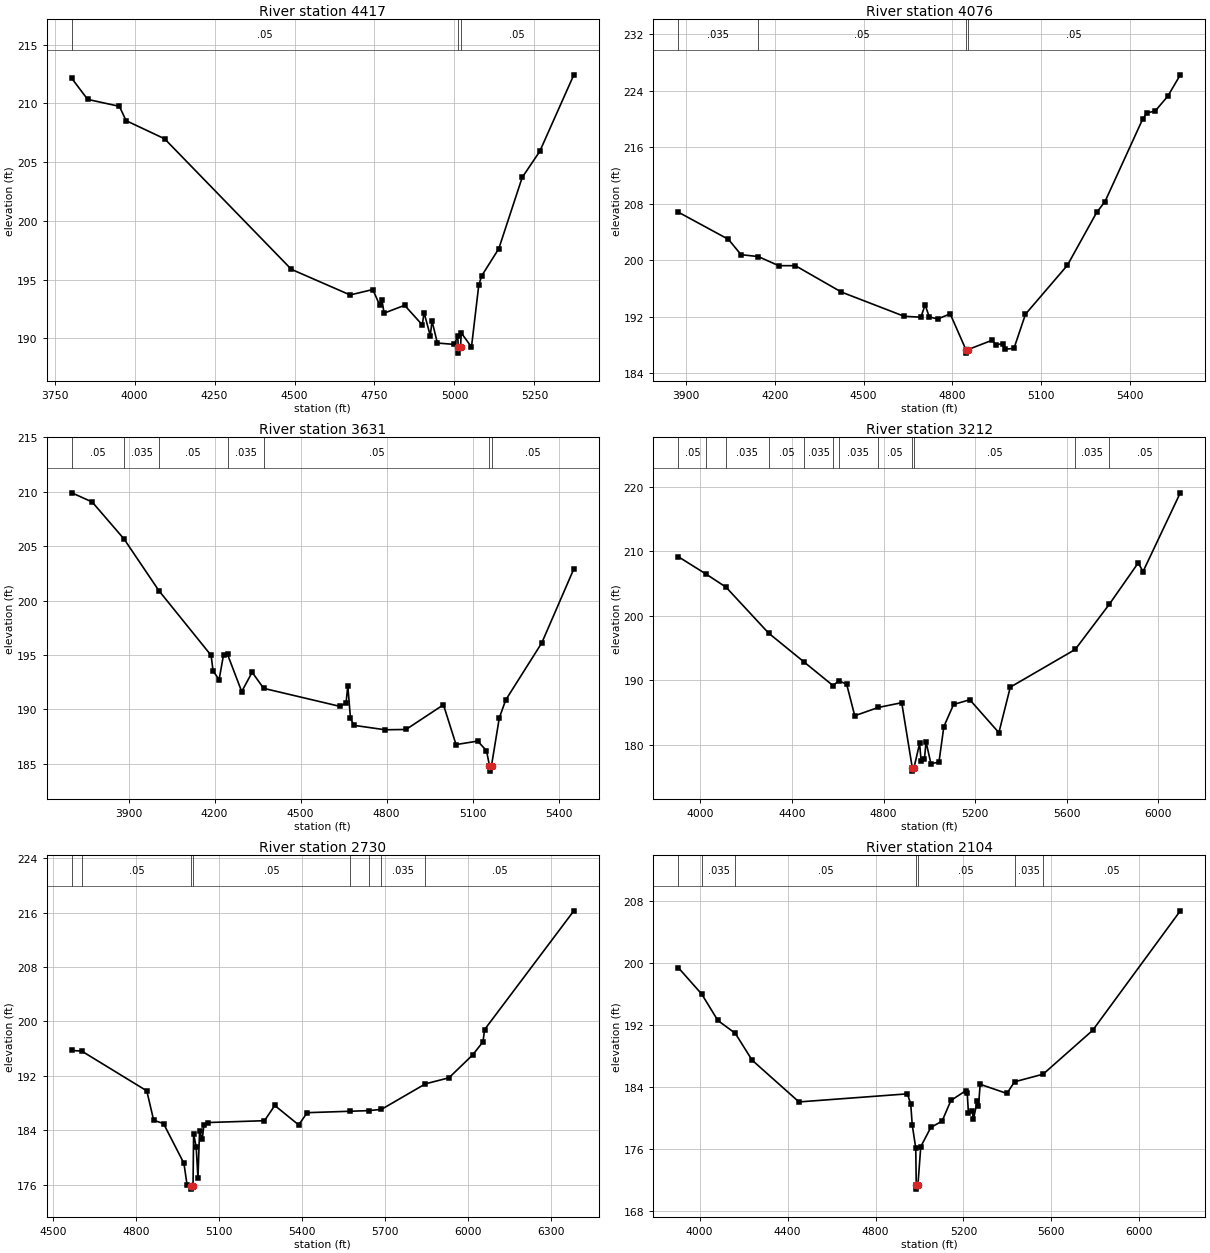
Type RM Length L Ch R = 1,4417,341,341,341
BEGIN DESCRIPTION:
Stream0846 7.0
END DESCRIPTION:
XS GIS Cut Line= 3
      2488274.99     13595024.99      2487579.44     13594262.78
      2487075.02     13594075.01
#Sta/Elev= 30
  3803.3  212.12  3852.9  210.33  3952.2  209.74  3973.2  208.52  4093.5  206.98
  4490.0  195.87  4673.8  193.69  4744.7  194.15  4765.7  192.86  4773.1  193.30
  4779.9  192.14  4844.2  192.81  4899.5  191.14  4904.9  192.19  4924.5  190.22
  4929.9  191.47  4946.6  189.60  5000.0  189.48  5010.2  190.21  5012.0  189.24
  5012.5  188.74  5019.0  189.24  5021.3  190.46  5053.3  189.26  5076.2  194.55
  5085.3  195.32  5138.7  197.63  5211.9  203.69  5266.7  205.90  5373.4  212.42
#Mann=3,-1,0
  3803.3    0.05       0  5012.0    0.05       0  5019.0    0.05       0
Bank Sta=5012,5019
Exp/Cntr=0.3,0.1

Type RM Length L Ch R = 1,4076,445,445,445
BEGIN DESCRIPTION:
Stream0846 6.0
END DESCRIPTION:
XS GIS Cut Line= 3
      2488375.03     13594725.03      2487575.00     13593925.00
      2487175.00     13593525.00
#Sta/Elev= 30
  3873.4  206.80  4043.1  202.94  4085.6  200.77  4144.0  200.50  4212.9  199.21
  4269.4  199.21  4425.0  195.47  4637.1  192.04  4693.7  191.91  4707.8  193.66
  4722.0  191.95  4750.3  191.66  4792.7  192.38  4845.7  187.32  4846.2  186.82
  4852.7  187.32  4934.1  188.64  4948.2  187.99  4969.5  188.17  4976.5  187.36
  5008.3  187.50  5047.2  192.34  5188.7  199.26  5287.7  206.75  5315.9  208.29
  5443.2  219.97  5457.4  220.85  5485.6  221.12  5528.1  223.22  5570.5  226.25
#Mann=4,-1,0
  3873.4   0.035       0  4144.0    0.05       0  4845.7    0.05       0
  4852.7    0.05       0
Bank Sta=4845.7,4852.7
Exp/Cntr=0.3,0.1

Type RM Length L Ch R = 1,3631,419,419,419
BEGIN DESCRIPTION:
Stream0846 5.0
END DESCRIPTION:
XS GIS Cut Line= 3
      2489025.03     13594375.02      2487925.00     13593675.00
      2487524.99     13593474.99
#Sta/Elev= 30
  3701.9  209.90  3773.0  209.06  3884.1  205.66  4005.7  200.91  4187.9  194.96
  4194.7  193.53  4215.8  192.73  4231.1  195.00  4245.3  195.04  4294.6  191.63
  4331.0  193.41  4371.1  191.93  4637.5  190.27  4658.6  190.60  4664.6  192.18
  4673.9  189.19  4685.7  188.53  4795.0  188.12  4867.8  188.15  4998.2  190.42
  5042.1  186.76  5117.6  187.08  5148.3  186.20  5158.7  184.82  5159.2  184.32
  5165.8  184.82  5193.0  189.21  5215.4  190.86  5341.2  196.11  5453.0  202.91
#Mann=7,-1,0
  3701.9    0.05       0  3884.1   0.035       0  4005.7    0.05       0
  4245.3   0.035       0  4371.1    0.05       0  5158.7    0.05       0
  5165.8    0.05       0
Bank Sta=5158.7,5165.8
Exp/Cntr=0.3,0.1

Type RM Length L Ch R = 1,3212,482,482,482
BEGIN DESCRIPTION:
Stream0846 4.0
END DESCRIPTION:
XS GIS Cut Line= 3
      2489024.98     13594274.98      2488275.00     13593475.00
      2487475.03     13592725.03
#Sta/Elev= 30
  3902.8  209.14  4026.2  206.40  4111.3  204.42  4297.7  197.29  4453.1  192.80
  4579.3  189.15  4603.6  189.92  4638.6  189.36  4673.8  184.49  4776.2  185.77
  4879.0  186.51  4925.2  176.41  4925.7  175.91  4932.4  176.41  4957.1  180.20
  4963.9  177.41  4978.1  177.80  4985.4  180.43  5006.4  177.08  5041.6  177.29
  5063.1  182.82  5105.6  186.24  5176.4  186.97  5303.4  181.87  5353.2  188.92
  5636.7  194.76  5785.3  201.74  5912.0  208.17  5933.1  206.83  6095.9  219.03
#Mann=12,-1,0
  3902.8    0.05       0  4026.2    0.07       0  4111.3   0.035       0
  4297.7    0.05       0  4453.1   0.035       0  4579.3    0.05       0
  4603.6   0.035       0  4776.2    0.05       0  4925.2    0.05       0
  4932.4    0.05       0  5636.7   0.035       0  5785.3    0.05       0
Bank Sta=4925.2,4932.4
Exp/Cntr=0.3,0.1

Type RM Length L Ch R = 1,2730,626,626,626
BEGIN DESCRIPTION:
Stream0846 3.0
END DESCRIPTION:
XS GIS Cut Line= 3
      2488874.99     13593774.96      2488725.00     13593375.00
      2487525.01     13592675.00
#Sta/Elev= 30
  4567.3  195.72  4603.3  195.63  4838.7  189.78  4863.6  185.45  4899.2  184.97
  4973.1  179.11  4984.7  175.87  4998.6  175.82  4999.1  175.32  5006.0  175.82
  5008.1  183.50  5017.6  181.45  5023.8  176.92  5029.6  183.80  5039.5  182.72
  5045.3  184.73  5061.0  185.12  5264.5  185.39  5301.7  187.63  5388.1  184.77
  5419.1  186.57  5575.3  186.78  5641.0  186.87  5687.3  187.05  5846.6  190.81
  5931.8  191.70  6017.8  195.07  6055.0  197.00  6060.8  198.80  6383.7  216.27
#Mann=8,-1,0
  4567.3   0.035       0  4603.3    0.05       0  4998.6    0.05       0
  5006.0    0.05       0  5575.3   0.035       0  5641.0    0.05       0
  5687.3   0.035       0  5846.6    0.05       0
Bank Sta=4998.6,5006
Exp/Cntr=0.3,0.1

Type RM Length L Ch R = 1,2104,752,752,752
BEGIN DESCRIPTION:
XS7827
END DESCRIPTION:
XS GIS Cut Line= 3
      2489195.92     13593758.72      2488979.26     13592971.28
      2487650.29     13592350.53
#Sta/Elev= 30
  3902.8  199.38  4009.7  195.96  4083.0  192.57  4162.2  190.92  4238.6  187.47
  4452.0  182.09  4945.0  183.13  4960.2  181.84  4967.0  179.14  4983.0  176.16
  4985.4  171.37  4985.9  170.87  4992.8  171.37  5005.9  176.34  5051.6  178.81
  5102.8  179.62  5143.0  182.28  5209.8  183.52  5217.1  183.25  5222.6  180.68
  5239.9  180.90  5245.4  179.86  5262.8  182.20  5268.3  181.53  5276.1  184.36
  5397.5  183.18  5432.4  184.68  5562.3  185.66  5787.6  191.30  6186.3  206.68
#Mann=7,-1,0
  3902.8    0.05       0  4009.7   0.035       0  4162.2    0.05       0
  4985.4    0.05       0  4992.8    0.05       0  5432.4   0.035       0
  5562.3    0.05       0
Bank Sta=4985.4,4992.8
Exp/Cntr=0.3,0.1

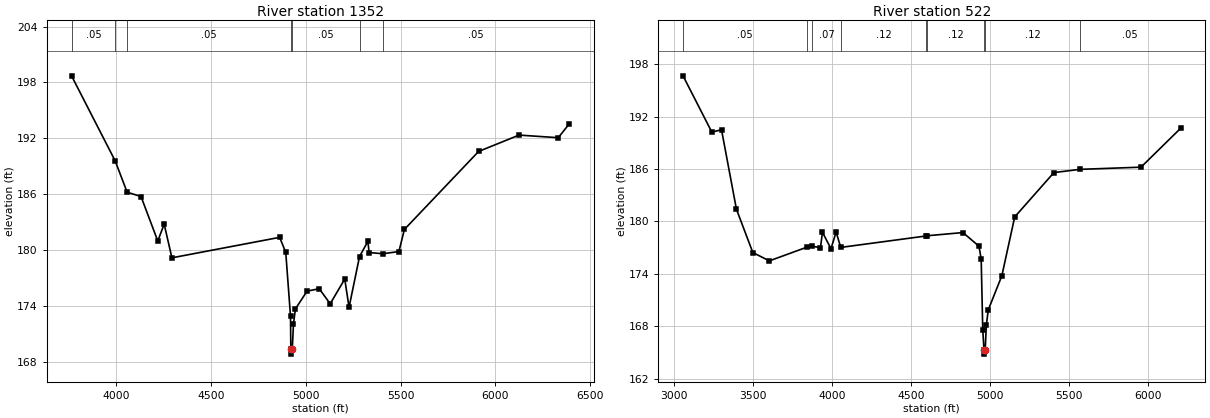
Type RM Length L Ch R = 1,1352,830,830,830
BEGIN DESCRIPTION:
Stream0846 2.0
END DESCRIPTION:
XS GIS Cut Line= 3
      2489275.00     13593675.02      2489050.09     13592488.00
      2488174.97     13591374.97
#Sta/Elev= 30
  3764.4  198.71  3994.5  189.57  4057.6  186.20  4130.8  185.74  4219.2  180.96
  4253.0  182.77  4293.7  179.15  4862.1  181.35  4894.2  179.73  4919.4  172.86
  4920.9  169.30  4921.4  168.80  4928.6  169.30  4934.9  172.04  4945.1  173.66
  5006.6  175.57  5070.8  175.83  5128.6  174.21  5205.4  176.87  5228.0  173.83
  5283.3  179.29  5327.4  180.92  5333.8  179.72  5406.2  179.59  5491.0  179.82
  5519.9  182.20  5911.2  190.58  6124.5  192.34  6331.4  192.06  6388.4  193.52
#Mann=7,-1,0
  3764.4    0.05       0  3994.5   0.035       0  4057.6    0.05       0
  4920.9    0.05       0  4928.6    0.05       0  5283.3    0.07       0
  5406.2    0.05       0
Bank Sta=4920.9,4928.6
Exp/Cntr=0.3,0.1

Type RM Length L Ch R = 1,522,0,0,0
BEGIN DESCRIPTION:
Stream0846 1.0
END DESCRIPTION:
XS GIS Cut Line= 4
      2489612.52     13593750.35      2489820.82     13593012.94
      2489375.00     13591925.00      2488275.01     13591425.00
#Sta/Elev= 30
  3058.0  196.68  3240.2  190.24  3301.8  190.50  3396.1  181.41  3500.0  176.44
  3604.8  175.49  3841.0  177.05  3877.8  177.15  3928.3  177.01  3940.9  178.77
  3994.9  176.88  4027.4  178.80  4056.5  177.03  4597.1  178.34  4605.7  178.37
  4830.5  178.73  4931.9  177.17  4946.0  175.69  4955.9  167.62  4963.7  165.31
  4964.2  164.81  4971.5  165.31  4978.4  168.09  4990.7  169.87  5076.9  173.79
  5158.2  180.52  5406.4  185.60  5571.7  185.97  5957.9  186.22  6208.3  190.66
#Mann=9,-1,0
  3058.0    0.05       0  3841.0   0.035       0  3877.8    0.07       0
  4056.5    0.12       0  4597.1    0.07       0  4605.7    0.12       0
  4963.7    0.05       0  4971.5    0.12       0  5571.7    0.05       0
Bank Sta=4963.7,4971.5
Exp/Cntr=0.3,0.1

Chan Stop Cuts=-1