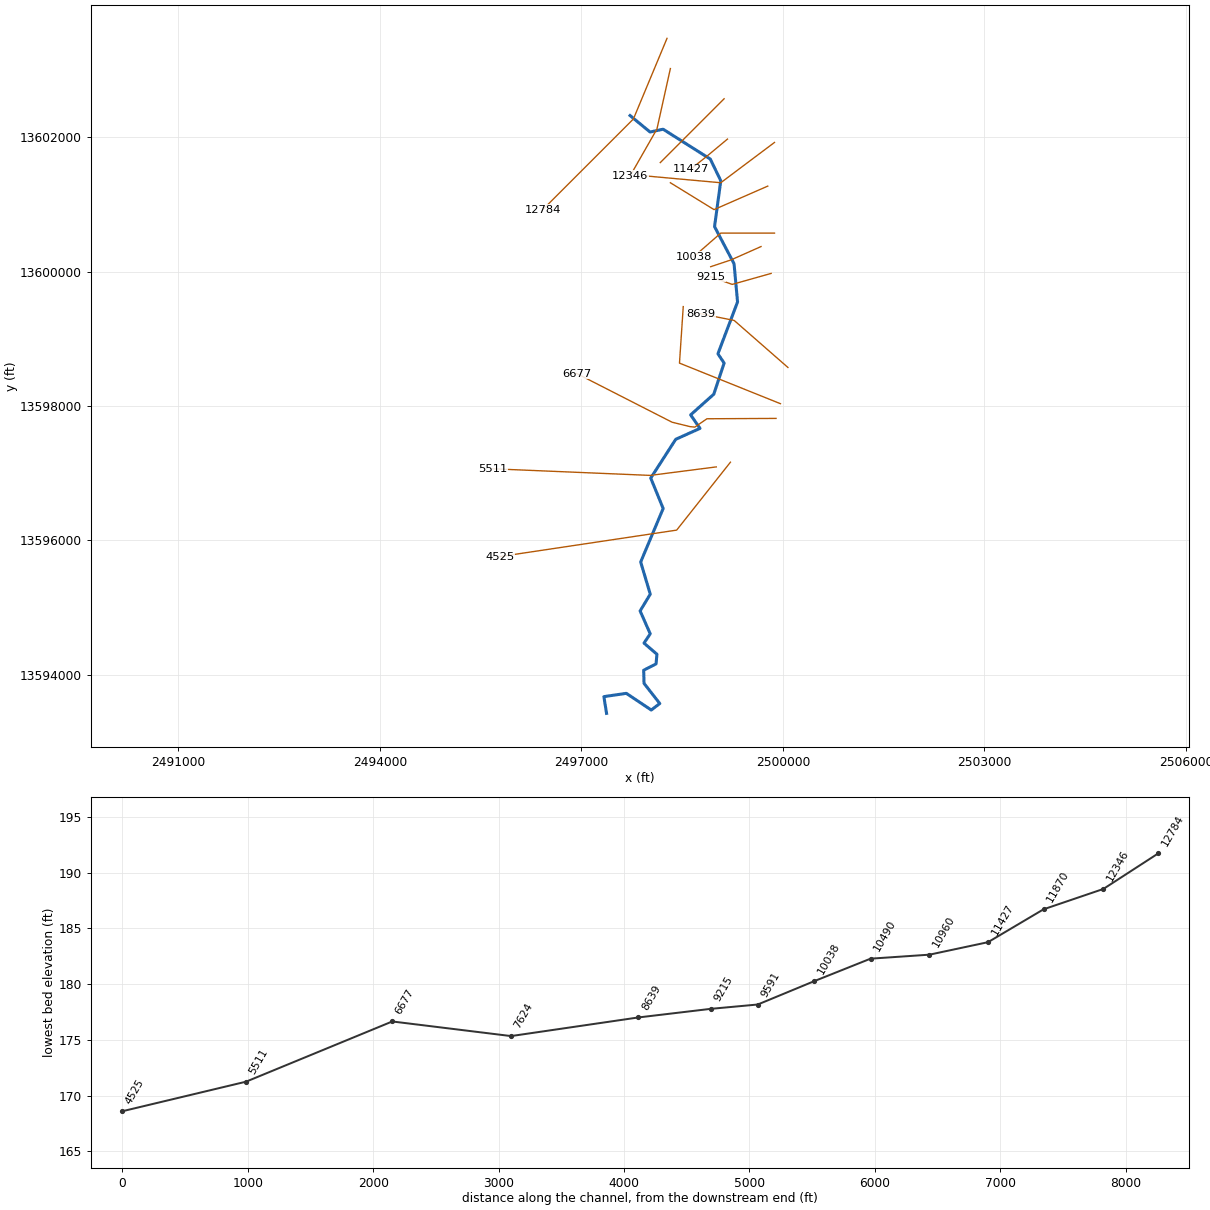
--- Stream0847.prj (project) ---

Proj Title=Stream0847 Base Level Engineering
Current Plan=p01
Default Exp/Contr=0.3,0.1
English Units
Geom File=g01
Flow File=f01
Plan File=p01
BEGIN DESCRIPTION:
Stream0847
END DESCRIPTION:

--- Stream0847.p01 (plan) ---

Plan Title=Multiple Run
Short Identifier=Multiple
Geom File=g01
Flow File=f01
Subcritical Flow
K Sum by GR= 0
Std Step Tol= 0.01
Critical Tol= 0.01
Num of Std Step Trials= 20
Max Error Tol= 0.3
Flow Tol Ratio= 0.001
Split Flow NTrial= 30
Split Flow Tol= 0.02
Split Flow Ratio= 0.02
Log Output Level= 0
Friction Slope Method= 1
Unsteady Friction Slope Method= 2
Unsteady Bridges Friction Slope Method= 1
Parabolic Critical Depth
Global Vel Dist=  1 , 1 , 1
Global Log Level= 0
CheckData=True
Encroach Param= -1, 0, 0, 0
BEGIN DESCRIPTION:
Multiple Run
END DESCRIPTION:

--- Stream0847.f01 (steady flow) ---

Flow Title=Multiple
Number of Profiles=7
Profile Names=10-year,25-year,50-year,1pct_min,100-year,1pct_plu,500-year
River Rch & RM= Stream0847,Reach-1,12784
     669    1080    1452     946    1887    3765    3155
River Rch & RM= Stream0847,Reach-1,10960
     892    1450    1957    1276    2546    5080    4273
River Rch & RM= Stream0847,Reach-1,4525
     899    1454    1954    1269    2531    5050    4210
Boundary for River Rch & Prof#=Stream0847,Reach-1,1
Up Type=0
Dn Type=3
Dn Slope=0.005
Boundary for River Rch & Prof#=Stream0847,Reach-1,2
Up Type=0
Dn Type=3
Dn Slope=0.005
Boundary for River Rch & Prof#=Stream0847,Reach-1,3
Up Type=0
Dn Type=3
Dn Slope=0.005
Boundary for River Rch & Prof#=Stream0847,Reach-1,4
Up Type=0
Dn Type=3
Dn Slope=0.005
Boundary for River Rch & Prof#=Stream0847,Reach-1,5
Up Type=0
Dn Type=3
Dn Slope=0.005
Boundary for River Rch & Prof#=Stream0847,Reach-1,6
Up Type=0
Dn Type=3
Dn Slope=0.005
Boundary for River Rch & Prof#=Stream0847,Reach-1,7
Up Type=0
Dn Type=3
Dn Slope=0.005

--- Stream0847.g01 (geometry) ---

Geom Title=Existing Conditions

River Reach=Stream0847,Reach-1
Reach XY= 30
      2497725.00     13602325.00      2498022.71     13602080.10
      2498216.65     13602122.00      2498919.27     13601677.55
      2499075.29     13601354.82      2498982.79     13600671.60
      2499272.93     13600119.14      2499325.20     13599549.92
      2499032.85     13598778.23      2499125.10     13598640.36
      2498971.25     13598176.55      2498626.49     13597869.15
      2498766.16     13597668.05      2498404.58     13597505.24
      2498032.88     13596928.22      2498217.67     13596475.10
      2497882.88     13595678.22      2498025.62     13595199.91
      2497874.68     13594949.89      2498024.96     13594609.58
      2497932.49     13594471.42      2498125.07     13594305.01
      2498111.64     13594161.65      2497927.50     13594066.85
      2497932.82     13593871.59      2498167.24     13593571.57
      2498040.42     13593475.03      2497668.97     13593723.38
      2497335.24     13593674.01      2497375.00     13593425.00

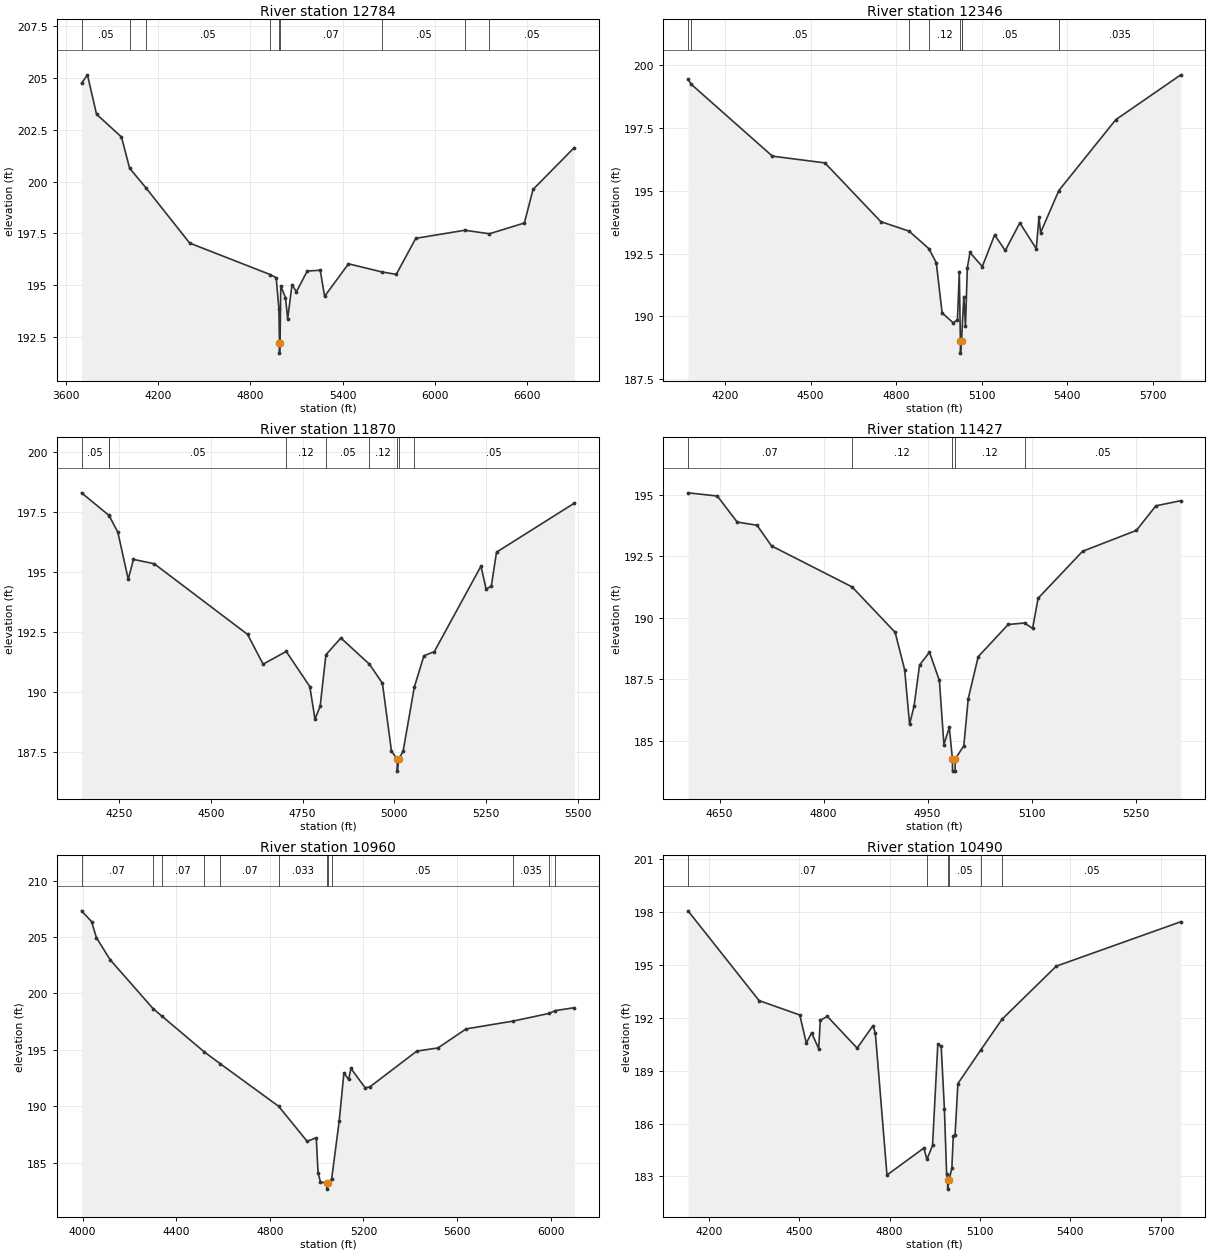
Type RM Length L Ch R = 1,12784,438,438,438
BEGIN DESCRIPTION:
Stream0847 27.0
END DESCRIPTION:
XS GIS Cut Line= 3
      2498274.99     13603474.96      2497775.00     13602275.00
      2496425.04     13600925.04
#Sta/Elev= 30
  3700.0  204.74  3738.4  205.15  3797.5  203.25  3960.0  202.15  4013.2  200.64
  4121.2  199.68  4404.1  197.03  4929.2  195.51  4967.5  195.36  4985.3  193.86
  4988.8  192.22  4989.0  191.72  4992.8  192.22  4997.3  194.96  5028.2  194.40
  5042.4  193.37  5070.7  195.03  5099.0  194.68  5169.7  195.68  5254.5  195.72
  5282.8  194.46  5438.4  196.03  5655.3  195.64  5749.5  195.52  5876.8  197.26
  6196.4  197.65  6356.2  197.48  6583.9  198.00  6640.4  199.62  6909.1  201.64
#Mann=9,-1,0
  3700.0    0.05       0  4013.2    0.07       0  4121.2    0.05       0
  4929.2    0.07       0  4988.8    0.05       0  4992.8    0.07       0
  5655.3    0.05       0  6196.4   0.035       0  6356.2    0.05       0
Bank Sta=4988.8,4992.8
Exp/Cntr=0.3,0.1

Type RM Length L Ch R = 1,12346,476,476,476
BEGIN DESCRIPTION:
Stream0847 26.0
END DESCRIPTION:
XS GIS Cut Line= 3
      2498325.00     13603025.01      2498125.00     13602125.00
      2497725.00     13601424.99
#Sta/Elev= 30
  4070.3  199.45  4080.9  199.25  4366.1  196.38  4550.5  196.11  4746.4  193.77
  4845.8  193.39  4915.3  192.69  4941.0  192.13  4961.5  190.13  5000.2  189.74
  5015.3  189.86  5021.8  191.75  5025.5  189.03  5025.8  188.53  5029.5  189.03
  5029.6  189.05  5037.6  190.78  5043.4  189.61  5049.9  191.93  5059.2  192.54
  5102.4  191.98  5145.6  193.24  5183.0  192.62  5234.1  193.72  5291.7  192.69
  5301.1  193.96  5306.8  193.33  5370.9  195.01  5570.3  197.83  5798.5  199.62
#Mann=8,-1,0
  4070.3    0.07       0  4080.9    0.05       0  4845.8    0.07       0
  4915.3    0.12       0  5025.5    0.05       0  5029.5    0.12       0
  5029.6    0.05       0  5370.9   0.035       0
Bank Sta=5025.5,5029.5
Exp/Cntr=0.3,0.1

Type RM Length L Ch R = 1,11870,443,443,443
BEGIN DESCRIPTION:
Stream0847 25.0
END DESCRIPTION:
XS GIS Cut Line= 3
      2499125.01     13602575.01      2498525.00     13601975.00
      2498175.01     13601625.01
#Sta/Elev= 30
  4147.1  198.29  4221.9  197.35  4222.3  197.34  4246.1  196.65  4274.4  194.69
  4288.5  195.52  4345.1  195.34  4599.7  192.40  4642.1  191.16  4705.1  191.69
  4769.4  190.23  4783.5  188.88  4797.6  189.40  4813.3  191.55  4854.2  192.25
  4931.9  191.16  4967.4  190.37  4992.1  187.54  5007.8  187.21  5008.0  186.71
  5011.8  187.21  5023.9  187.54  5054.3  190.20  5080.5  191.51  5108.8  191.68
  5236.1  195.24  5250.2  194.28  5264.3  194.41  5278.5  195.82  5490.6  197.86
#Mann=9,-1,0
  4147.1    0.05       0  4221.9    0.07       0  4222.3    0.05       0
  4705.1    0.12       0  4813.3    0.05       0  4931.9    0.12       0
  5007.8    0.05       0  5011.8    0.12       0  5054.3    0.05       0
Bank Sta=5007.8,5011.8
Exp/Cntr=0.3,0.1

Type RM Length L Ch R = 1,11427,467,467,467
BEGIN DESCRIPTION:
Stream0847 24.0
END DESCRIPTION:
XS GIS Cut Line= 3
      2499174.97     13601974.98      2498875.00     13601725.00
      2498625.03     13601525.02
#Sta/Elev= 30
  4604.6  195.09  4646.9  194.96  4675.5  193.90  4704.1  193.77  4725.0  192.93
  4841.2  191.26  4903.3  189.41  4917.0  187.89  4924.1  185.67  4930.6  186.41
  4938.5  188.08  4952.8  188.60  4967.1  187.45  4973.6  184.84  4981.4  185.54
  4985.9  184.26  4986.1  183.76  4989.7  183.76  4990.0  184.26  5002.3  184.79
  5008.7  186.71  5023.1  188.42  5066.3  189.73  5090.0  189.79  5101.5  189.57
  5109.5  190.80  5173.6  192.71  5251.2  193.56  5279.2  194.56  5315.2  194.77
#Mann=5,-1,0
  4604.6    0.07       0  4841.2    0.12       0  4985.9    0.05       0
  4990.0    0.12       0  5090.0    0.05       0
Bank Sta=4985.9,4990
Exp/Cntr=0.3,0.1

Type RM Length L Ch R = 1,10960,470,470,470
BEGIN DESCRIPTION:
Stream0847 23.0
END DESCRIPTION:
XS GIS Cut Line= 3
      2499874.99     13601924.99      2499075.00     13601325.00
      2497975.03     13601425.00
#Sta/Elev= 30
  3995.9  207.32  4038.6  206.37  4059.4  204.94  4117.8  202.99  4301.3  198.65
  4340.4  197.96  4520.0  194.81  4588.9  193.75  4838.0  189.98  4959.4  186.88
  4998.4  187.20  5005.9  184.11  5016.0  183.29  5044.0  183.14  5044.2  182.64
  5048.2  183.14  5064.1  183.54  5096.3  188.68  5116.4  192.94  5136.5  192.37
  5146.5  193.34  5206.8  191.64  5226.8  191.70  5427.7  194.88  5518.0  195.16
  5638.5  196.85  5838.4  197.54  5992.1  198.22  6018.9  198.47  6100.4  198.73
#Mann=12,-1,0
  3995.9    0.07       0  4301.3    0.12       0  4340.4    0.07       0
  4520.0    0.12       0  4588.9    0.07       0  4838.0   0.033       0
  5044.0   0.033       0  5048.2   0.033       0  5064.1    0.05       0
  5838.4   0.035       0  5992.1    0.05       0  6018.9   0.035       0
Bank Sta=5044,5048.2
Exp/Cntr=0.3,0.1

Type RM Length L Ch R = 1,10490,452,452,452
BEGIN DESCRIPTION:
Stream0847 22.0
END DESCRIPTION:
XS GIS Cut Line= 3
      2499774.98     13601274.99      2498975.00     13600925.00
      2498325.01     13601325.00
#Sta/Elev= 30
  4130.6  198.07  4366.4  192.98  4501.7  192.16  4523.5  190.57  4541.1  191.15
  4564.5  190.25  4569.9  191.86  4593.3  192.08  4692.3  190.28  4744.6  191.55
  4752.7  191.14  4791.3  183.08  4913.7  184.61  4924.1  183.97  4942.6  184.76
  4960.1  190.50  4971.4  190.38  4982.0  186.84  4989.4  183.13  4992.7  182.78
  4992.9  182.28  4997.0  182.78  5006.7  183.46  5011.5  185.28  5017.4  185.36
  5026.9  188.27  5103.3  190.19  5173.5  191.92  5353.5  194.93  5767.0  197.45
#Mann=6,-1,0
  4130.6    0.07       0  4924.1    0.05       0  4992.7    0.05       0
  4997.0    0.05       0  5103.3   0.035       0  5173.5    0.05       0
Bank Sta=4992.7,4997
Exp/Cntr=0.3,0.1

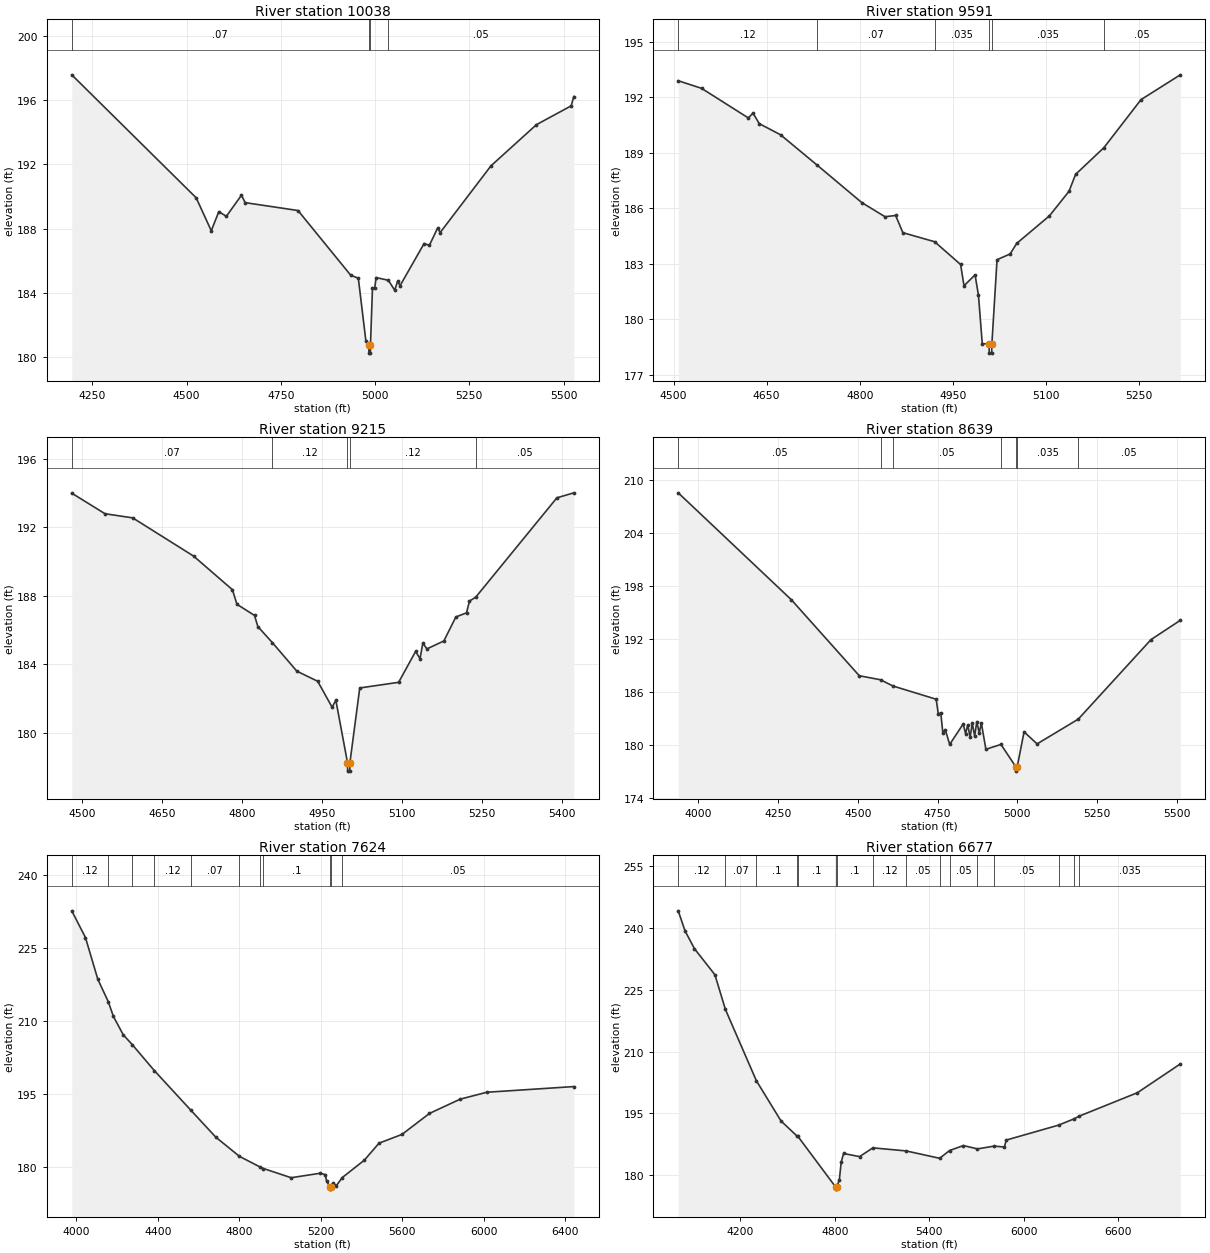
Type RM Length L Ch R = 1,10038,447,447,447
BEGIN DESCRIPTION:
Stream0847 21.0
END DESCRIPTION:
XS GIS Cut Line= 3
      2499875.05     13600575.00      2499075.00     13600575.00
      2498674.97     13600224.97
#Sta/Elev= 30
  4195.7  197.56  4525.7  189.91  4565.7  187.86  4585.7  189.05  4605.7  188.76
  4645.7  190.07  4655.7  189.61  4795.7  189.12  4935.7  185.09  4955.7  184.91
  4975.7  181.02  4983.5  180.75  4983.8  180.25  4987.6  180.25  4987.9  180.75
  4993.2  184.28  4999.1  184.28  5002.9  184.95  5035.5  184.78  5052.2  184.16
  5059.8  184.72  5066.5  184.45  5130.0  187.06  5144.3  186.96  5166.1  188.04
  5172.8  187.75  5307.5  191.90  5428.1  194.46  5520.1  195.63  5527.3  196.21
#Mann=4,-1,0
  4195.7    0.07       0  4983.5    0.05       0  4987.9    0.07       0
  5035.5    0.05       0
Bank Sta=4983.5,4987.9
Exp/Cntr=0.3,0.1

Type RM Length L Ch R = 1,9591,376,376,376
BEGIN DESCRIPTION:
Stream0847 20.0
END DESCRIPTION:
XS GIS Cut Line= 3
      2499675.01     13600375.00      2499225.00     13600175.00
      2498924.98     13600074.99
#Sta/Elev= 30
  4507.6  192.89  4545.2  192.48  4620.5  190.88  4628.0  191.14  4638.2  190.57
  4672.4  189.97  4731.0  188.34  4803.1  186.31  4840.7  185.54  4857.8  185.61
  4869.4  184.68  4920.6  184.19  4962.4  182.96  4967.9  181.81  4985.7  182.40
  4991.2  181.29  4997.3  178.68  5008.3  178.67  5008.6  178.17  5012.5  178.17
  5012.8  178.67  5021.1  183.22  5042.2  183.53  5052.8  184.10  5105.5  185.59
  5137.1  186.92  5147.6  187.83  5193.4  189.28  5253.0  191.87  5316.3  193.21
#Mann=6,-1,0
  4507.6    0.12       0  4731.0    0.07       0  4920.6   0.035       0
  5008.3   0.035       0  5012.8   0.035       0  5193.4    0.05       0
Bank Sta=5008.3,5012.8
Exp/Cntr=0.3,0.1

Type RM Length L Ch R = 1,9215,576,576,576
BEGIN DESCRIPTION:
Stream0847 19.0
END DESCRIPTION:
XS GIS Cut Line= 3
      2499825.05     13599975.01      2499246.19     13599811.73
      2498925.02     13599924.99
#Sta/Elev= 30
  4480.9  193.99  4543.3  192.79  4595.2  192.55  4709.5  190.32  4782.3  188.36
  4790.8  187.51  4823.8  186.86  4830.0  186.21  4857.4  185.27  4903.2  183.61
  4942.3  183.02  4969.3  181.51  4976.4  181.91  4998.2  178.28  4998.5  177.78
  5002.5  177.78  5002.8  178.28  5021.2  182.63  5094.2  182.96  5126.0  184.76
  5134.3  184.34  5139.6  185.25  5147.2  184.91  5179.0  185.37  5201.5  186.77
  5221.5  187.01  5227.1  187.70  5238.7  187.92  5391.1  193.72  5422.9  194.01
#Mann=5,-1,0
  4480.9    0.07       0  4857.4    0.12       0  4998.2    0.05       0
  5002.8    0.12       0  5238.7    0.05       0
Bank Sta=4998.2,5002.8
Exp/Cntr=0.3,0.1

Type RM Length L Ch R = 1,8639,1015,1015,1015
BEGIN DESCRIPTION:
Stream0847 18.0
END DESCRIPTION:
XS GIS Cut Line= 3
      2500074.97     13598575.02      2499275.00     13599275.00
      2498774.98     13599375.00
#Sta/Elev= 30
  3937.6  208.60  4292.1  196.46  4504.7  187.84  4571.3  187.38  4609.8  186.68
  4745.7  185.17  4752.4  183.47  4760.0  183.64  4766.6  181.34  4774.2  181.72
  4788.0  180.04  4830.2  182.36  4837.8  181.27  4844.5  182.26  4852.0  180.87
  4858.7  182.44  4866.3  181.00  4872.9  182.63  4880.5  181.34  4887.2  182.47
  4901.4  179.49  4948.7  180.04  4994.9  177.51  4995.3  177.01  4999.6  177.51
  5021.0  181.47  5061.8  180.10  5190.8  182.91  5418.7  191.94  5510.5  194.13
#Mann=7,-1,0
  3937.6    0.05       0  4571.3    0.12       0  4609.8    0.05       0
  4948.7   0.035       0  4994.9   0.035       0  4999.6   0.035       0
  5190.8    0.05       0
Bank Sta=4994.9,4999.6
Exp/Cntr=0.3,0.1

Type RM Length L Ch R = 1,7624,947,947,947
BEGIN DESCRIPTION:
XS7832
END DESCRIPTION:
XS GIS Cut Line= 3
      2499963.75     13598035.61      2498460.71     13598639.63
      2498516.81     13599481.19
#Sta/Elev= 30
  3977.7  232.68  4044.8  227.18  4105.7  218.56  4156.9  213.95  4181.9  210.93
  4230.2  207.14  4275.6  205.06  4382.8  199.76  4563.0  191.55  4684.5  186.04
  4800.5  182.09  4902.5  179.88  4917.9  179.59  5054.1  177.69  5197.9  178.62
  5222.1  178.31  5227.5  177.04  5243.8  175.84  5244.2  175.34  5248.8  175.84
  5258.9  176.55  5275.9  176.05  5304.4  177.71  5413.0  181.30  5485.2  184.81
  5597.6  186.61  5732.8  190.94  5883.1  193.87  6013.9  195.30  6441.0  196.47
#Mann=11,-1,0
  3977.7    0.12       0  4156.9    0.07       0  4275.6   0.035       0
  4382.8    0.12       0  4563.0    0.07       0  4800.5     0.1       0
  4902.5    0.07       0  4917.9     0.1       0  5243.8    0.05       0
  5248.8     0.1       0  5304.4    0.05       0
Bank Sta=5243.8,5248.8
Exp/Cntr=0.3,0.1

Type RM Length L Ch R = 1,6677,1166,1166,1166
BEGIN DESCRIPTION:
XS7831
END DESCRIPTION:
XS GIS Cut Line= 6
      2499897.97     13597816.38      2498869.57     13597811.24
      2498689.98     13597687.58      2498622.74     13597692.97
      2498350.21     13597759.82      2496929.76     13598485.03
#Sta/Elev= 30
  3806.1  244.16  3849.1  239.31  3909.1  234.98  4039.1  228.65  4105.7  220.24
  4302.4  202.95  4459.1  193.18  4560.2  189.54  4564.8  189.53  4806.3  177.15
  4806.7  176.65  4811.9  177.15  4829.1  178.79  4841.4  183.19  4856.3  185.30
  4957.8  184.53  5042.7  186.66  5253.7  185.92  5466.8  184.13  5529.9  186.02
  5617.6  187.22  5706.9  186.41  5812.7  187.08  5878.0  186.87  5889.9  188.55
  6221.9  192.17  6320.8  193.70  6354.9  194.38  6723.1  200.04  6995.5  207.02
#Mann=16,-1,0
  3806.1    0.12       0  4105.7    0.07       0  4302.4     0.1       0
  4560.2    0.12       0  4564.8     0.1       0  4806.3    0.05       0
  4811.9     0.1       0  5042.7    0.12       0  5253.7    0.05       0
  5466.8    0.12       0  5529.9    0.05       0  5706.9    0.12       0
  5812.7    0.05       0  6221.9   0.035       0  6320.8    0.05       0
  6354.9   0.035       0
Bank Sta=4806.3,4811.9
Exp/Cntr=0.3,0.1

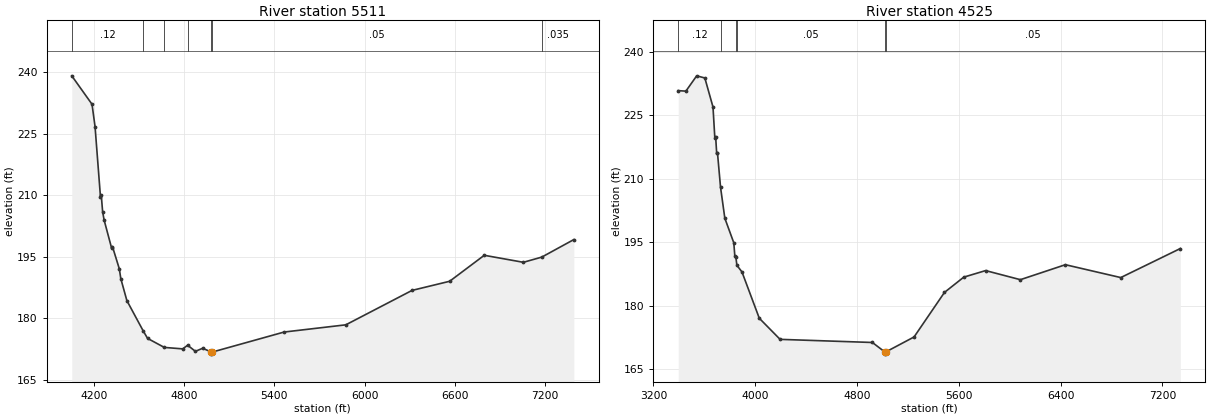
Type RM Length L Ch R = 1,5511,986,986,986
BEGIN DESCRIPTION:
XS7830
END DESCRIPTION:
XS GIS Cut Line= 3
      2499008.56     13597094.47      2498025.25     13596968.04
      2495679.71     13597066.36
#Sta/Elev= 30
  4053.2  239.17  4187.9  232.23  4208.0  226.79  4244.2  209.57  4249.2  210.10
  4258.4  206.01  4268.5  203.95  4318.7  197.05  4323.7  197.51  4369.3  192.08
  4379.4  189.66  4419.7  184.31  4527.2  176.99  4557.3  175.09  4668.5  172.89
  4790.9  172.53  4823.7  173.42  4875.4  171.93  4923.9  172.68  4981.6  171.75
  4982.0  171.25  4987.2  171.75  5465.2  176.64  5875.6  178.40  6316.0  186.80
  6566.2  189.03  6796.4  195.37  7056.6  193.66  7179.0  194.93  7392.2  199.21
#Mann=7,-1,0
  4053.2    0.12       0  4527.2     0.1       0  4668.5    0.12       0
  4823.7    0.05       0  4981.6    0.05       0  4987.2    0.05       0
  7179.0   0.035       0
Bank Sta=4981.6,4987.2
Exp/Cntr=0.3,0.1

Type RM Length L Ch R = 1,4525,0,0,0
BEGIN DESCRIPTION:
XS7829
END DESCRIPTION:
XS GIS Cut Line= 3
      2499219.22     13597164.67      2498418.56     13596153.31
      2495791.77     13595760.00
#Sta/Elev= 30
  3394.5  230.86  3454.6  230.74  3539.5  234.36  3603.6  233.85  3667.7  226.99
  3682.1  219.69  3688.5  220.01  3696.6  216.08  3703.0  216.14  3726.9  208.04
  3760.7  200.71  3831.2  194.90  3839.2  191.83  3847.2  191.57  3855.4  189.59
  3895.3  188.03  4031.5  177.08  4195.0  172.09  4920.6  171.35  5018.7  169.10
  5019.2  168.60  5024.8  169.10  5248.1  172.66  5486.8  183.18  5638.5  186.79
  5810.4  188.34  6083.4  186.19  6437.3  189.73  6872.5  186.69  7340.5  193.55
#Mann=6,-1,0
  3394.5    0.12       0  3726.9    0.05       0  3847.2    0.12       0
  3855.4    0.05       0  5018.7    0.05       0  5024.8    0.05       0
Bank Sta=5018.7,5024.8
Exp/Cntr=0.3,0.1

Chan Stop Cuts=-1