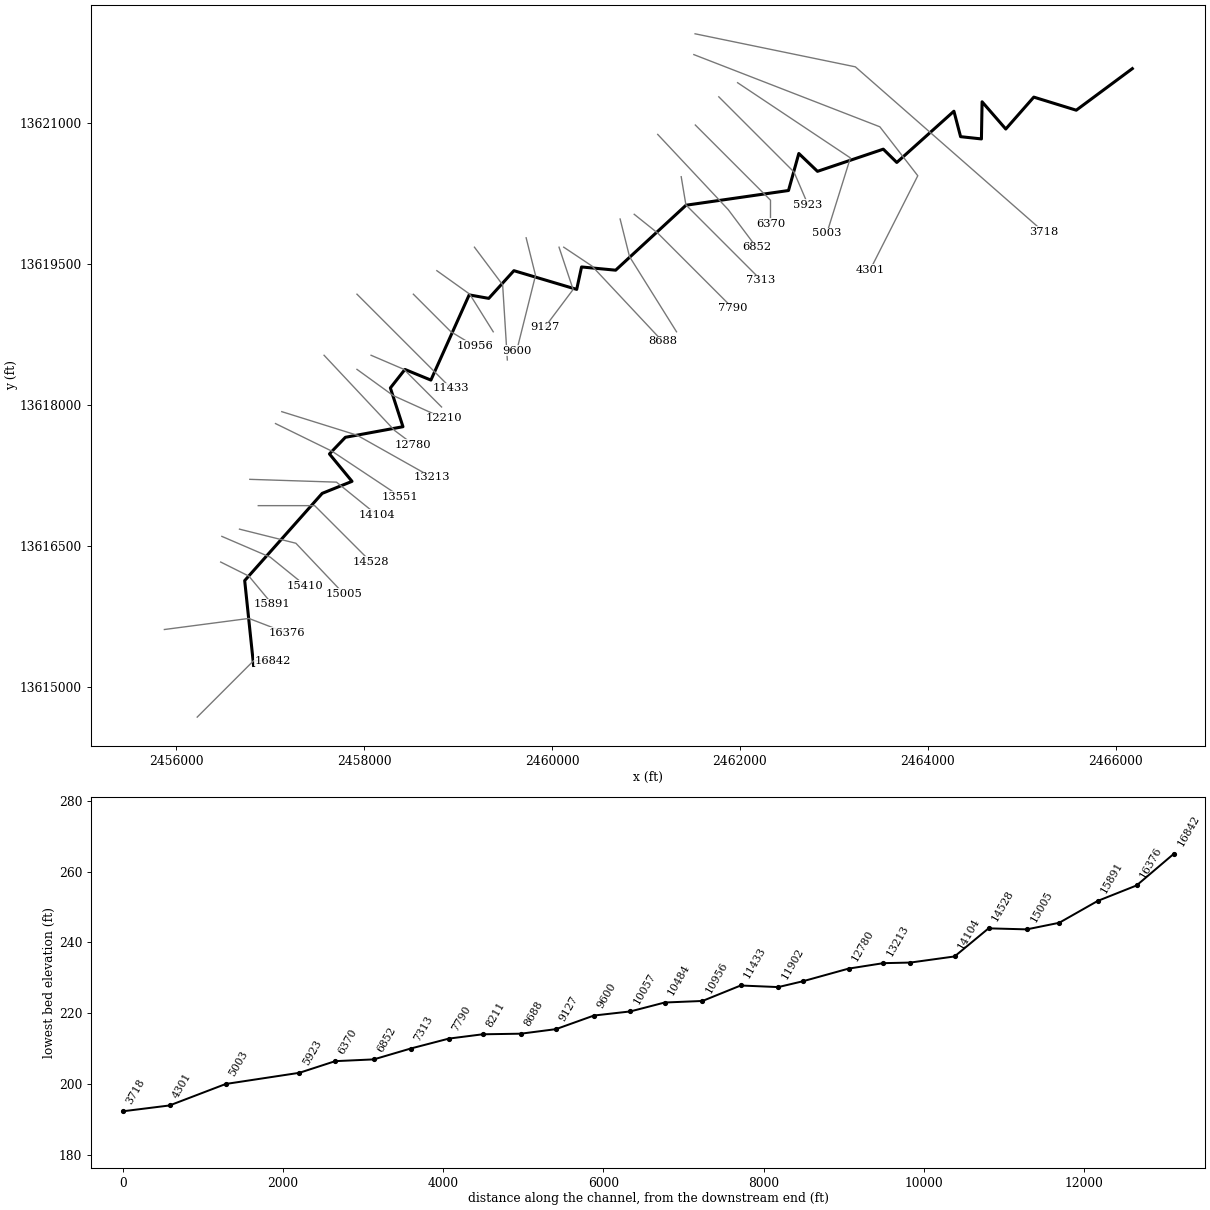
--- THOMAS HOLLOW.prj (project) ---

Proj Title=THOMAS HOLLOW Base Level Engineering
Current Plan=p01
Default Exp/Contr=0.3,0.1
English Units
Geom File=g01
Flow File=f01
Plan File=p01
BEGIN DESCRIPTION:
THOMAS HOLLOW
END DESCRIPTION:

--- THOMAS HOLLOW.p01 (plan) ---

Plan Title=Multiple Run
Short Identifier=Multiple
Geom File=g01
Flow File=f01
Subcritical Flow
K Sum by GR= 0
Std Step Tol= 0.01
Critical Tol= 0.01
Num of Std Step Trials= 20
Max Error Tol= 0.3
Flow Tol Ratio= 0.001
Split Flow NTrial= 30
Split Flow Tol= 0.02
Split Flow Ratio= 0.02
Log Output Level= 0
Friction Slope Method= 1
Unsteady Friction Slope Method= 2
Unsteady Bridges Friction Slope Method= 1
Parabolic Critical Depth
Global Vel Dist=  1 , 1 , 1
Global Log Level= 0
CheckData=True
Encroach Param= -1, 0, 0, 0
BEGIN DESCRIPTION:
Multiple Run
END DESCRIPTION:

--- THOMAS HOLLOW.f01 (steady flow) ---

Flow Title=Multiple
Number of Profiles=7
Profile Names=10-year,25-year,50-year,1pct_min,100-year,1pct_plu,500-year
River Rch & RM= THOMAS HOLLOW,Reach-1,16842
     357     556     731     466     930    1856    1491
River Rch & RM= THOMAS HOLLOW,Reach-1,15891
     823    1353    1841    1213    2421    4830    4145
River Rch & RM= THOMAS HOLLOW,Reach-1,13551
    1110    1844    2527    1674    3339    6663    5782
Boundary for River Rch & Prof#=THOMAS HOLLOW,Reach-1,1
Up Type=0
Dn Type=3
Dn Slope=0.005
Boundary for River Rch & Prof#=THOMAS HOLLOW,Reach-1,2
Up Type=0
Dn Type=3
Dn Slope=0.005
Boundary for River Rch & Prof#=THOMAS HOLLOW,Reach-1,3
Up Type=0
Dn Type=3
Dn Slope=0.005
Boundary for River Rch & Prof#=THOMAS HOLLOW,Reach-1,4
Up Type=0
Dn Type=3
Dn Slope=0.005
Boundary for River Rch & Prof#=THOMAS HOLLOW,Reach-1,5
Up Type=0
Dn Type=3
Dn Slope=0.005
Boundary for River Rch & Prof#=THOMAS HOLLOW,Reach-1,6
Up Type=0
Dn Type=3
Dn Slope=0.005
Boundary for River Rch & Prof#=THOMAS HOLLOW,Reach-1,7
Up Type=0
Dn Type=3
Dn Slope=0.005

--- THOMAS HOLLOW.g01 (geometry) ---

Geom Title=Existing Conditions

River Reach=THOMAS HOLLOW,Reach-1
Reach XY= 30
      2456825.00     13615225.00      2456730.39     13616127.44
      2457554.96     13617055.65      2457872.42     13617183.48
      2457632.07     13617475.00      2457801.47     13617652.14
      2458414.39     13617764.89      2458280.41     13618177.42
      2458435.33     13618374.13      2458711.63     13618260.84
      2459118.92     13619167.53      2459327.43     13619130.40
      2459594.98     13619425.05      2460263.03     13619226.17
      2460314.76     13619464.66      2460677.43     13619430.40
      2461426.25     13620121.64      2462516.68     13620278.16
      2462626.43     13620672.02      2462824.98     13620482.08
      2463525.22     13620718.00      2463668.91     13620576.57
      2464276.67     13621121.92      2464347.63     13620850.98
      2464569.36     13620826.97      2464576.40     13621222.00
      2464828.41     13620932.38      2465126.64     13621271.86
      2465578.34     13621132.60      2466175.00     13621575.00

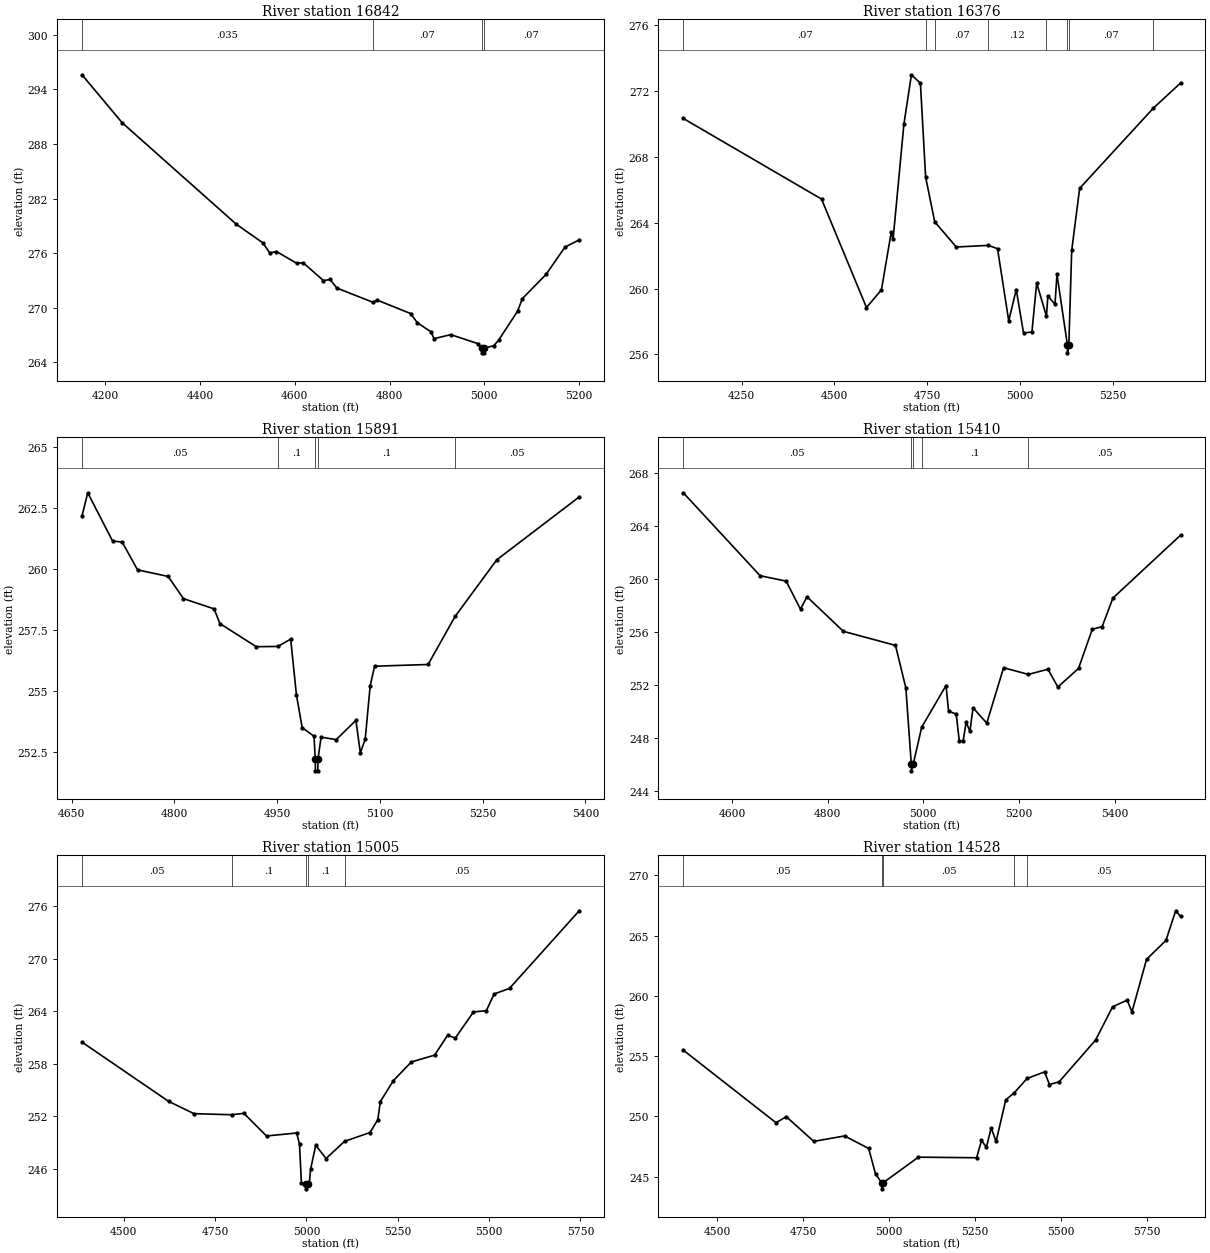
Type RM Length L Ch R = 1,16842,466,466,466
BEGIN DESCRIPTION:
THOMAS HOLLOW 28.0
END DESCRIPTION:
XS GIS Cut Line= 3
      2456225.02     13614675.02      2456825.00     13615275.00
      2457025.01     13615275.00
#Sta/Elev= 30
  4151.5  295.61  4236.3  290.34  4476.7  279.20  4533.3  277.13  4547.4  276.04
  4561.6  276.19  4604.0  274.91  4618.2  274.95  4660.6  273.00  4674.7  273.12
  4688.9  272.18  4765.2  270.61  4773.7  270.86  4844.4  269.38  4858.6  268.37
  4886.9  267.39  4893.9  266.62  4929.3  267.06  4985.9  266.08  4994.5  265.56
  4994.7  265.06  4998.2  265.06  4998.5  265.56  5020.0  265.85  5030.0  266.45
  5070.0  269.63  5080.0  271.01  5130.0  273.67  5170.0  276.68  5200.0  277.47
#Mann=4,-1,0
  4151.5   0.035       0  4765.2    0.07       0  4994.5    0.05       0
  4998.5    0.07       0
Bank Sta=4994.5,4998.5
Exp/Cntr=0.3,0.1

Type RM Length L Ch R = 1,16376,485,485,485
BEGIN DESCRIPTION:
THOMAS HOLLOW 27.0
END DESCRIPTION:
XS GIS Cut Line= 3
      2455875.83     13615607.01      2456775.00     13615725.00
      2457178.72     13615569.80
#Sta/Elev= 30
  4093.2  270.32  4465.5  265.43  4586.6  258.85  4626.9  259.92  4653.2  263.41
  4658.2  262.98  4687.4  269.97  4707.6  272.97  4731.9  272.46  4745.9  266.77
  4770.4  264.05  4828.6  262.52  4914.6  262.62  4939.6  262.42  4969.8  258.04
  4990.0  259.94  5009.7  257.30  5032.2  257.37  5045.1  260.33  5071.4  258.32
  5075.1  259.54  5094.4  259.05  5099.7  260.87  5127.7  256.60  5128.0  256.10
  5131.7  256.60  5139.4  262.31  5160.8  266.08  5359.5  270.95  5432.6  272.47
#Mann=8,-1,0
  4093.2    0.07       0  4745.9     0.1       0  4770.4    0.07       0
  4914.6    0.12       0  5071.4    0.07       0  5127.7    0.05       0
  5131.7    0.07       0  5359.5    0.05       0
Bank Sta=5127.7,5131.7
Exp/Cntr=0.3,0.1

Type RM Length L Ch R = 1,15891,481,481,481
BEGIN DESCRIPTION:
THOMAS HOLLOW 26.0
END DESCRIPTION:
XS GIS Cut Line= 3
      2456474.98     13616325.01      2456775.00     13616175.00
      2457024.97     13615875.03
#Sta/Elev= 30
  4665.1  262.17  4673.5  263.13  4709.8  261.15  4723.8  261.11  4746.2  259.97
  4790.9  259.70  4813.3  258.79  4858.0  258.37  4866.4  257.77  4919.5  256.82
  4951.1  256.83  4969.8  257.13  4978.2  254.84  4986.6  253.50  5003.8  253.15
  5005.7  252.23  5005.9  251.73  5009.4  251.73  5009.7  252.23  5014.2  253.11
  5036.3  253.01  5065.0  253.80  5071.5  252.47  5078.6  253.03  5085.8  255.21
  5092.3  256.02  5170.4  256.09  5209.8  258.06  5270.6  260.38  5391.0  262.96
#Mann=5,-1,0
  4665.1    0.05       0  4951.1     0.1       0  5005.7    0.05       0
  5009.7     0.1       0  5209.8    0.05       0
Bank Sta=5005.7,5009.7
Exp/Cntr=0.3,0.1

Type RM Length L Ch R = 1,15410,405,405,405
BEGIN DESCRIPTION:
THOMAS HOLLOW 25.0
END DESCRIPTION:
XS GIS Cut Line= 3
      2456487.42     13616597.95      2457002.94     13616376.25
      2457375.00     13616075.00
#Sta/Elev= 30
  4498.0  266.54  4658.6  260.28  4713.1  259.87  4743.1  257.75  4756.6  258.69
  4832.8  256.08  4941.7  255.02  4963.4  251.81  4974.8  246.05  4975.0  245.55
  4978.8  246.05  4996.6  248.85  5047.4  251.99  5052.8  250.05  5068.7  249.84
  5075.1  247.82  5083.1  247.77  5089.5  249.23  5097.4  248.53  5103.9  250.31
  5132.6  249.15  5167.8  253.33  5219.7  252.83  5260.5  253.22  5281.3  251.88
  5324.5  253.28  5353.2  256.23  5374.0  256.44  5396.4  258.59  5537.9  263.34
#Mann=5,-1,0
  4498.0    0.05       0  4974.8    0.05       0  4978.8    0.05       0
  4996.6     0.1       0  5219.7    0.05       0
Bank Sta=4974.8,4978.8
Exp/Cntr=0.3,0.1

Type RM Length L Ch R = 1,15005,477,477,477
BEGIN DESCRIPTION:
THOMAS HOLLOW 24.0
END DESCRIPTION:
XS GIS Cut Line= 3
      2456674.99     13616675.00      2457275.00     13616525.00
      2457785.56     13615986.27
#Sta/Elev= 30
  4385.9  260.48  4623.0  253.70  4692.6  252.29  4795.5  252.17  4829.1  252.33
  4891.0  249.74  4973.5  250.08  4981.2  248.79  4986.3  244.41  4999.8  244.19
  5000.0  243.69  5003.8  244.19  5007.8  244.19  5011.5  245.93  5025.6  248.68
  5053.9  247.16  5104.5  249.13  5174.1  250.13  5195.5  251.61  5202.4  253.67
  5238.0  256.07  5287.3  258.21  5350.9  258.99  5386.4  261.27  5407.5  260.94
  5457.2  263.93  5492.4  264.08  5513.9  265.99  5555.9  266.63  5746.6  275.51
#Mann=5,-1,0
  4385.9    0.05       0  4795.5     0.1       0  4999.8    0.05       0
  5003.8     0.1       0  5104.5    0.05       0
Bank Sta=4999.8,5003.8
Exp/Cntr=0.3,0.1

Type RM Length L Ch R = 1,14528,424,424,424
BEGIN DESCRIPTION:
THOMAS HOLLOW 23.0
END DESCRIPTION:
XS GIS Cut Line= 3
      2456874.97     13616925.00      2457475.00     13616925.00
      2458075.03     13616324.97
#Sta/Elev= 30
  4400.4  255.49  4670.4  249.47  4700.4  249.97  4780.4  247.92  4870.4  248.37
  4940.4  247.33  4960.4  245.21  4978.4  244.48  4978.7  243.98  4982.4  244.48
  5085.3  246.61  5255.0  246.56  5269.1  248.00  5283.3  247.43  5297.4  249.04
  5311.6  247.91  5339.8  251.37  5363.9  251.93  5401.7  253.14  5453.0  253.69
  5467.1  252.63  5495.4  252.87  5601.5  256.33  5651.0  259.09  5693.4  259.64
  5707.5  258.67  5750.0  263.03  5806.5  264.60  5834.8  267.06  5849.0  266.59
#Mann=5,-1,0
  4400.4    0.05       0  4978.4    0.05       0  4982.4    0.05       0
  5363.9    0.07       0  5401.7    0.05       0
Bank Sta=4978.4,4982.4
Exp/Cntr=0.3,0.1

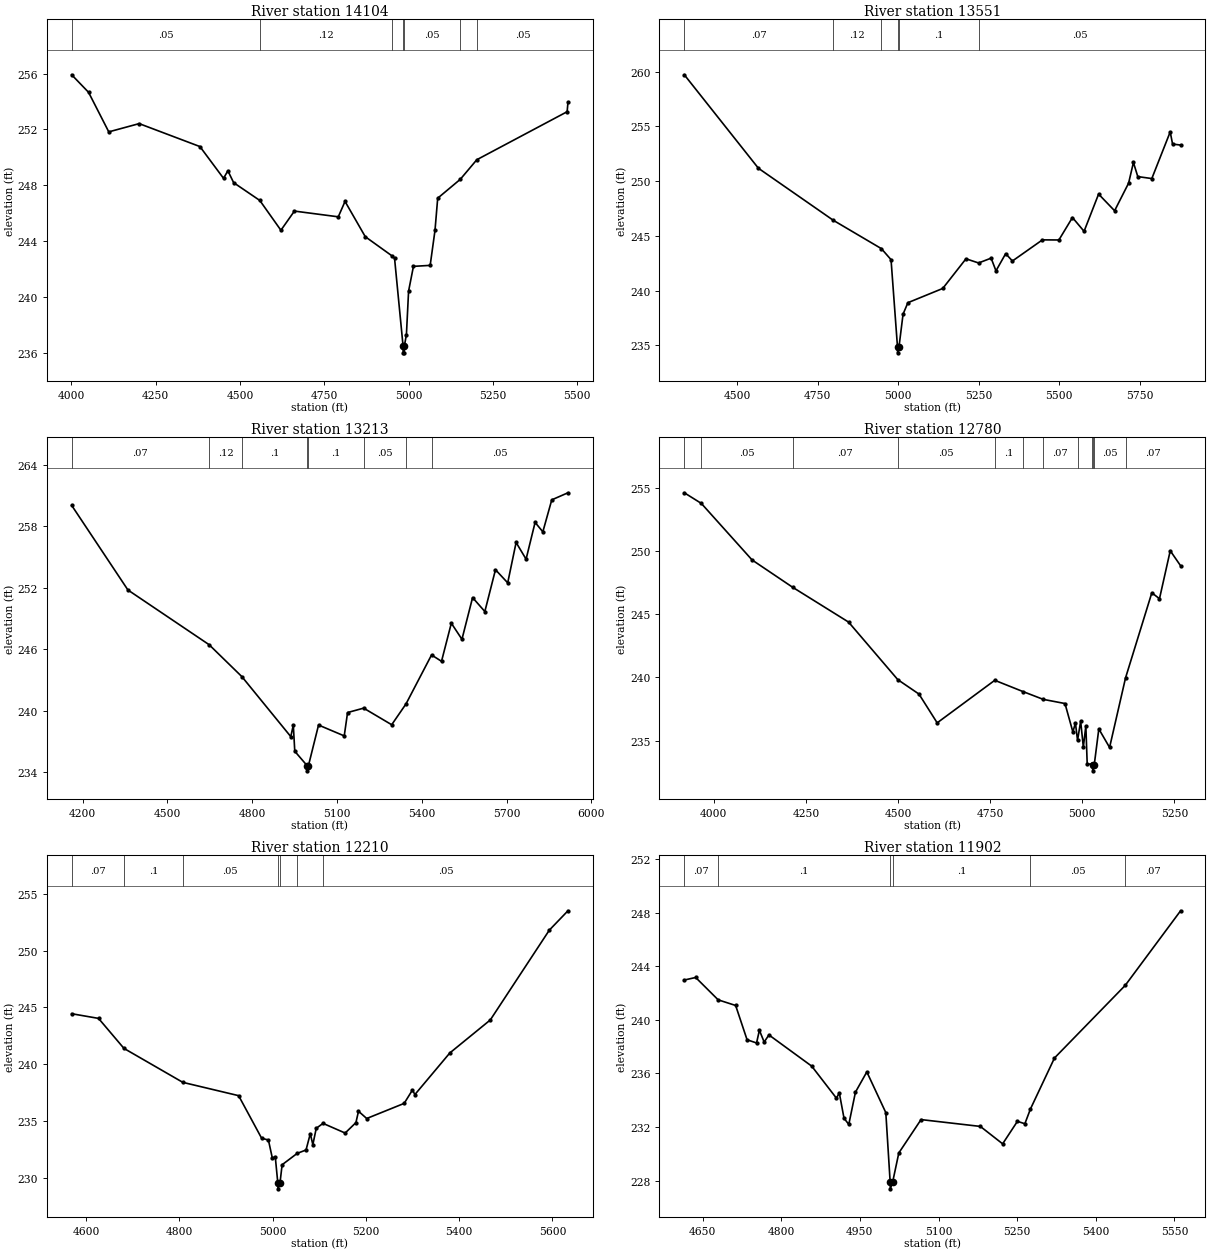
Type RM Length L Ch R = 1,14104,553,553,553
BEGIN DESCRIPTION:
THOMAS HOLLOW 22.0
END DESCRIPTION:
XS GIS Cut Line= 3
      2456785.02     13617204.93      2457707.08     13617175.05
      2458133.49     13616829.65
#Sta/Elev= 30
  4001.3  255.91  4051.3  254.66  4111.3  251.83  4201.4  252.42  4381.5  250.78
  4451.5  248.51  4464.4  249.05  4481.5  248.20  4559.0  246.93  4621.6  244.80
  4661.6  246.17  4791.7  245.76  4811.7  246.86  4871.7  244.34  4950.9  242.97
  4958.5  242.80  4983.7  236.54  4984.0  236.04  4987.5  236.04  4987.7  236.54
  4993.7  237.35  5000.1  240.45  5014.5  242.22  5064.1  242.29  5078.4  244.79
  5086.4  247.09  5153.4  248.44  5202.4  249.84  5470.1  253.27  5472.6  253.93
#Mann=7,-1,0
  4001.3    0.05       0  4559.0    0.12       0  4950.9    0.05       0
  4983.7    0.05       0  4987.7    0.05       0  5153.4    0.12       0
  5202.4    0.05       0
Bank Sta=4983.7,4987.7
Exp/Cntr=0.3,0.1

Type RM Length L Ch R = 1,13551,338,338,338
BEGIN DESCRIPTION:
THOMAS HOLLOW 21.0
END DESCRIPTION:
XS GIS Cut Line= 3
      2457058.25     13617798.26      2457660.12     13617503.73
      2458385.77     13617021.39
#Sta/Elev= 30
  4335.4  259.71  4565.6  251.17  4798.0  246.42  4947.4  243.83  4977.5  242.82
  4997.6  234.81  4997.9  234.31  5002.0  234.81  5014.8  237.84  5029.8  238.89
  5138.0  240.19  5210.2  242.90  5249.4  242.52  5288.3  242.96  5303.4  241.80
  5333.5  243.37  5354.5  242.70  5447.7  244.63  5498.8  244.62  5540.9  246.67
  5577.0  245.41  5622.1  248.81  5671.8  247.29  5715.3  249.81  5730.3  251.70
  5743.8  250.41  5787.4  250.23  5844.5  254.49  5851.9  253.38  5876.8  253.29
#Mann=6,-1,0
  4335.4    0.07       0  4798.0    0.12       0  4947.4     0.1       0
  4997.6    0.05       0  5002.0     0.1       0  5249.4    0.05       0
Bank Sta=4997.6,5002
Exp/Cntr=0.3,0.1

Type RM Length L Ch R = 1,13213,433,433,433
BEGIN DESCRIPTION:
THOMAS HOLLOW 20.0
END DESCRIPTION:
XS GIS Cut Line= 3
      2457125.00     13617925.00      2457925.00     13617675.00
      2458724.97     13617225.02
#Sta/Elev= 30
  4161.2  260.05  4360.3  251.79  4647.6  246.45  4763.6  243.33  4936.5  237.48
  4945.4  238.60  4950.6  236.05  4994.5  234.64  4994.8  234.14  4998.9  234.64
  5034.7  238.61  5125.6  237.55  5137.4  239.83  5194.3  240.26  5293.5  238.64
  5344.1  240.67  5434.5  245.45  5469.8  244.83  5504.5  248.55  5542.1  246.98
  5579.7  251.05  5623.1  249.69  5660.7  253.77  5704.0  252.49  5733.7  256.43
  5769.0  254.80  5800.9  258.39  5828.3  257.47  5859.9  260.59  5917.2  261.28
#Mann=8,-1,0
  4161.2    0.07       0  4647.6    0.12       0  4763.6     0.1       0
  4994.5    0.05       0  4998.9     0.1       0  5194.3    0.05       0
  5344.1    0.07       0  5434.5    0.05       0
Bank Sta=4994.5,4998.9
Exp/Cntr=0.3,0.1

Type RM Length L Ch R = 1,12780,570,570,570
BEGIN DESCRIPTION:
THOMAS HOLLOW 19.0
END DESCRIPTION:
XS GIS Cut Line= 3
      2457574.98     13618525.02      2458325.00     13617725.00
      2458524.99     13617575.01
#Sta/Elev= 30
  3920.0  254.62  3966.1  253.78  4103.9  249.30  4213.8  247.14  4365.7  244.38
  4499.3  239.82  4556.7  238.68  4606.1  236.40  4762.4  239.77  4838.7  238.88
  4893.9  238.26  4952.9  237.93  4974.3  235.68  4981.2  236.39  4987.0  235.01
  4995.4  236.53  5002.7  234.48  5009.5  236.16  5013.2  233.13  5027.2  233.14
  5027.9  233.10  5028.2  232.60  5032.4  233.10  5044.7  235.92  5073.9  234.45
  5117.2  239.96  5188.5  246.70  5209.3  246.23  5238.5  250.03  5266.6  248.84
#Mann=12,-1,0
  3920.0    0.07       0  3966.1    0.05       0  4213.8    0.07       0
  4499.3    0.05       0  4762.4     0.1       0  4838.7    0.05       0
  4893.9    0.07       0  4987.0     0.1       0  5027.2    0.05       0
  5027.9    0.05       0  5032.4    0.05       0  5117.2    0.07       0
Bank Sta=5027.9,5032.4
Exp/Cntr=0.3,0.1

Type RM Length L Ch R = 1,12210,308,308,308
BEGIN DESCRIPTION:
THOMAS HOLLOW 18.0
END DESCRIPTION:
XS GIS Cut Line= 3
      2457925.00     13618375.00      2458308.95     13618097.06
      2458846.79     13617853.75
#Sta/Elev= 30
  4569.0  244.44  4626.6  244.03  4681.1  241.39  4807.4  238.40  4927.0  237.23
  4976.4  233.48  4990.9  233.33  4999.4  231.72  5005.6  231.86  5011.1  229.53
  5011.5  229.03  5015.7  229.53  5020.3  231.15  5052.6  232.15  5071.6  232.45
  5080.7  233.88  5086.2  232.92  5093.5  234.36  5108.1  234.79  5155.5  233.94
  5178.6  234.86  5184.1  235.86  5201.7  235.22  5282.0  236.55  5299.7  237.72
  5305.1  237.33  5380.0  240.99  5466.7  243.89  5593.4  251.80  5633.3  253.50
#Mann=7,-1,0
  4569.0    0.07       0  4681.1     0.1       0  4807.4    0.05       0
  5011.1    0.05       0  5015.7    0.05       0  5052.6     0.1       0
  5108.1    0.05       0
Bank Sta=5011.1,5015.7
Exp/Cntr=0.3,0.1

Type RM Length L Ch R = 1,11902,469,469,469
BEGIN DESCRIPTION:
THOMAS HOLLOW 17.0
END DESCRIPTION:
XS GIS Cut Line= 3
      2458075.01     13618525.00      2458425.00     13618375.00
      2458825.03     13617974.97
#Sta/Elev= 30
  4615.2  242.97  4636.9  243.16  4679.8  241.49  4713.1  241.07  4734.9  238.51
  4753.0  238.27  4758.4  239.22  4767.5  238.34  4776.6  238.87  4858.2  236.54
  4905.3  234.15  4910.8  234.54  4919.8  232.65  4928.9  232.19  4941.6  234.60
  4963.3  236.11  4999.5  233.07  5007.8  227.88  5008.1  227.38  5012.5  227.88
  5024.3  230.06  5066.7  232.55  5179.8  232.04  5222.3  230.74  5250.5  232.42
  5264.7  232.24  5275.3  233.34  5321.2  237.15  5456.1  242.57  5561.7  248.14
#Mann=6,-1,0
  4615.2    0.07       0  4679.8     0.1       0  5007.8    0.05       0
  5012.5     0.1       0  5275.3    0.05       0  5456.1    0.07       0
Bank Sta=5007.8,5012.5
Exp/Cntr=0.3,0.1

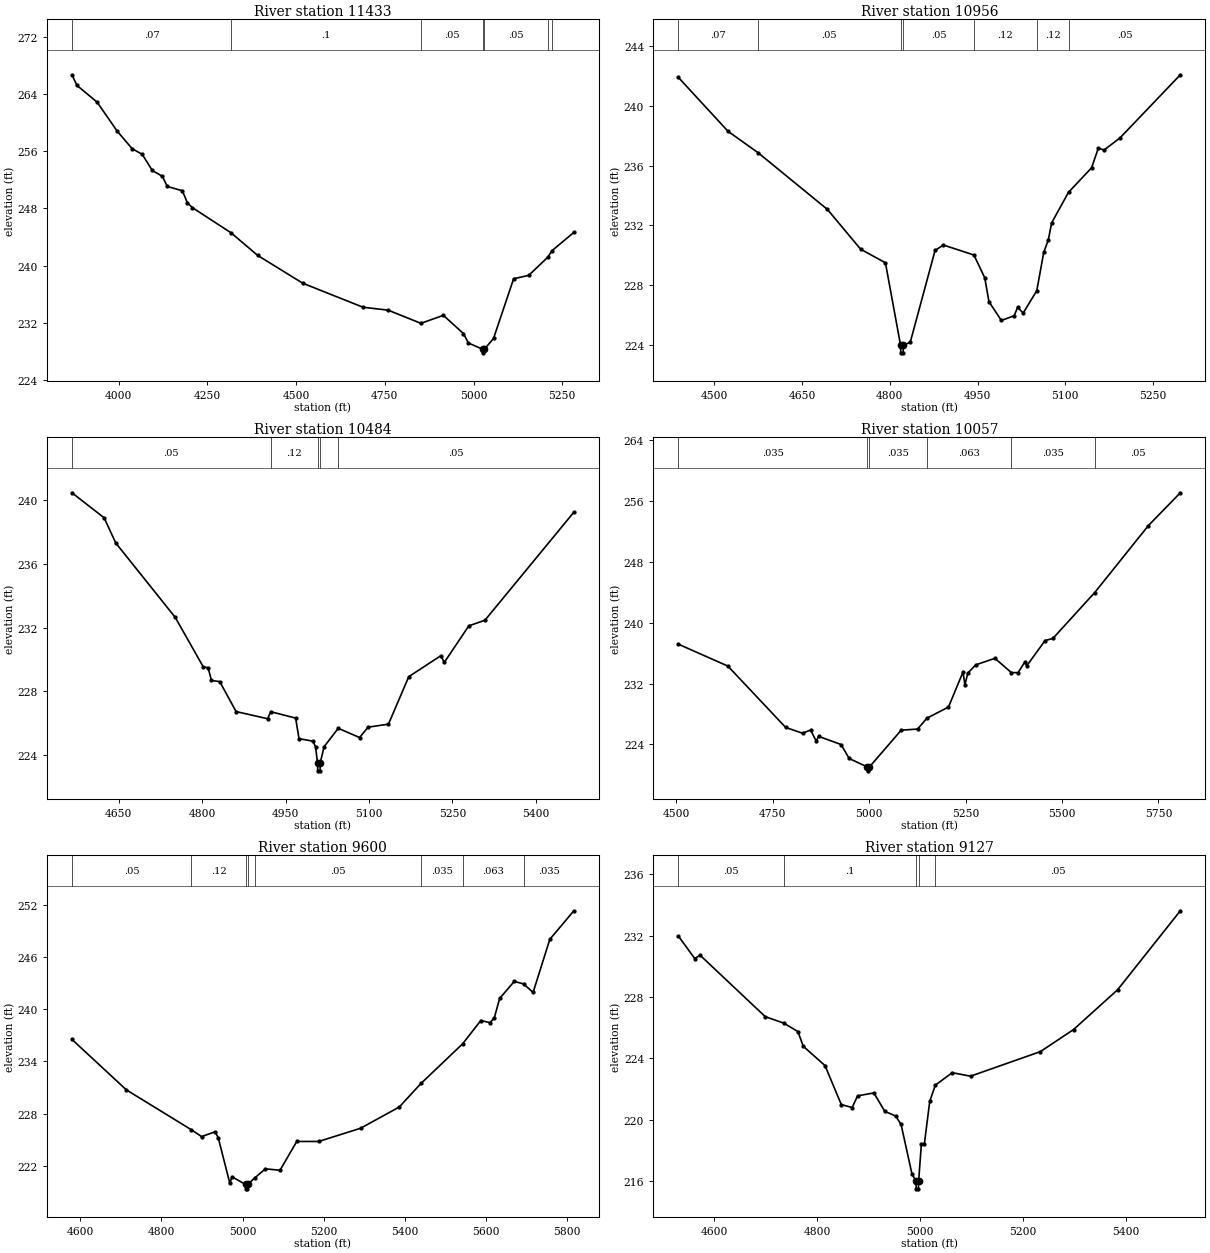
Type RM Length L Ch R = 1,11433,477,477,477
BEGIN DESCRIPTION:
THOMAS HOLLOW 16.0
END DESCRIPTION:
XS GIS Cut Line= 3
      2457925.00     13619175.00      2458725.00     13618375.00
      2458924.99     13618175.01
#Sta/Elev= 30
  3868.5  266.67  3882.6  265.18  3939.2  262.86  3995.8  258.81  4038.2  256.34
  4066.5  255.56  4094.8  253.31  4123.1  252.49  4137.2  251.07  4179.6  250.47
  4193.8  248.78  4207.9  248.11  4316.7  244.60  4391.8  241.44  4519.0  237.55
  4688.7  234.20  4759.5  233.79  4851.8  231.95  4915.0  233.07  4971.6  230.52
  4985.7  229.20  5025.8  228.33  5026.1  227.83  5030.6  228.33  5056.4  229.84
  5113.0  238.18  5155.4  238.65  5209.6  241.20  5221.3  242.11  5282.7  244.65
#Mann=7,-1,0
  3868.5    0.07       0  4316.7     0.1       0  4851.8    0.05       0
  5025.8    0.05       0  5030.6    0.05       0  5209.6    0.07       0
  5221.3    0.05       0
Bank Sta=5025.8,5030.6
Exp/Cntr=0.3,0.1

Type RM Length L Ch R = 1,10956,472,472,472
BEGIN DESCRIPTION:
THOMAS HOLLOW 15.0
END DESCRIPTION:
XS GIS Cut Line= 3
      2458524.98     13619175.02      2458925.00     13618775.00
      2459175.04     13618624.98
#Sta/Elev= 30
  4439.1  241.90  4524.0  238.29  4575.2  236.86  4693.7  233.06  4750.3  230.40
  4792.7  229.49  4818.6  223.96  4818.9  223.46  4823.0  223.46  4823.4  223.96
  4835.1  224.17  4877.5  230.32  4891.7  230.68  4943.9  230.01  4962.4  228.48
  4969.5  226.89  4990.7  225.63  5012.6  225.94  5018.4  226.50  5028.1  226.13
  5051.2  227.62  5063.1  230.18  5070.9  231.03  5076.7  232.17  5105.4  234.21
  5144.8  235.85  5156.4  237.17  5166.1  237.04  5193.3  237.85  5296.4  242.08
#Mann=7,-1,0
  4439.1    0.07       0  4575.2    0.05       0  4818.6    0.05       0
  4823.4    0.05       0  4943.9    0.12       0  5051.2    0.12       0
  5105.4    0.05       0
Bank Sta=4818.6,4823.4
Exp/Cntr=0.3,0.1

Type RM Length L Ch R = 1,10484,427,427,427
BEGIN DESCRIPTION:
THOMAS HOLLOW 14.0
END DESCRIPTION:
XS GIS Cut Line= 3
      2458774.99     13619425.01      2459125.00     13619175.00
      2459374.99     13618775.02
#Sta/Elev= 30
  4566.3  240.47  4624.1  238.90  4645.0  237.32  4751.9  232.65  4802.3  229.54
  4810.9  229.49  4817.0  228.69  4831.8  228.62  4861.2  226.74  4917.8  226.29
  4923.5  226.73  4968.2  226.33  4974.3  225.04  4999.4  224.88  5004.1  224.51
  5007.5  223.52  5007.9  223.02  5012.1  223.02  5012.4  223.52  5019.4  224.54
  5044.8  225.69  5083.1  225.11  5098.4  225.76  5135.0  225.95  5171.5  228.93
  5229.3  230.25  5235.2  229.82  5279.4  232.12  5308.3  232.47  5468.1  239.25
#Mann=5,-1,0
  4566.3    0.05       0  4923.5    0.12       0  5007.5    0.05       0
  5012.4    0.12       0  5044.8    0.05       0
Bank Sta=5007.5,5012.4
Exp/Cntr=0.3,0.1

Type RM Length L Ch R = 1,10057,457,457,457
BEGIN DESCRIPTION:
THOMAS HOLLOW 13.0
END DESCRIPTION:
XS GIS Cut Line= 3
      2459174.98     13619675.03      2459475.00     13619275.00
      2459525.00     13618475.00
#Sta/Elev= 30
  4505.2  237.18  4633.4  234.30  4783.4  226.22  4827.1  225.46  4847.9  225.88
  4862.5  224.44  4868.8  225.05  4927.1  223.97  4947.9  222.14  4995.4  221.01
  4995.8  220.51  5000.4  221.01  5082.9  225.86  5125.5  226.01  5149.7  227.44
  5205.6  228.91  5243.2  233.51  5248.2  231.85  5255.7  233.37  5275.8  234.45
  5325.9  235.32  5368.7  233.44  5386.0  233.43  5403.5  234.83  5408.5  234.33
  5456.1  237.66  5476.2  237.93  5584.7  243.97  5724.1  252.80  5806.8  257.11
#Mann=6,-1,0
  4505.2   0.035       0  4995.4   0.035       0  5000.4   0.035       0
  5149.7   0.063       0  5368.7   0.035       0  5584.7    0.05       0
Bank Sta=4995.4,5000.4
Exp/Cntr=0.3,0.1

Type RM Length L Ch R = 1,9600,473,473,473
BEGIN DESCRIPTION:
THOMAS HOLLOW 12.0
END DESCRIPTION:
XS GIS Cut Line= 3
      2459725.00     13619774.99      2459825.00     13619375.00
      2459625.01     13618575.02
#Sta/Elev= 30
  4579.4  236.53  4713.4  230.73  4873.9  226.13  4898.9  225.35  4932.4  225.91
  4940.2  225.17  4968.5  219.97  4973.7  220.73  5007.2  219.84  5007.6  219.34
  5011.9  219.34  5012.3  219.84  5030.5  220.62  5056.1  221.64  5092.2  221.48
  5133.4  224.79  5187.5  224.79  5290.6  226.31  5386.0  228.75  5439.7  231.47
  5541.9  236.01  5587.0  238.70  5610.2  238.46  5620.5  239.05  5633.4  241.25
  5669.4  243.20  5692.4  242.92  5715.8  241.93  5757.1  248.05  5816.3  251.33
#Mann=8,-1,0
  4579.4    0.05       0  4873.9    0.12       0  5007.2    0.05       0
  5012.3    0.12       0  5030.5    0.05       0  5439.7   0.035       0
  5541.9   0.063       0  5692.4   0.035       0
Bank Sta=5007.2,5012.3
Exp/Cntr=0.3,0.1

Type RM Length L Ch R = 1,9127,439,439,439
BEGIN DESCRIPTION:
THOMAS HOLLOW 11.0
END DESCRIPTION:
XS GIS Cut Line= 3
      2460075.00     13619674.99      2460225.00     13619225.00
      2459925.02     13618825.03
#Sta/Elev= 30
  4531.1  231.97  4562.7  230.51  4573.3  230.72  4699.7  226.72  4735.5  226.30
  4763.0  225.75  4773.5  224.79  4815.7  223.53  4847.3  220.99  4868.4  220.80
  4878.9  221.56  4910.6  221.75  4931.6  220.55  4952.7  220.25  4963.3  219.70
  4984.4  216.48  4992.3  216.00  4992.7  215.50  4997.0  215.50  4997.4  216.00
  5002.8  218.44  5008.6  218.44  5019.0  221.21  5029.9  222.26  5062.7  223.07
  5098.1  222.84  5233.6  224.44  5298.1  225.88  5383.6  228.47  5505.4  233.62
#Mann=5,-1,0
  4531.1    0.05       0  4735.5     0.1       0  4992.3    0.05       0
  4997.4     0.1       0  5029.9    0.05       0
Bank Sta=4992.3,4997.4
Exp/Cntr=0.3,0.1

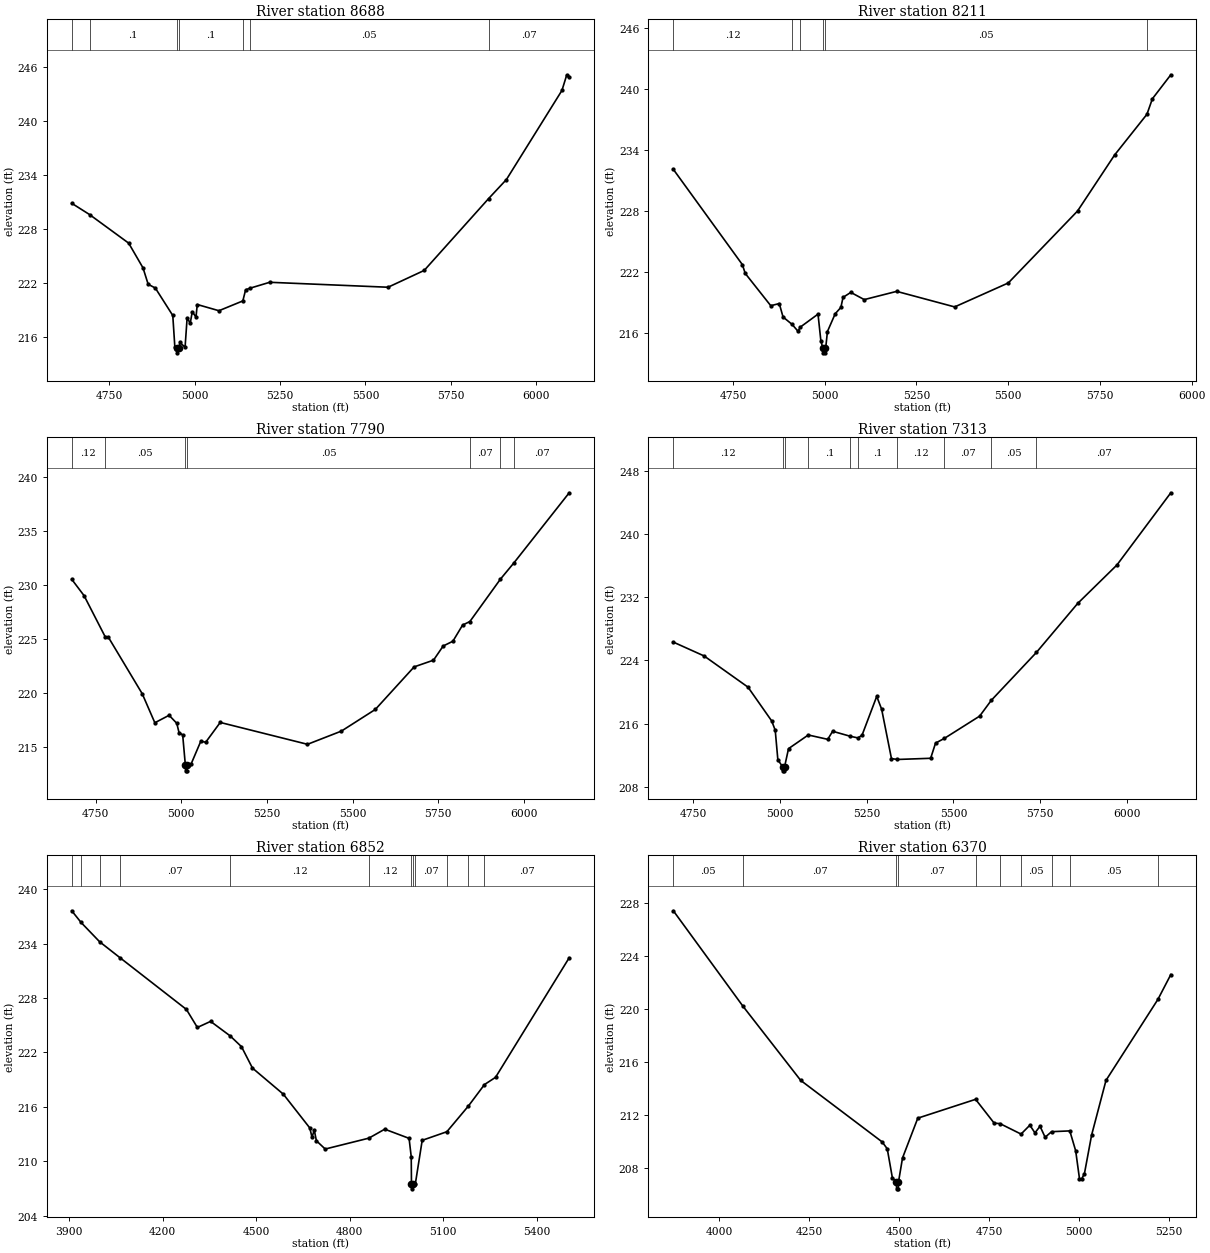
Type RM Length L Ch R = 1,8688,477,477,477
BEGIN DESCRIPTION:
THOMAS HOLLOW 10.0
END DESCRIPTION:
XS GIS Cut Line= 3
      2460124.98     13619675.02      2460425.00     13619475.00
      2461175.02     13618674.98
#Sta/Elev= 30
  4639.7  230.83  4691.8  229.58  4806.5  226.40  4848.5  223.65  4863.6  221.83
  4884.6  221.41  4935.7  218.36  4941.7  214.89  4948.2  214.71  4948.5  214.21
  4953.3  214.71  4956.7  215.36  4971.7  214.83  4977.7  218.09  4986.8  217.50
  4992.8  218.78  5003.7  218.18  5007.4  219.58  5070.9  218.89  5140.9  219.98
  5149.0  221.21  5160.8  221.38  5219.6  222.05  5566.2  221.50  5672.2  223.37
  5860.5  231.34  5913.0  233.47  6075.6  243.37  6089.8  245.11  6096.9  244.91
#Mann=7,-1,0
  4639.7    0.05       0  4691.8     0.1       0  4948.2    0.05       0
  4953.3     0.1       0  5140.9    0.12       0  5160.8    0.05       0
  5860.5    0.07       0
Bank Sta=4948.2,4953.3
Exp/Cntr=0.3,0.1

Type RM Length L Ch R = 1,8211,421,421,421
BEGIN DESCRIPTION:
THOMAS HOLLOW 9.0
END DESCRIPTION:
XS GIS Cut Line= 3
      2460724.99     13619975.05      2460825.00     13619575.00
      2461325.02     13618774.96
#Sta/Elev= 30
  4587.4  232.10  4775.6  222.72  4783.3  221.86  4852.9  218.68  4876.1  218.89
  4886.4  217.57  4911.0  216.84  4927.6  216.15  4932.6  216.55  4981.7  217.85
  4989.4  215.24  4994.6  214.54  4995.0  214.04  4999.4  214.04  4999.8  214.54
  5002.7  214.54  5007.4  216.14  5028.6  217.89  5044.0  218.51  5049.9  219.50
  5071.1  219.99  5107.7  219.28  5196.1  220.09  5354.1  218.56  5500.3  220.92
  5689.0  228.00  5789.9  233.51  5878.1  237.52  5893.0  239.05  5943.2  241.41
#Mann=6,-1,0
  4587.4    0.12       0  4911.0    0.07       0  4932.6    0.05       0
  4994.6    0.05       0  4999.8    0.05       0  5878.1    0.07       0
Bank Sta=4994.6,4999.8
Exp/Cntr=0.3,0.1

Type RM Length L Ch R = 1,7790,477,477,477
BEGIN DESCRIPTION:
THOMAS HOLLOW 8.0
END DESCRIPTION:
XS GIS Cut Line= 3
      2460875.00     13620025.00      2461125.00     13619825.00
      2461924.98     13619025.02
#Sta/Elev= 30
  4680.4  230.52  4716.4  229.01  4777.7  225.23  4786.9  225.19  4886.1  219.95
  4922.9  217.27  4964.5  217.96  4986.9  217.22  4993.4  216.37  5004.1  216.15
  5012.0  213.33  5012.5  212.83  5016.9  212.83  5017.3  213.33  5028.8  213.47
  5057.1  215.57  5071.3  215.47  5113.7  217.30  5368.3  215.28  5467.2  216.50
  5566.2  218.50  5679.4  222.43  5735.9  223.05  5764.2  224.36  5792.5  224.80
  5820.8  226.29  5842.1  226.62  5931.1  230.53  5970.9  232.05  6131.9  238.51
#Mann=7,-1,0
  4680.4    0.12       0  4777.7    0.05       0  5012.0    0.05       0
  5017.3    0.05       0  5842.1    0.07       0  5931.1    0.05       0
  5970.9    0.07       0
Bank Sta=5012,5017.3
Exp/Cntr=0.3,0.1

Type RM Length L Ch R = 1,7313,461,461,461
BEGIN DESCRIPTION:
THOMAS HOLLOW 7.0
END DESCRIPTION:
XS GIS Cut Line= 3
      2461375.01     13620424.96      2461425.00     13620125.00
      2462225.02     13619324.98
#Sta/Elev= 30
  4691.9  226.32  4780.6  224.57  4907.3  220.62  4975.7  216.34  4985.9  215.16
  4993.5  211.42  5007.5  210.52  5007.9  210.02  5012.4  210.02  5012.8  210.52
  5024.3  212.83  5081.3  214.56  5137.4  214.01  5151.6  215.03  5203.0  214.39
  5224.5  214.19  5236.4  214.53  5278.8  219.45  5293.0  217.82  5321.3  211.57
  5338.5  211.46  5434.4  211.61  5448.5  213.53  5474.0  214.13  5575.8  216.95
  5609.4  218.95  5739.5  225.01  5858.7  231.22  5971.8  236.08  6127.4  245.23
#Mann=10,-1,0
  4691.9    0.12       0  5007.5    0.05       0  5012.8    0.12       0
  5081.3     0.1       0  5203.0    0.05       0  5224.5     0.1       0
  5338.5    0.12       0  5474.0    0.07       0  5609.4    0.05       0
  5739.5    0.07       0
Bank Sta=5007.5,5012.8
Exp/Cntr=0.3,0.1

Type RM Length L Ch R = 1,6852,482,482,482
BEGIN DESCRIPTION:
THOMAS HOLLOW 6.0
END DESCRIPTION:
XS GIS Cut Line= 3
      2461125.03     13620874.97      2461875.00     13620075.00
      2462174.98     13619675.03
#Sta/Elev= 30
  3907.9  237.62  3937.9  236.33  3997.5  234.20  4064.0  232.41  4275.9  226.74
  4311.1  224.75  4353.6  225.42  4416.3  223.82  4452.7  222.63  4487.9  220.27
  4587.0  217.39  4672.0  213.66  4678.9  212.64  4686.2  213.43  4693.1  212.25
  4721.4  211.34  4861.4  212.54  4912.4  213.53  4990.5  212.52  4997.4  210.49
  4998.2  207.45  4998.6  206.95  5003.9  207.45  5010.6  207.50  5032.6  212.30
  5111.8  213.25  5181.0  216.09  5232.4  218.45  5268.0  219.25  5504.4  232.44
#Mann=12,-1,0
  3907.9   0.035       0  3937.9    0.07       0  3997.5   0.035       0
  4064.0    0.07       0  4416.3    0.12       0  4861.4    0.12       0
  4998.2    0.05       0  5003.9    0.12       0  5010.6    0.07       0
  5111.8    0.12       0  5181.0    0.05       0  5232.4    0.07       0
Bank Sta=4998.2,5003.9
Exp/Cntr=0.3,0.1

Type RM Length L Ch R = 1,6370,447,447,447
BEGIN DESCRIPTION:
THOMAS HOLLOW 5.0
END DESCRIPTION:
XS GIS Cut Line= 3
      2461525.00     13620975.00      2462325.00     13620175.00
      2462325.00     13619924.97
#Sta/Elev= 30
  3872.9  227.42  4066.0  220.23  4226.5  214.63  4452.7  209.99  4466.9  209.47
  4481.0  207.30  4492.3  206.95  4492.8  206.45  4497.6  206.45  4498.0  206.95
  4509.3  208.78  4551.7  211.78  4712.2  213.20  4763.9  211.40  4779.9  211.37
  4838.4  210.58  4862.9  211.25  4877.0  210.67  4891.1  211.17  4905.3  210.34
  4923.1  210.76  4973.8  210.82  4990.1  209.32  5000.7  207.21  5006.8  207.21
  5014.3  207.58  5034.3  210.50  5074.3  214.63  5218.3  220.73  5254.3  222.61
#Mann=10,-1,0
  3872.9    0.05       0  4066.0    0.07       0  4492.3    0.05       0
  4498.0    0.07       0  4712.2    0.05       0  4779.9    0.12       0
  4838.4    0.05       0  4923.1    0.12       0  4973.8    0.05       0
  5218.3    0.07       0
Bank Sta=4492.3,4498
Exp/Cntr=0.3,0.1

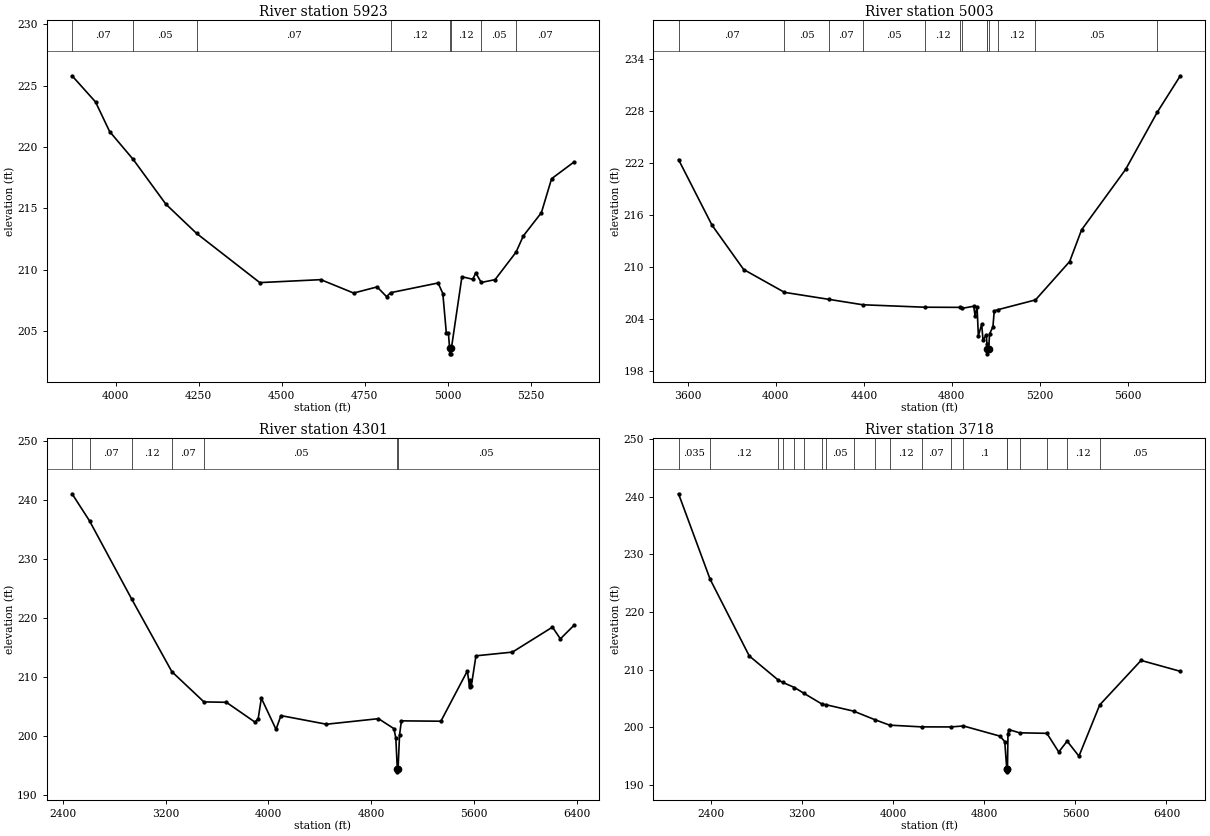
Type RM Length L Ch R = 1,5923,920,920,920
BEGIN DESCRIPTION:
THOMAS HOLLOW 4.0
END DESCRIPTION:
XS GIS Cut Line= 3
      2461774.98     13621275.02      2462575.00     13620475.00
      2462725.00     13620124.99
#Sta/Elev= 30
  3868.4  225.80  3939.1  223.67  3981.6  221.26  4052.3  219.00  4151.3  215.34
  4243.9  212.96  4434.1  208.96  4618.0  209.20  4717.0  208.11  4787.7  208.61
  4816.0  207.82  4828.7  208.14  4971.5  208.93  4985.7  208.07  4996.3  204.85
  5002.5  204.85  5006.0  203.66  5006.5  203.16  5011.3  203.16  5011.8  203.66
  5043.3  209.44  5076.0  209.23  5085.0  209.75  5101.4  208.97  5143.1  209.20
  5206.4  211.44  5228.3  212.76  5282.7  214.65  5313.5  217.42  5380.6  218.77
#Mann=8,-1,0
  3868.4    0.07       0  4052.3    0.05       0  4243.9    0.07       0
  4828.7    0.12       0  5006.0    0.05       0  5011.8    0.12       0
  5101.4    0.05       0  5206.4    0.07       0
Bank Sta=5006,5011.8
Exp/Cntr=0.3,0.1

Type RM Length L Ch R = 1,5003,702,702,702
BEGIN DESCRIPTION:
THOMAS HOLLOW 3.0
END DESCRIPTION:
XS GIS Cut Line= 3
      2461974.97     13621425.02      2463175.00     13620625.00
      2462925.00     13619825.01
#Sta/Elev= 30
  3557.9  222.37  3709.7  214.83  3853.9  209.71  4039.4  207.08  4242.2  206.27
  4395.8  205.65  4676.0  205.37  4839.0  205.35  4846.3  205.24  4899.5  205.48
  4905.5  204.37  4914.5  205.41  4920.5  202.08  4935.6  203.41  4941.6  201.56
  4956.6  202.21  4959.6  201.09  4961.2  200.50  4961.7  200.00  4967.0  200.50
  4971.6  202.31  4986.6  203.10  4992.6  204.93  5010.2  205.09  5180.1  206.21
  5335.4  210.63  5389.4  214.27  5589.5  221.23  5734.1  227.85  5838.3  232.02
#Mann=13,-1,0
  3557.9    0.07       0  4039.4    0.05       0  4242.2    0.07       0
  4395.8    0.05       0  4676.0    0.12       0  4839.0    0.05       0
  4846.3    0.12       0  4959.6    0.05       0  4961.2    0.05       0
  4967.0    0.05       0  5010.2    0.12       0  5180.1    0.05       0
  5734.1    0.07       0
Bank Sta=4961.2,4967
Exp/Cntr=0.3,0.1

Type RM Length L Ch R = 1,4301,583,583,583
BEGIN DESCRIPTION:
XS7844
END DESCRIPTION:
XS GIS Cut Line= 4
      2461509.38     13621724.21      2463488.54     13620955.99
      2463892.19     13620435.16      2463384.39     13619432.58
#Sta/Elev= 30
  2472.7  241.00  2608.7  236.41  2936.4  223.19  3249.7  210.88  3499.1  205.77
  3673.7  205.70  3896.9  202.34  3921.4  202.95  3946.0  206.40  4060.3  201.12
  4098.5  203.45  4452.5  201.99  4857.8  202.93  4978.2  201.24  4992.7  199.64
  5004.2  194.43  5004.7  193.93  5010.2  194.43  5021.7  200.17  5036.2  202.56
  5343.5  202.50  5549.6  211.01  5566.2  208.34  5571.8  209.45  5579.9  208.40
  5616.4  213.57  5900.4  214.20  6212.2  218.43  6273.4  216.44  6378.5  218.71
#Mann=7,-1,0
  2472.7   0.035       0  2608.7    0.07       0  2936.4    0.12       0
  3249.7    0.07       0  3499.1    0.05       0  5004.2    0.05       0
  5010.2    0.05       0
Bank Sta=5004.2,5010.2
Exp/Cntr=0.3,0.1

Type RM Length L Ch R = 1,3718,0,0,0
BEGIN DESCRIPTION:
XS7843
END DESCRIPTION:
XS GIS Cut Line= 3
      2461522.43     13621945.57      2463228.13     13621594.01
      2465233.37     13619836.17
#Sta/Elev= 30
  2113.3  240.52  2390.6  225.70  2734.5  212.39  2985.8  208.26  3030.6  207.78
  3131.6  206.91  3213.5  205.92  3374.1  204.03  3405.4  203.94  3651.5  202.81
  3838.9  201.32  3967.9  200.38  4248.9  200.08  4504.6  200.07  4615.8  200.24
  4936.3  198.48  4979.0  197.54  4996.8  192.78  4997.3  192.28  5002.9  192.78
  5007.4  198.83  5014.1  199.62  5108.7  199.05  5349.4  198.96  5453.5  195.72
  5527.2  197.61  5630.9  195.00  5813.4  203.89  6176.6  211.61  6521.5  209.72
#Mann=20,-1,0
  2113.3   0.035       0  2390.6    0.12       0  2985.8    0.07       0
  3030.6    0.12       0  3131.6    0.07       0  3213.5    0.05       0
  3374.1    0.12       0  3405.4    0.05       0  3651.5    0.12       0
  3838.9    0.05       0  3967.9    0.12       0  4248.9    0.07       0
  4504.6    0.05       0  4615.8     0.1       0  4996.8    0.05       0
  5002.9     0.1       0  5108.7    0.12       0  5349.4     0.1       0
  5527.2    0.12       0  5813.4    0.05       0
Bank Sta=4996.8,5002.9
Exp/Cntr=0.3,0.1

Chan Stop Cuts=-1